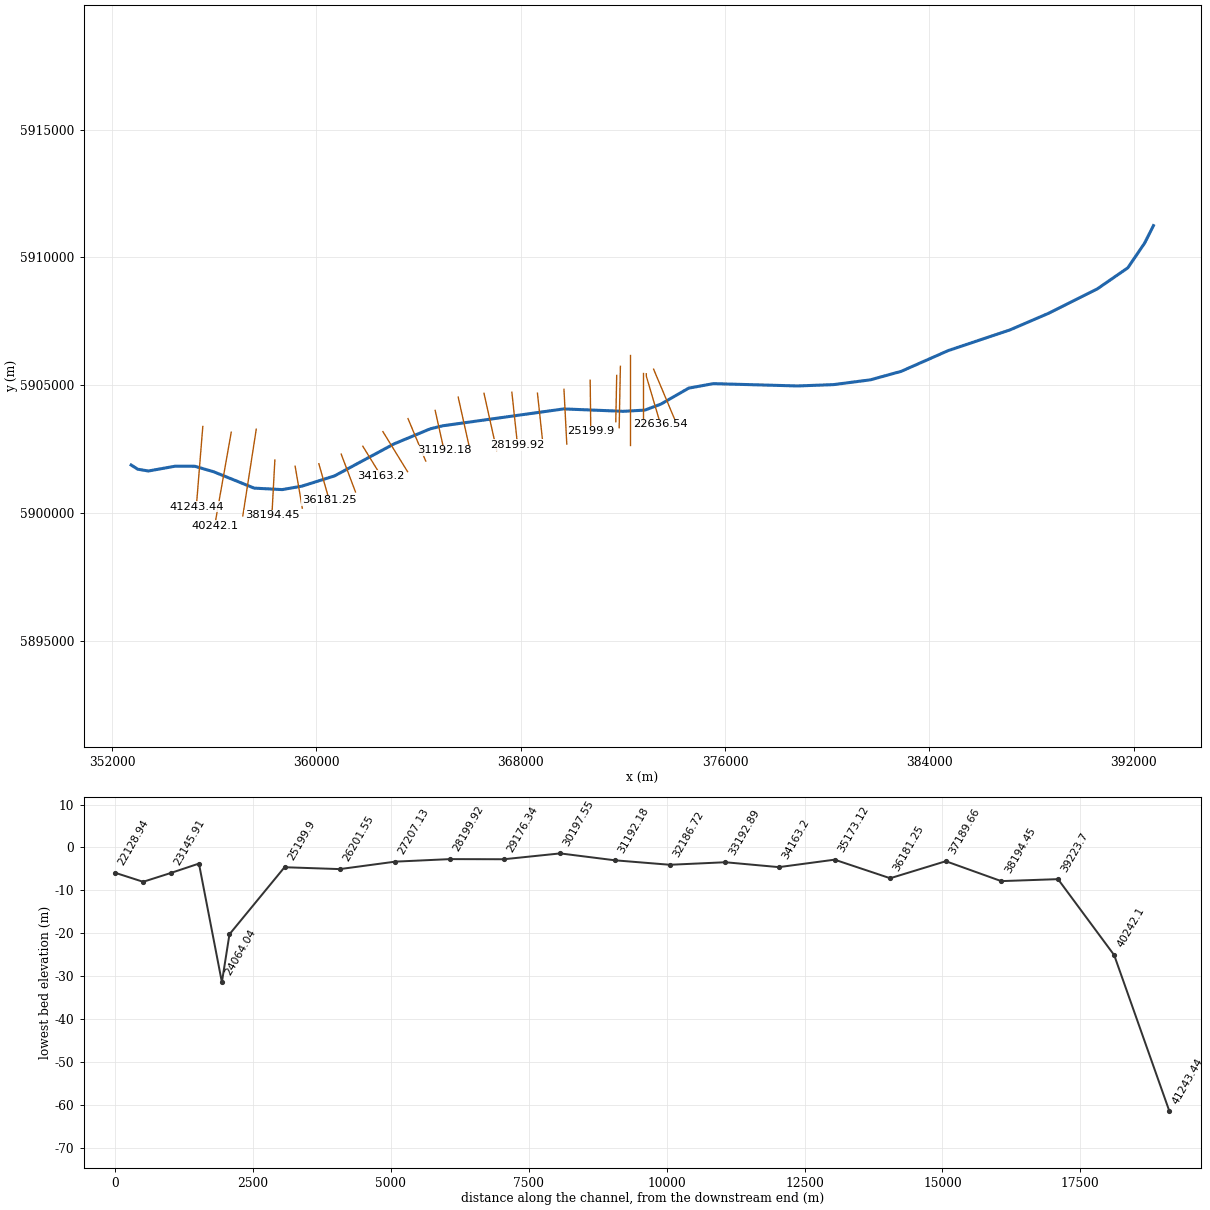
HEC-RAS study Churchill_Mapping.prj: Churchill River Flood Risk Mapping

--- Churchill_Mapping.u17 (unsteady flow) ---

Flow Title=2018 Jun - Aug
Program Version=5.07
Use Restart= 0
Initial Flow Loc=Churchill River ,Main            ,41243.44,3785
Initial Flow Loc=Churchill River ,Main DS         ,874.7763,3800.2
Initial Flow Loc=Mud Lake A      ,Main A          ,4343.607,7.6
Initial Flow Loc=Mud Lake B      ,Main            ,5538.203,7.6
Initial Flow Loc=Mud Lake C      ,Main            ,3296.746,15.2
Initial Flow Loc=Mud Lake In     ,In              ,100     ,15.2
Initial Storage Elev=Mud Lake        ,0.5
Boundary Location=Churchill River ,Main            ,41243.44,        ,                ,                ,                ,
Interval=1HOUR
Flow Hydrograph= 1464
3785.4953784.7843786.4073788.1633788.2973789.1953790.6283793.211 3793.843796.502
4062.073 4052.46 4052.434053.3744054.375 4051.344052.2834172.9424172.6184172.556
4172.8494169.3094173.5294174.889 4320.684324.4854325.849 4328.354331.2034336.247
4518.1644522.8344527.735 4861.824834.1724834.5894837.2894844.1584840.5024843.471
4847.7894999.2415006.7425014.9725020.9335023.9935024.8135027.3055078.4635082.915
5080.8165086.5415083.138  5086.75087.0825087.4635087.5595095.0045087.2415089.754
 5091.445085.937 5087.055084.8555082.7565081.2295079.2585081.3564943.4724950.209
4948.3694951.0834953.5474949.616 4950.244952.6114949.7414950.646 4955.174944.251
4942.8174936.8614931.4064928.9434924.7064925.5164639.7574662.5664663.9634663.797
4667.349 4669.224671.1144667.3494668.675 4666.974668.8884666.3074666.4024664.981
4662.2344658.7534658.3514655.0594650.5354648.2614426.744 4440.374444.2284440.438
4446.7314444.0024445.5134441.1824443.528 4439.314441.0474439.6254302.4464312.324
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Use DSS=False
Use Fixed Start Time=False
Is Critical Boundary=False
Boundary Location=Mud Lake In     ,In              ,100     ,        ,                ,                ,                ,
Interval=1HOUR
Flow Hydrograph= 1464
    15.2    15.2    15.3    15.3    15.3    15.4    15.4    15.4    15.4    15.5
    15.5    15.5    15.6    15.6    15.6    15.6    15.7    15.7    15.7    15.8
    15.8    15.8    15.8    15.9    15.9    15.9      16      16      16    16.1
    16.1    16.1    16.1    16.2    16.2    16.2    16.3    16.3    16.3    16.4
    16.4    16.4    16.4    16.5    16.5    16.5    16.6    16.6    16.6    16.7
    16.7    16.7    16.8    16.8    16.8    16.8    16.9    16.9    16.9      17
      17      17    17.1    17.1    17.1    17.2    17.2    17.2    17.3    17.3
    17.3    17.3    17.4    17.4    17.4    17.5    17.5    17.5    17.6    17.6
    17.6    17.7    17.7    17.7    17.7    17.8    17.8    17.8    17.9    17.9
    17.9      18      18      18      18    18.1    18.1    18.1    18.2    18.2
    18.2    18.2    18.3    18.3    18.3    18.4    18.4    18.4    18.4    18.5
    18.5    18.5    18.5    18.6    18.6    18.6    18.6    18.7    18.7    18.7
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Use DSS=False
Use Fixed Start Time=False
Is Critical Boundary=False
Boundary Location=Churchill River ,Main            ,9566.389,        ,                ,                ,                ,
Interval=1HOUR
Lateral Inflow Hydrograph= 1464
   338.3   342.1   345.9   349.9   353.9   358.1   362.3   366.6   370.9   375.3
   379.7   384.1   388.6     393   397.4   401.8   406.1   410.3   414.4   418.4
   422.4   426.2     430   433.7   437.3   440.8   444.2   447.3   450.2   452.9
   455.3   457.5   459.4     461   462.3   463.4   464.1   464.5   464.7   464.6
   464.1   463.4   462.5   461.3   459.8     458     456   453.8   451.3   448.5
   445.5   442.3   438.9   435.2   431.4   427.4   423.3     419   414.7   410.2
   405.6   400.9   396.2   391.5   386.7   381.9     377   372.2   367.3   362.3
   357.4   352.6   347.8     343   338.5     334   329.7   325.5   321.4   317.5
   313.6   309.9   306.3   302.9   299.5   296.3   293.1   290.1   287.1   284.3
   281.6   278.9   276.2   273.7   271.1   268.6   266.1   263.7   261.3   258.8
   256.4     254   251.6   249.2   246.8   244.4   241.9   239.5     237   234.5
   231.9   229.4   226.7   224.1   221.3   218.6   215.8   212.9     210   207.1
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Use DSS=False
Use Fixed Start Time=False
Is Critical Boundary=False
Boundary Location=Churchill River ,Main            ,40242.1 ,        ,                ,                ,                ,
Interval=1HOUR
Lateral Inflow Hydrograph= 1464
    75.8    76.8    77.8    78.8    79.9    80.9    81.9      83      84      85
      86      87      88    88.9    89.8    90.7    91.6    92.4    93.1    93.9
    94.5    95.2    95.8    96.3    96.9    97.4    97.9    98.3    98.6    98.9
    99.1    99.3    99.4    99.4    99.3    99.2      99    98.7    98.3    97.9
    97.4    96.9    96.2    95.5    94.8    93.9    93.1    92.1    91.2    90.2
    89.2    88.1      87    85.9    84.8    83.6    82.5    81.3    80.1    78.9
    77.8    76.7    75.6    74.5    73.5    72.5    71.5    70.5    69.6    68.7
    67.9      67    66.2    65.4    64.6    63.9    63.2    62.5    61.8    61.1
    60.5    59.8    59.2    58.6    58.1    57.5      57    56.5      56    55.6
    55.1    54.7    54.3    53.9    53.5      53    52.6    52.2    51.8    51.3
    50.9    50.4    49.9    49.4    48.9    48.4    47.9    47.3    46.7    46.1
    45.5    44.9    44.2    43.6    42.9    42.2    41.5    40.8    40.1    39.4
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Use DSS=False
Use Fixed Start Time=False
Is Critical Boundary=False
Boundary Location=Churchill River ,Main            ,36181.25,        ,                ,                ,                ,
Interval=1HOUR
Lateral Inflow Hydrograph= 1465
    50.4    50.5    50.6    50.6    50.6    50.5    50.5    50.4    50.2    50.1
    49.9    49.8    49.6    49.4      49    48.6    48.1    47.4    46.7    45.9
    45.2    44.6    44.3    44.2    44.4    44.6    44.7    44.5    43.8    42.7
    41.1    39.3    37.4    35.6    33.9    32.4      31    29.8    28.7    27.7
    26.9    26.3    25.8    25.4      25      25      25    24.9    24.9    24.9
    24.9    24.9    24.8    24.8    24.8    24.8    24.8    24.7    24.7    24.7
    24.7    24.6    24.6    24.6    24.6    24.6    24.7    24.7    24.8    24.8
    24.9      25    25.1    25.2    25.4    25.5    25.6    25.7    25.8    25.9
      26    26.1    26.2    26.3    26.3    26.4    26.5    26.6    26.8    26.9
      27      27    26.9    26.5      26    25.4      25      25    24.9    24.9
    24.9    24.9    24.9    24.8    24.8    24.8    24.8    24.8    24.7    24.7
    24.7    24.7    24.7    24.6    24.6    24.6    24.6    24.6    24.5    24.5
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Use DSS=False
Use Fixed Start Time=False
Is Critical Boundary=False
Boundary Location=Churchill River ,Main            ,25199.9 ,        ,                ,                ,                ,
Interval=1HOUR
Lateral Inflow Hydrograph= 1465
    52.6    52.9    53.1    53.3    53.4    53.5    53.5    53.5    53.4    53.3
    53.2    53.1    52.9    52.7    52.3    51.9    51.3    50.5    49.7    48.7
    47.8    46.9    46.3      46      46    46.1    46.1    45.9    45.2      44
    42.3    40.3    37.9    35.4      33    30.8    28.7    26.7      25    23.4
      22    20.8    19.8      19    18.2    17.7    17.2    16.7    16.4    16.1
    15.8    15.6    15.4    15.2    15.1    14.9    14.7    14.6    14.4    14.3
    14.2    14.1      14    13.9    13.8    13.8    13.8    13.8    13.9      14
    14.1    14.2    14.3    14.5    14.6    14.8    14.9    15.1    15.2    15.4
    15.5    15.6    15.8    15.9    16.1    16.3    16.4    16.6    16.8    17.1
    17.2    17.3    17.2    16.9    16.5    15.8      15    14.1    13.2    12.3
    11.5    10.8    10.2     9.6     9.1     8.6     8.2     7.8     7.5     7.1
     6.9     6.6     6.4     6.2     6.2     6.2     6.2     6.2     6.2     6.2
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Use DSS=False
Use Fixed Start Time=False
Is Critical Boundary=False
Boundary Location=Churchill River ,Main            ,13613.57,        ,                ,                ,                ,
Interval=1HOUR
Lateral Inflow Hydrograph= 1465
    40.9      41    41.1    41.2    41.2    41.1      41    40.9    40.8    40.7
    40.5    40.3    40.1    39.9    39.5    39.1    38.5    37.8    36.9    36.1
    35.2    34.6    34.3    34.2    34.4    34.7    34.8    34.5    33.8    32.5
    30.7    28.7    26.5    24.5    22.6    20.9    19.3    17.9    16.6    15.6
    14.7      14    13.4    12.9    12.6    12.3    12.1      12    11.8    11.8
    11.7    11.7    11.6    11.6    11.5    11.5    11.4    11.4    11.3    11.2
    11.2    11.1    11.1    11.1    11.1    11.2    11.2    11.3    11.4    11.5
    11.6    11.7    11.8      12    12.1    12.3    12.4    12.5    12.7    12.8
    12.9      13    13.1    13.3    13.4    13.5    13.6    13.8    13.9    14.1
    14.3    14.3    14.1    13.7    13.1    12.4    11.6    10.8      10     9.4
     8.8     8.3     7.8     7.4       7     6.7     6.5     6.5     6.5     6.5
     6.5     6.5     6.5     6.5     6.5     6.4     6.4     6.4     6.4     6.4
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Use DSS=False
Use Fixed Start Time=False
Is Critical Boundary=False
Boundary Location=Churchill River ,Main DS         ,-1972.08,        ,                ,                ,                ,
Interval=1HOUR
Stage Hydrograph= 1464
    .003    .084     .08    .011   -.058   -.128   -.197   -.266   -.335   -.361
   -.301   -.241    -.18    -.12   -.097   -.146   -.194   -.242    -.29   -.338
   -.372    -.29   -.209   -.128   -.047    .034    .115    .053   -.015   -.084
   -.154   -.223   -.292   -.361   -.338   -.279    -.22    -.16   -.101   -.113
   -.161    -.21   -.258   -.306   -.354   -.351   -.286    -.22   -.154   -.088
   -.022   -.001   -.055   -.111   -.165    -.22   -.275    -.33   -.377   -.319
   -.261   -.204   -.146   -.087    -.11   -.143   -.175   -.208   -.241   -.273
   -.242   -.192   -.142   -.091   -.041    .009   -.024   -.077   -.132   -.185
   -.239   -.293   -.347   -.361   -.306    -.25   -.195    -.14   -.084   -.113
   -.147   -.181   -.215   -.249   -.278   -.227   -.176   -.125   -.074   -.023
     .01   -.042   -.095   -.148   -.201   -.254   -.306   -.359   -.361   -.327
   -.292   -.258   -.224    -.19   -.195   -.213   -.231   -.249   -.267   -.268
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Use DSS=False
Use Fixed Start Time=False
Is Critical Boundary=False

--- Churchill_Mapping.g33 (geometry) ---

Geom Title=Current Conditions - KGS LiDAR Clipped
Program Version=4.10

Junct Name=J2
Junct Desc=, 0 , 0 ,-1 ,0
Up River,Reach=Mud Lake A      ,Main A
Up River,Reach=Mud Lake B      ,Main
Dn River,Reach=Mud Lake C      ,Main
Junc L&A=748.2,0
Junc L&A=406.05,0

Junct Name=J3
Junct Desc=, 0 , 0 ,-1 ,0
Up River,Reach=Churchill River ,Main
Up River,Reach=Mud Lake C      ,Main
Dn River,Reach=Churchill River ,Main DS
Junc L&A=329.13,
Junc L&A=0,

River Reach=Churchill River ,Main
Reach XY= 30
      352746.205    5901870.9107     353004.0902    5901707.0009
     353420.8098     5901636.357     354472.7952     5901825.799
     355239.9892    5901821.6318     355973.1246    5901608.4963
     357565.9195    5900965.5575     358660.9476    5900908.7374
     359433.5325    5901044.2043     360708.3637    5901444.4094
     363043.2479    5902699.8532     364462.8616    5903289.8951
     364940.0188    5903405.8247     369682.2204    5904067.5335
     372003.6472    5903973.4233     372857.1925    5904020.3913
     373484.7877    5904254.4113     374575.1212    5904881.1223
     375539.3177    5905057.0816     378839.9485    5904966.4881
     380249.1116    5905018.9498     381688.4319    5905206.2566
     382895.9556    5905538.7512     384737.2631    5906351.3853
     387170.5262    5907167.2208     388678.6542    5907818.0971
      390570.517    5908765.1309     391766.4875    5909590.2807
      392425.707     5910559.566392769.8948848085911242.63821614

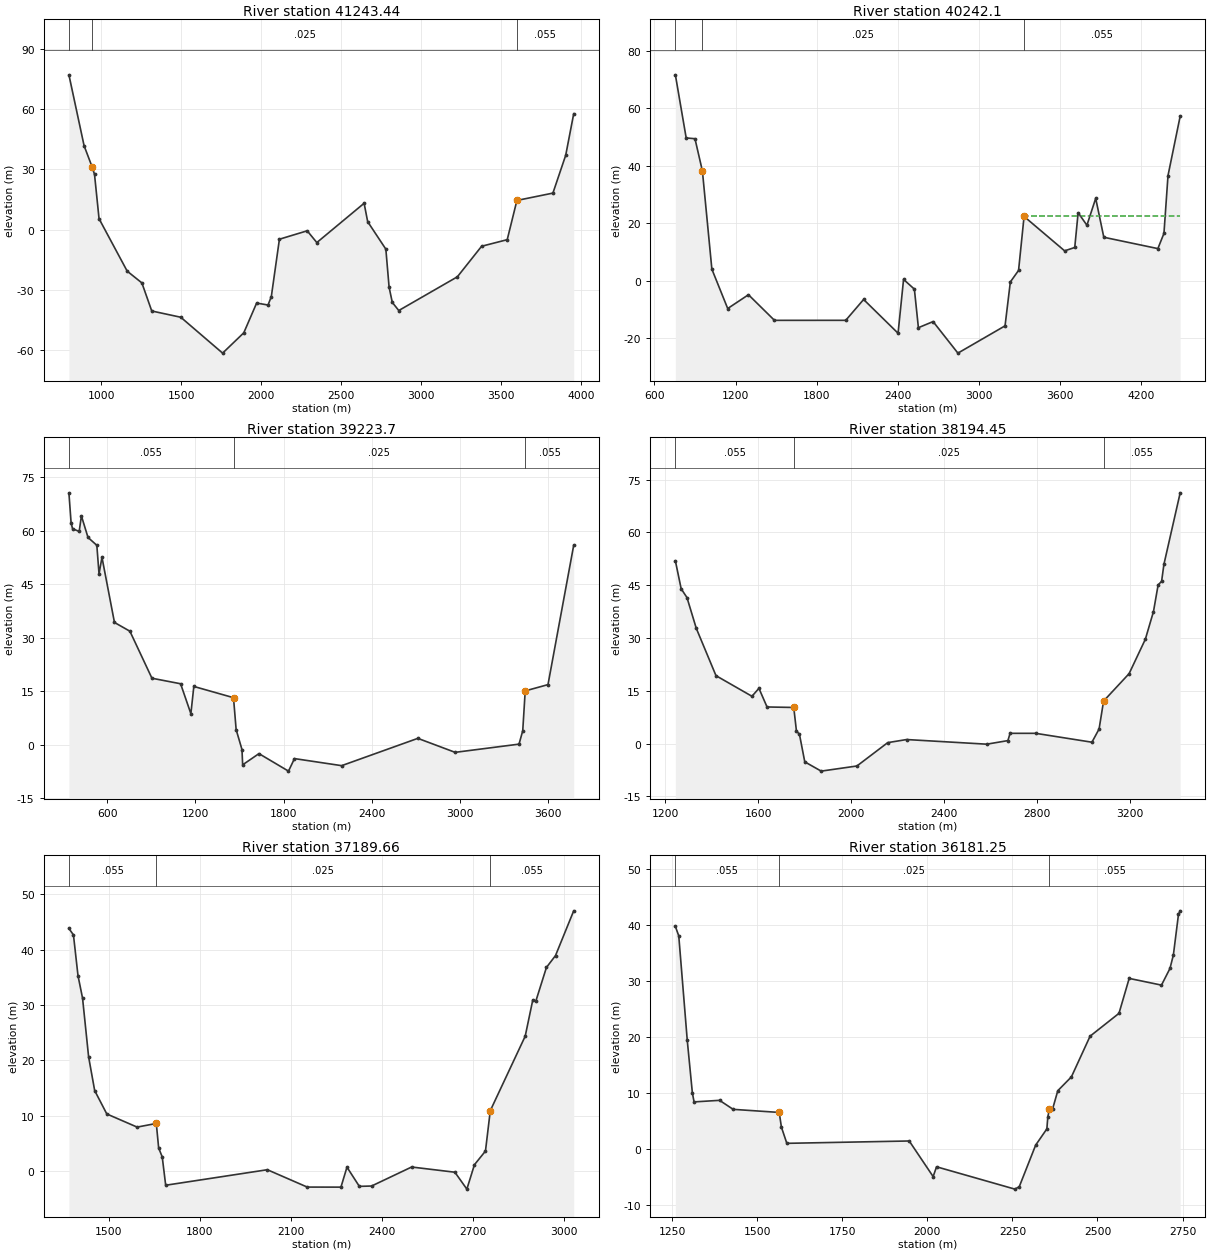
Type RM Length L Ch R = 1 ,41243.44,1199.65,1001.34,790.16
XS GIS Cut Line= 2
355551.9021897725903380.25918935355298.2267538125900237.71443768
#Sta/Elev= 30
  799.44   77.12  894.37   41.78  944.34   31.26  959.33   27.58  987.68    5.45
 1163.41  -20.66 1255.24  -26.53 1316.83  -40.51 1498.23  -43.63 1759.43   -61.5
 1891.64  -51.38 1971.99  -36.56 2043.03  -37.54 2063.54   -33.4 2114.18   -4.76
  2287.7    -.57 2347.85   -6.43 2643.14   13.14 2665.47    3.97 2778.97   -9.71
 2799.18  -28.64 2819.15  -36.23 2859.64  -40.28 3225.62  -23.48 3376.96   -8.27
 3536.99   -4.99 3597.47   14.55 3822.32   18.21 3902.26   37.05 3952.23   57.74
#Mann= 3 , 0 , 0
  799.44    .055       0  944.34    .025       0 3597.47    .055       0
Bank Sta=944.34,3597.47
XS Rating Curve= 0 ,0
Exp/Cntr(USF)=0.3,0.1
Exp/Cntr=0.5,0.3

Type RM Length L Ch R = 1 ,40242.1 ,968.29,1018.41,1034.79
XS GIS Cut Line= 2
356665.7540205175903155.76013423356014.6894317675899481.03599879
#Sta/Elev= 30
  754.38    71.6  834.32   49.67  899.26    49.4  954.22   38.18 1024.16    4.08
 1141.25    -9.6 1294.67   -4.81 1486.99  -13.71 2013.92   -13.7 2146.03   -6.46
 2400.71  -18.19 2441.37     .51 2521.35   -2.87 2551.03  -16.26 2659.73  -14.14
 2843.13   -25.1 3191.64  -15.62 3230.76    -.37 3291.56    3.64 3332.28   22.39
 3632.03   10.44 3706.96   11.61 3731.94   23.69 3796.89   19.33 3861.84   28.68
 3921.79   15.16 4321.47   11.22 4366.43   16.51 4396.41   36.61 4486.34   57.23
#Mann= 3 , 0 , 0
  754.38    .055       0  954.22    .025       0 3332.28    .055       0
#XS Ineff= 2 , 0
                         3331.54           22.41
Permanent Ineff=
       F       F
Bank Sta=954.22,3332.28
XS Rating Curve= 0 ,0
Exp/Cntr(USF)=0.3,0.1
Exp/Cntr=0.5,0.3

Type RM Length L Ch R = 1 ,39223.7 ,827.11,1029.24,1183.39
XS GIS Cut Line= 2
357644.9400931885903272.44553403357118.595832677 5899880.4101248
#Sta/Elev= 30
  339.76   70.56  354.75   62.12  364.75   60.49  409.72   59.75  424.71    64.1
  469.67   58.06  529.63   55.86  544.62   47.85  564.61   52.49  649.55   34.25
  754.48    31.8  904.37   18.63 1099.24   17.08 1169.19    8.69 1189.18   16.33
 1458.99   13.18 1476.97    4.23 1516.63   -1.34 1521.24   -5.62 1632.11   -2.49
 1832.97   -7.39 1873.58   -3.88 2194.44   -5.86 2712.49    1.79 2966.16   -2.13
 3400.49     .17  3425.8    3.91 3442.62   15.08 3597.51   16.84 3772.39   55.88
#Mann= 3 , 0 , 0
  339.76    .055       0 1458.99    .025       0 3442.62    .055       0
#XS Ineff= 2 , 0
         1452.07   13.17
Permanent Ineff=
       F       F
Bank Sta=1458.99,3442.62
XS Rating Curve= 0 ,0
Exp/Cntr(USF)=0.3,0.1
Exp/Cntr=0.5,0.3

Type RM Length L Ch R = 1 ,38194.45,590.64,1004.79,1303.96
XS GIS Cut Line= 2
358373.0744874665902065.84526603358256.6761285735899895.87627662
#Sta/Elev= 30
  1243.9   51.94 1268.88   43.99 1293.86   41.49 1333.82   32.76 1418.75   19.29
 1573.61   13.43 1603.59   15.69 1638.56   10.39 1753.46   10.25 1765.02     3.6
 1778.18    2.58 1800.95   -5.21 1871.59   -7.85 2025.46   -6.39 2157.97     .25
 2239.49    1.13 2584.52    -.19 2675.39     .83 2684.79     2.9 2794.67     2.9
 3037.14     .37 3067.92    4.13 3087.28   12.07 3197.18   19.87 3267.12   29.65
 3302.09   37.53 3322.07   45.08 3337.06   46.12 3347.05   50.95 3416.99   71.27
#Mann= 3 , 0 , 0
  1243.9    .055       0 1753.46    .025       0 3087.28    .055       0
Bank Sta=1753.46,3087.28
XS Rating Curve= 0 ,0
Exp/Cntr(USF)=0.3,0.1
Exp/Cntr=0.5,0.3

Type RM Length L Ch R = 1 ,37189.66,843.23,1008.41,1150.62
XS GIS Cut Line= 2
359167.6922901485901824.18651839359446.9824786115900183.87996252
#Sta/Elev= 30
 1369.11   43.82  1384.1   42.65 1399.09    35.3 1414.08   31.25 1434.07   20.65
 1454.06   14.57 1494.03   10.35 1593.97    7.98 1657.18    8.64 1664.93    4.22
 1676.74     2.6 1688.12   -2.51 2023.22     .29 2154.63   -2.84 2265.79   -2.85
 2285.66     .75 2326.42   -2.71 2366.79   -2.65 2498.76     .78 2641.36    -.16
 2680.87   -3.21 2705.79    1.19 2742.16    3.66 2758.04   10.94 2873.14   24.38
 2898.12   30.91 2908.12   30.69 2943.09   36.78 2973.07   38.93 3033.03      47
#Mann= 3 , 0 , 0
 1369.11    .055       0 1657.18    .025       0 2758.04    .055       0
Bank Sta=1657.18,2758.04
XS Rating Curve= 0 ,0
Exp/Cntr(USF)=0.3,0.1
Exp/Cntr=0.5,0.3

Type RM Length L Ch R = 1 ,36181.25,885.13,1008.13,1123.83
XS GIS Cut Line= 2
360095.6836881055901918.51135192360503.7541469965900491.71876408
#Sta/Elev= 30
 1259.15   39.75 1269.14   38.05 1294.12   19.38 1309.11   10.01 1314.11     8.4
 1389.06    8.68 1429.03    7.07 1564.42    6.52 1570.89    3.89 1586.82       1
 1946.64    1.42 2016.94   -4.94 2026.95   -3.19 2257.19   -7.18 2270.07   -6.75
  2318.3     .68 2351.23    3.58 2354.05    5.73 2358.72    7.05  2368.4     7.2
 2383.39    10.4 2423.36   12.87 2478.32   20.14 2563.26   24.22 2593.24   30.46
 2688.18   29.26 2713.16   32.24 2723.15   34.64 2738.14   41.89 2743.14   42.53
#Mann= 3 , 0 , 0
 1259.15    .055       0 1564.42    .025       0 2358.72    .055       0
Bank Sta=1564.42,2358.72
XS Rating Curve= 0 ,0
Exp/Cntr(USF)=0.3,0.1
Exp/Cntr=0.5,0.3

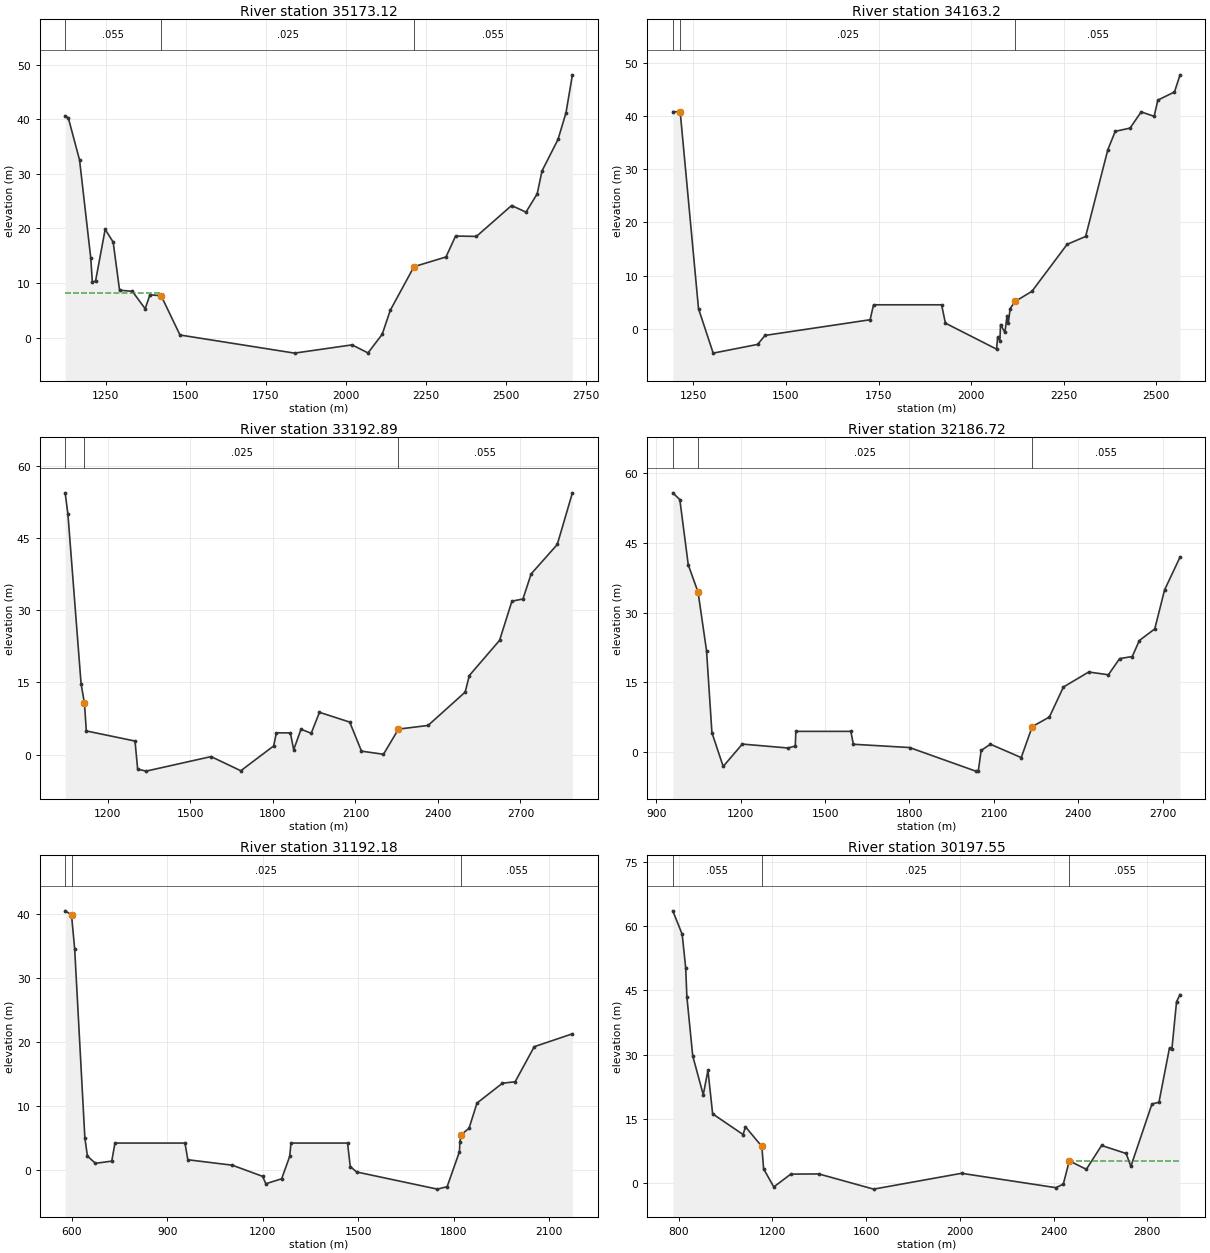
Type RM Length L Ch R = 1 ,35173.12,734.97,1009.92,1301.42
XS GIS Cut Line= 2
360970.3608625635902298.87858823 361529.021321395900817.96409063
#Sta/Elev= 30
 1123.44   40.61 1133.43    40.2 1168.38   32.51 1203.33   14.56 1208.32   10.16
 1218.31   10.34 1248.27   19.81 1273.23   17.49  1293.2    8.67 1333.15    8.47
 1373.09    5.28 1388.07    7.84 1423.02    7.66 1481.72     .47 1839.27   -2.85
 2018.55   -1.34 2068.51   -2.81 2112.77      .6 2137.88    4.99 2211.93   12.98
 2311.79   14.76 2341.75   18.59 2406.66   18.52 2516.51   24.18 2561.45   22.97
  2596.4   26.32 2611.38   30.51 2661.31   36.27 2686.28   41.16 2706.25   48.11
#Mann= 3 , 0 , 0
 1123.44    .055       0 1423.02    .025       0 2211.93    .055       0
#XS Ineff= 2 , 0
          1418.6    8.09
Permanent Ineff=
       F       F
Bank Sta=1423.02,2211.93
XS Rating Curve= 0 ,0
Exp/Cntr(USF)=0.3,0.1
Exp/Cntr=0.5,0.3

Type RM Length L Ch R = 1 ,34163.2 ,971.99,970.31,998.23
XS GIS Cut Line= 2
361817.0489163785902605.56069662362535.0387920345901439.35483532
#Sta/Elev= 30
 1194.58   40.84 1214.57   40.77 1263.95    3.78 1303.62   -4.59 1423.55   -2.95
  1443.5   -1.26 1727.24    1.69 1736.52     4.5 1920.35     4.5 1930.51    1.05
 2068.78   -3.84  2071.5   -1.62 2077.66   -2.23 2079.42     .78 2091.27     -.7
 2096.72    2.32 2100.31     .99 2105.39     3.8 2119.25    5.15 2164.23    7.04
  2259.2   15.87 2309.19   17.36 2369.16   33.69 2389.16   37.13 2429.14   37.74
 2459.13   40.79 2494.12   39.95 2504.12      43  2549.1   44.54  2564.1   47.76
#Mann= 3 , 0 , 0
 1194.58    .055       0 1214.57    .025       0 2119.25    .055       0
Bank Sta=1214.57,2119.25
XS Rating Curve= 0 ,0
Exp/Cntr(USF)=0.3,0.1
Exp/Cntr=0.5,0.3

Type RM Length L Ch R = 1 ,33192.89,1234.76,1006.17,727.63
XS GIS Cut Line= 2
362601.8736214855903179.97413019363568.7352490045901609.53455864
#Sta/Elev= 30
 1044.55   54.33 1054.55   49.98 1102.38   14.74 1114.71   10.63 1121.57     4.9
 1298.54     2.8 1308.13   -3.03 1338.96   -3.45 1575.04    -.43 1683.15   -3.37
 1802.73    1.79 1812.54     4.5 1863.37     4.5 1875.41       1 1902.07    5.25
 1939.17    4.42 1969.15    8.77  2079.1    6.74 2121.95      .7 2201.93     .05
 2256.35    5.28 2363.98    6.04 2498.92   12.97 2513.92   16.41 2623.87   23.71
 2668.85   31.86 2708.83   32.31 2738.82   37.53 2833.78   43.64 2888.75   54.37
#Mann= 3 , 0 , 0
 1044.55    .055       0 1114.71    .025       0 2256.35    .055       0
Bank Sta=1114.71,2256.35
XS Rating Curve= 0 ,0
Exp/Cntr(USF)=0.3,0.1
Exp/Cntr=0.5,0.3

Type RM Length L Ch R = 1 ,32186.72,1219.67,994.54,671.77
XS GIS Cut Line= 2
363585.524373777 5903689.3092772364280.2721808325902025.70106655
#Sta/Elev= 30
  958.86   55.74  983.83   54.29 1013.79   40.28 1048.75   34.37 1078.71   21.85
 1097.93    4.21 1137.88   -3.04 1205.86    1.77 1367.96     .93 1394.13    1.34
 1396.22     4.5 1591.57     4.5 1600.56    1.73 1800.13    1.03 2035.51   -4.04
 2044.77   -3.94  2054.8      .4 2087.54    1.74 2197.18   -1.13 2236.26    5.52
 2297.26    7.58  2347.2   14.03 2437.09   17.25 2507.01   16.66 2546.96   20.13
 2591.91   20.58 2616.88   24.01 2671.81   26.51 2706.77    34.9  2761.7   41.94
#Mann= 3 , 0 , 0
  958.86    .055       0 1048.75    .025       0 2236.26    .055       0
Bank Sta=1048.75,2236.26
XS Rating Curve= 0 ,0
Exp/Cntr(USF)=0.3,0.1
Exp/Cntr=0.5,0.3

Type RM Length L Ch R = 1 ,31192.18,1034.11,994.63,993.08
XS GIS Cut Line= 2
364649.3241861275904008.64111034364995.5919739045902453.27202352
#Sta/Elev= 30
  579.43   40.49  599.41   39.85   609.4   34.48  641.34    5.01   649.4    2.16
  674.61    1.03  725.89    1.38  735.88     4.2  955.84     4.2  964.84    1.59
 1104.56     .74 1199.53      -1 1209.85   -2.16  1259.6   -1.38 1285.02    2.15
 1288.82     4.2 1466.49     4.2 1475.03     .53 1495.17    -.32 1748.66      -3
 1779.35   -2.62  1818.1    2.85 1819.33    4.38 1823.45    5.51 1848.19    6.51
 1873.17   10.45 1953.09   13.55 1993.05   13.78 2052.99   19.26 2172.88   21.27
#Mann= 3 , 0 , 0
  579.43    .055       0  599.41    .025       0 1823.45    .055       0
Bank Sta=599.41,1823.45
XS Rating Curve= 0 ,0
Exp/Cntr(USF)=0.3,0.1
Exp/Cntr=0.5,0.3

Type RM Length L Ch R = 1 ,30197.55,1025.02,1021.21,1018.34
XS GIS Cut Line= 2
365551.1467196745904527.67976934366021.5640176275902414.65468567
#Sta/Elev= 30
  774.91    63.5  814.91   58.03  829.91    50.2   834.9   43.49   859.9   29.68
   904.9   20.61  924.89   26.32  944.89   16.16 1074.88   11.34 1084.88   13.15
 1154.87    8.57 1162.47    3.34 1205.81    -.88 1278.44    2.11 1398.24    2.15
 1631.86   -1.39 2007.11     2.3 2409.88   -1.05 2441.47    -.22 2466.92    5.21
 2539.71    3.23  2604.7    8.79 2709.69    6.92 2729.69    3.91 2819.68   18.45
 2849.67   18.87 2894.67   31.57 2904.67   31.18 2924.66   42.31 2939.66   43.98
#Mann= 3 , 0 , 0
  774.91    .055       0 1154.87    .025       0 2466.92    .055       0
#XS Ineff= 2 , 0
                          2465.4            5.18
Permanent Ineff=
       F       F
Bank Sta=1154.87,2466.92
XS Rating Curve= 0 ,0
Exp/Cntr(USF)=0.3,0.1
Exp/Cntr=0.5,0.3

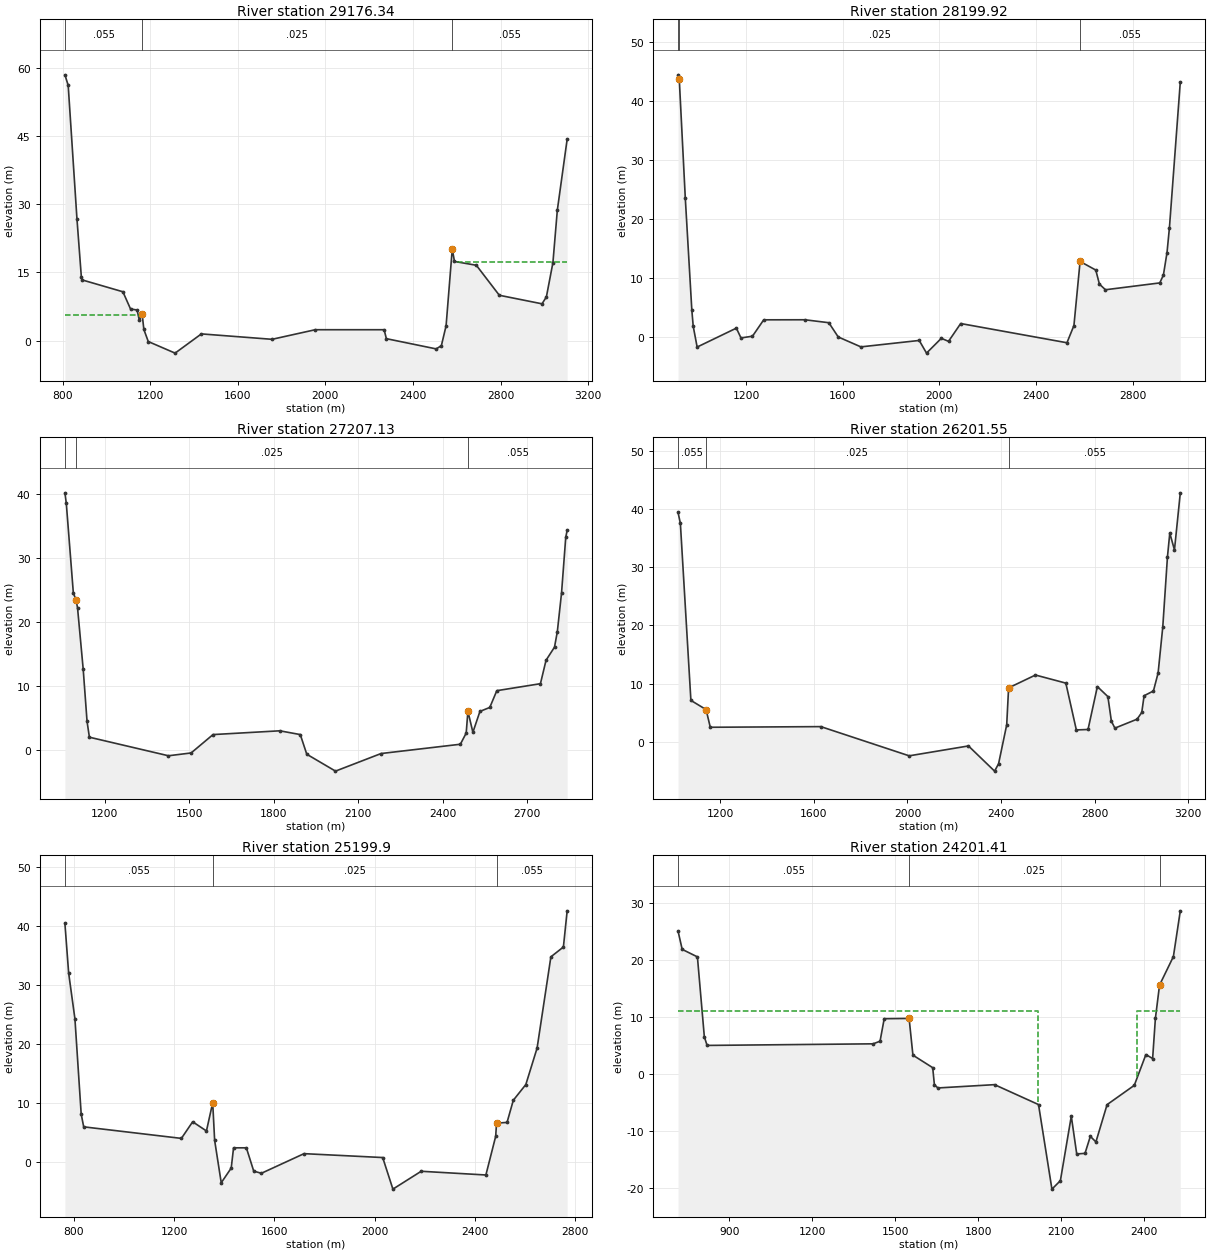
Type RM Length L Ch R = 1 ,29176.34,1138.34,976.42,790.73
XS GIS Cut Line= 2
366560.9276692795904678.03350944367059.5760711035902438.19974385
#Sta/Elev= 30
  809.88   58.48  824.88   56.17  864.87   26.84  884.87    14.1  889.87   13.34
 1074.84   10.75 1109.84    6.95 1139.83    6.74 1149.83    4.47 1162.71    5.88
 1170.58    2.46 1190.71     -.2 1313.32   -2.75 1433.44    1.48 1756.23     .29
 1953.58     2.4 2268.33     2.4 2278.55     .43 2506.13   -1.82 2529.83   -1.11
 2551.38    3.26 2579.62   20.19 2589.62   17.42 2689.61   16.58 2794.59    9.98
 2989.56     8.1 3009.56     9.6 3039.55   17.18 3059.55   28.68 3104.55   44.32
#Mann= 3 , 0 , 0
  809.88    .055       0 1162.71    .025       0 2579.62    .055       0
#XS Ineff= 2 , 0
         1146.63    5.57 2601.53           17.35
Permanent Ineff=
       F       F
Bank Sta=1162.71,2579.62
XS Rating Curve= 0 ,0
Exp/Cntr(USF)=0.3,0.1
Exp/Cntr=0.5,0.3

Type RM Length L Ch R = 1 ,28199.92,995.41,992.79,993.66
XS GIS Cut Line= 2
367651.6502519545904722.52372833 367873.887254415902656.81752187
#Sta/Elev= 30
  918.94   44.49  923.94   43.81  948.91    23.6  975.96    4.58  981.63    1.86
  997.91   -1.69 1160.16    1.52 1179.25    -.14 1226.81     .15 1273.38    2.93
 1443.34    2.94 1542.65    2.44 1581.58     .02 1675.29   -1.66 1916.58    -.57
 1946.78   -2.72 2007.94    -.21 2037.83    -.72 2088.11     2.3 2527.66    -.96
 2556.52    1.96 2582.03   12.83 2646.95   11.37 2661.93    8.99  2686.9    8.03
 2911.64    9.19 2926.62   10.52  2941.6   14.34 2951.59   18.56 2996.54   43.29
#Mann= 3 , 0 , 0
  918.94    .055       0  923.94    .025       0 2582.03    .055       0
#XS Ineff= 2 , 0
                         2636.98           11.56
Permanent Ineff=
       F       F
Bank Sta=923.94,2582.03
XS Rating Curve= 0 ,0
Exp/Cntr(USF)=0.3,0.1
Exp/Cntr=0.5,0.3

Type RM Length L Ch R = 1 ,27207.13,1086.67,1005.59,915.85
XS GIS Cut Line= 2
368653.9797961015904684.76221193368844.699946377  5902912.006482
#Sta/Elev= 30
  1058.8   40.17  1063.8   38.51 1088.77   24.51 1098.76   23.39 1103.75   22.16
  1123.8   12.59 1137.41    4.46 1145.74    1.99 1426.43    -.91 1506.89    -.47
  1584.6     2.4  1821.6    2.99 1894.43     2.4 1917.42    -.67 2019.36   -3.31
 2181.25    -.56 2462.69     .89  2483.4    2.64 2489.38    6.04 2507.16    2.76
 2532.14    6.02  2567.1    6.64 2592.07    9.26 2746.89   10.35 2766.87   14.02
 2796.84   16.06 2806.83   18.46 2821.81   24.51 2836.79   33.24 2841.79   34.31
#Mann= 3 , 0 , 0
  1058.8    .055       0 1098.76    .025       0 2489.38    .055       0
#XS Ineff= 2 , 0
                         2492.91             5.3
Permanent Ineff=
       F       F
Bank Sta=1098.76,2489.38
XS Rating Curve= 0 ,0
Exp/Cntr(USF)=0.3,0.1
Exp/Cntr=0.5,0.3

Type RM Length L Ch R = 1 ,26201.55,1068.28,1001.65,945.48
XS GIS Cut Line= 2
369691.8209327125904835.26165984369802.4220721925902690.43859519
#Sta/Elev= 30
 1018.89   39.42 1028.88   37.54 1073.83    7.11 1138.76    5.53 1156.73    2.49
 1629.49     2.6 2007.26   -2.42 2260.72    -.72 2372.44   -5.05 2389.44   -3.79
 2424.26    2.91 2432.36    9.26 2547.24   11.47  2677.1   10.08 2722.05    2.03
 2771.99    2.11 2811.95    9.48  2856.9    7.76 2871.89    3.53 2886.87    2.34
 2981.77    3.88 3001.75    5.03 3011.74    7.91 3051.69    8.73 3071.67   11.82
 3091.65   19.75 3111.63   31.78 3121.62   35.87  3141.6   32.98 3166.57   42.79
#Mann= 3 , 0 , 0
 1018.89    .055       0 1138.76    .025       0 2432.36    .055       0
#XS Ineff= 2 , 0
                         2456.32            9.52
Permanent Ineff=
       F       F
Bank Sta=1138.76,2432.36
XS Rating Curve= 0 ,0
Exp/Cntr(USF)=0.3,0.1
Exp/Cntr=0.5,0.3

Type RM Length L Ch R = 1 ,25199.9 ,1065.31,998.49,975.09
XS GIS Cut Line= 2
370718.3077095245905191.75483746370741.7553093775903188.30404968
#Sta/Elev= 30
  764.45   40.49  779.44   32.04  804.43   24.29  829.41    8.13   839.4    5.96
 1229.12       4 1274.09    6.82 1329.05    5.26 1354.04   10.06 1361.74    3.67
 1388.08   -3.53 1427.87   -1.04 1437.24     2.4 1488.35     2.4 1517.74   -1.56
  1548.3   -1.92 1718.39    1.41 2032.18     .75 2072.87   -4.61 2185.69   -1.58
 2443.79   -2.21 2482.95    4.36 2486.28    6.59  2528.2    6.71 2553.18   10.47
 2603.14   13.14 2648.11   19.33 2703.07   34.81 2753.03   36.48 2768.02   42.62
#Mann= 3 , 0 , 0
  764.45    .055       0 1354.04    .025       0 2486.28    .055       0
#XS Ineff= 2 , 0
         1352.24    9.07
Permanent Ineff=
       F       F
Bank Sta=1354.04,2486.28
XS Rating Curve= 0 ,0
Exp/Cntr(USF)=0.3,0.1
Exp/Cntr=0.5,0.3

Type RM Length L Ch R = 1 ,24201.41,139.37,137.37,138.3
XS GIS Cut Line= 2
371756.7121453255905380.33097292371720.4204786075903565.74943093
#Sta/Elev= 30
  714.98   25.08  729.98   21.87  784.98   20.55  809.97    6.52  819.97       5
 1419.95    5.28 1444.95    5.74 1459.95    9.69 1549.95    9.74 1563.74    3.29
 1635.23    1.09 1641.31   -1.91 1653.94   -2.47  1858.7   -1.89 2017.59   -5.39
 2066.03  -20.24 2096.55  -18.76 2136.02   -7.43 2155.63  -14.06 2185.55  -13.96
 2204.82  -10.97 2224.98  -11.95 2265.34    -5.4 2363.69   -2.01 2405.55    3.39
 2429.92     2.7 2439.92    9.75 2454.92    15.6 2504.92    20.6 2529.92   28.64
#Mann= 3 , 0 , 0
  714.98    .055       0 1549.95    .025       0 2454.92    .055       0
#XS Ineff= 2 , 0
       0    2015      11    2375       0      11
Permanent Ineff=
       F       F
Bank Sta=1549.95,2454.92
XS Rating Curve= 0 ,0
Exp/Cntr(USF)=0.3,0.1
Exp/Cntr=0.5,0.3

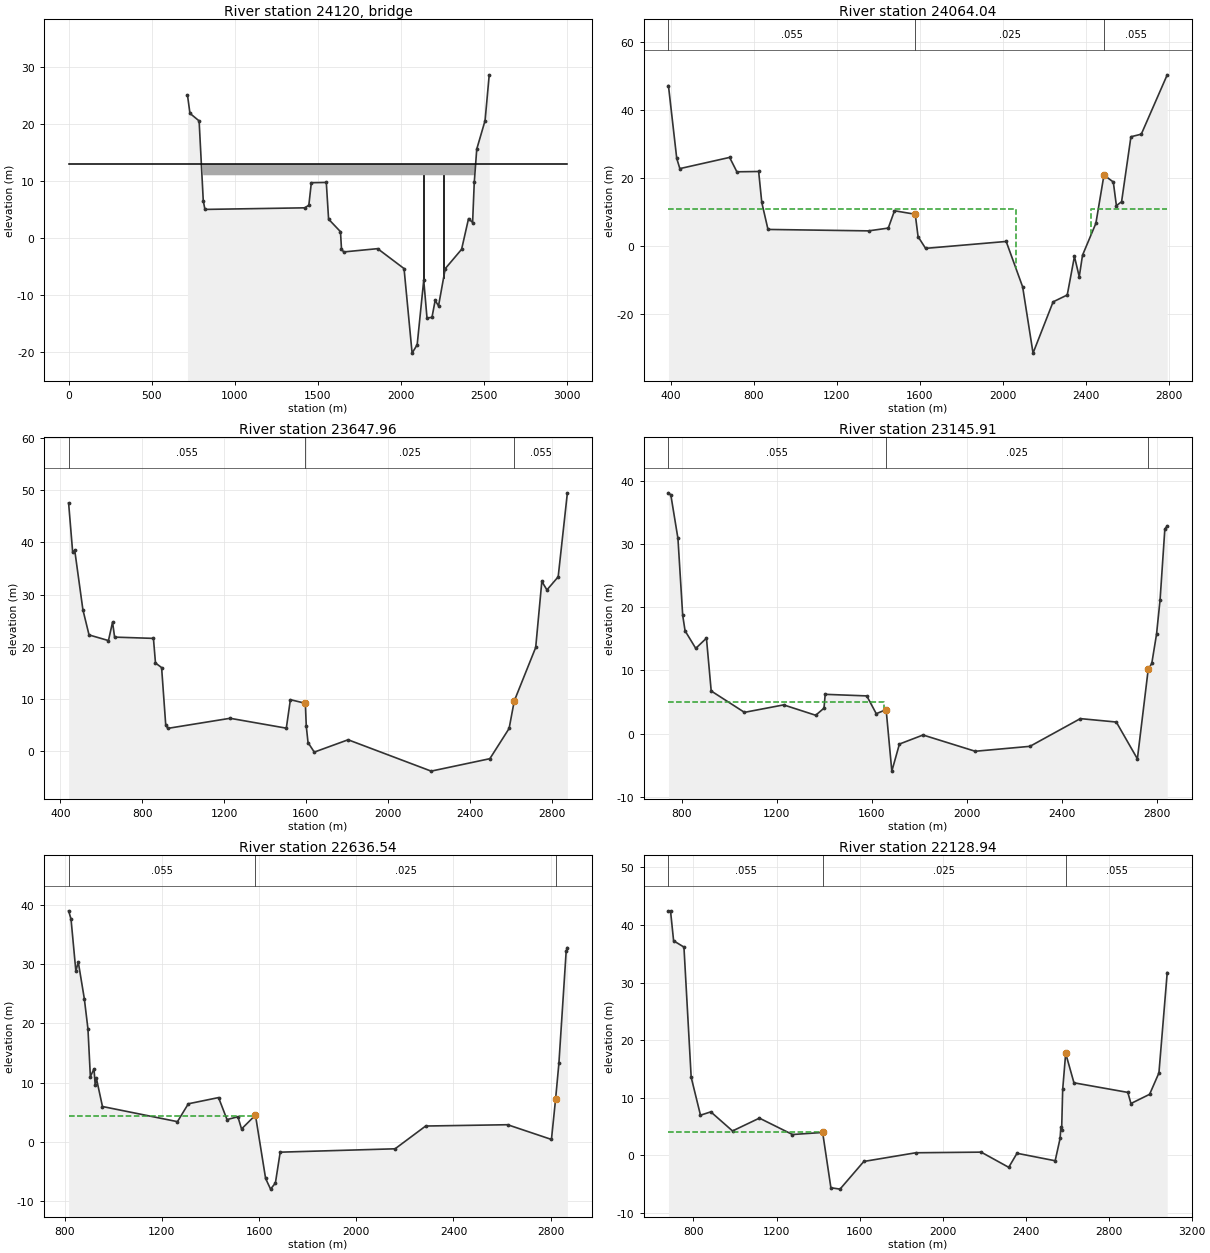
Type RM Length L Ch R = 3 ,24120   ,,,
Bridge Culvert--1,0,-1,-1, 0
Deck Dist Width WeirC Skew NumUp NumDn MinLoCord MaxHiCord MaxSubmerge Is_Ogee
60,20,1.4,0, 2, 2, , , 0.98, 0, 0,0,,
       0    3000
      13      13
      11      11
       0    3000
      13      13
      11      11
Pier Skew, UpSta & Num, DnSta & Num=  ,2135, 2 ,2185, 2 , 0 , 0 , 0 ,,
       1       1
   10.99   10.99
       1       1
   10.99   10.99
Pier Skew, UpSta & Num, DnSta & Num=  ,2255, 2 ,2305, 2 , 0 , 0 , 0 ,,
       1       1
   10.99   10.99
       1       1
   10.99   10.99
Abutment Skew #Up #Dn= , 2 , 2
       0    2015
      11      11
       0    2065
      11      11
BR Coef=-1 , 0 , 0 ,, 0 ,,,0.8,-1,,0,
WSPro=,,,, 1 ,,,, 0 ,,,, 0 ,,,,-1 ,-1 ,-1 , 0 , 0 , 0 , 0 , 0
BC Design=,, 0 ,, 0 ,,,,,,
BC HTab HWMax=11
BC Use User HTab Curves=0
BC User HTab FreeFlow(D)= 0

Type RM Length L Ch R = 1 ,24064.04,382.78,416.08,439.98
XS GIS Cut Line= 2
371901.1531471015905733.05358407 371853.121241045903331.46154319
#Sta/Elev= 30
  389.53    47.2  429.48    25.8  444.46   22.81  684.17    26.1  719.13   21.87
     824   21.96  838.98   12.89  868.94    4.93 1353.36    4.51 1448.24    5.33
  1478.2   10.42 1578.08    9.39 1591.72    2.81 1627.89    -.63 2016.08     1.4
 2095.38  -11.96 2145.42  -31.42 2242.07  -16.35 2310.14  -14.33 2344.75   -3.01
 2367.92   -8.96 2383.75   -2.63 2448.08    6.73 2486.98   20.92 2531.92   18.87
  2546.9   11.91 2571.87   13.09 2616.82   32.17 2666.76   32.93  2791.6   50.37
#Mann= 3 , 0 , 0
  389.53    .055       0 1578.08    .025       0 2486.98    .055       0
#XS Ineff= 2 , 0
            2065      11    2425              11
Permanent Ineff=
       F       F
Bank Sta=1578.08,2486.98
XS Rating Curve= 0 ,0
Exp/Cntr(USF)=0.5,0.3
Exp/Cntr=0.5,0.3

Type RM Length L Ch R = 1 ,23647.96,505.71,502.05,500
XS GIS Cut Line= 2
     372282.0612    5906167.8354     372282.0612    5902665.7447
#Sta/Elev= 30
  439.63   47.56  459.62   38.08  469.61   38.48  509.58    27.1  539.55    22.3
  634.47   21.22  654.46   24.75  664.45   21.88  854.29   21.64  864.28   16.93
  894.26   16.05  914.24    5.13  924.23    4.42 1228.98    6.35 1503.75    4.46
 1523.73    9.91 1596.74    9.22 1601.42    4.82 1609.95     1.7 1640.47    -.12
 1805.82    2.24 2211.82   -3.76 2498.71   -1.38 2592.85    4.41 2617.83    9.65
 2722.74    19.9 2752.71   32.54 2777.69   30.91 2832.65   33.42 2877.61   49.49
#Mann= 3 , 0 , 0
  439.63    .055       0 1596.74    .025       0 2617.83    .055       0
#XS Ineff= 2 , 0
         1570.62    8.99
Permanent Ineff=
       F       F
Bank Sta=1596.74,2617.83
XS Rating Curve= 0 ,0
Exp/Cntr(USF)=0.5,0.3
Exp/Cntr=0.5,0.3

Type RM Length L Ch R = 1 ,23145.91,131.3,509.36,874.95
XS GIS Cut Line= 2
     372782.06125905486.04409512     372782.06125903387.08730234
#Sta/Elev= 30
  744.63   38.07  754.63   37.75  784.61   30.86   804.6   18.71   814.6   16.26
  859.58   13.48  904.55    15.1  924.54    6.75 1064.47    3.37 1229.39    4.55
 1364.33    2.91 1399.31    4.04 1404.31    6.22 1579.22    5.97  1619.2    3.16
 1660.71     3.8 1684.71   -5.92 1716.64   -1.64  1816.1    -.21 2035.59   -2.78
 2266.02      -2 2478.04    2.38 2629.31    1.84 2718.07   -3.98 2763.64   10.17
 2778.63    11.1 2798.62   15.72 2813.61   21.18  2833.6   32.35  2843.6   32.84
#Mann= 3 , 0 , 0
  744.63    .055       0 1660.71    .025       0 2763.64    .055       0
#XS Ineff= 2 , 0
         1650.03    4.95
Permanent Ineff=
       F       F
Bank Sta=1660.71,2763.64
XS Rating Curve= 0 ,0
Exp/Cntr(USF)=0.5,0.3
Exp/Cntr=0.5,0.3

Type RM Length L Ch R = 1 ,22636.54,243.38,507.6,678.94
XS GIS Cut Line= 4
372915.9574064325905440.96374746     372916.6397     5905346.413
     373087.2052     5904768.912373471.2682796985903468.55016847
#Sta/Elev= 30
  816.19   39.05  826.14   37.66  846.05   28.86     856   30.39  880.88   24.19
  895.81   19.08  905.77   11.02   920.7   12.32  925.67    9.55  930.65    10.7
  955.53    5.96 1264.08     3.4 1308.87    6.42 1433.28    7.47 1468.12    3.75
 1512.91    4.23 1527.86    2.16  1585.1    4.51 1626.94   -6.21 1647.35   -8.01
 1667.18   -6.98 1686.98   -1.76 2159.79   -1.19 2285.57    2.66 2622.79    2.88
 2803.24     .39 2820.13    7.15 2833.91   13.28 2863.82   32.22  2868.8   32.83
#Mann= 3 , 0 , 0
  816.19    .055       0  1585.1    .025       0 2820.13    .055       0
#XS Ineff= 2 , 0
         1579.13    4.32
Permanent Ineff=
       F       F
Bank Sta=1585.1,2820.13
XS Rating Curve= 0 ,0
Exp/Cntr(USF)=0.5,0.3
Exp/Cntr=0.5,0.3

Type RM Length L Ch R = 1 ,22128.94,396.14,507.49,502.51
XS GIS Cut Line= 4
373202.0571685045905621.70403538     373431.5829    5905075.4949
      373964.584    5903807.0964374132.8194875145903406.74148285
#Sta/Elev= 30
  679.37   42.35  689.33   42.46  704.26   37.25  754.05   36.16   788.9   13.53
  833.71    6.94   883.5    7.52  988.05     4.2  1117.5    6.43 1276.83    3.58
 1422.15    3.94 1461.91   -5.67 1505.84   -5.91 1620.56    -1.1 1870.69     .41
 2185.71     .52 2318.46   -2.12 2358.41     .32 2542.19    -.98 2565.98    2.91
 2569.67    4.91 2573.33    4.36 2578.41   11.41 2592.85   17.69 2632.73   12.57
 2892.26    10.9 2907.24    8.97 2997.08   10.57 3042.01   14.29 3081.94   31.73
#Mann= 3 , 0 , 0
  679.37    .055       0 1422.15    .025       0 2592.85    .055       0
#XS Ineff= 2 , 0
         1408.68     4.1
Permanent Ineff=
       F       F
Bank Sta=1422.15,2592.85
XS Rating Curve= 0 ,0
Exp/Cntr(USF)=0.5,0.3
Exp/Cntr=0.5,0.3