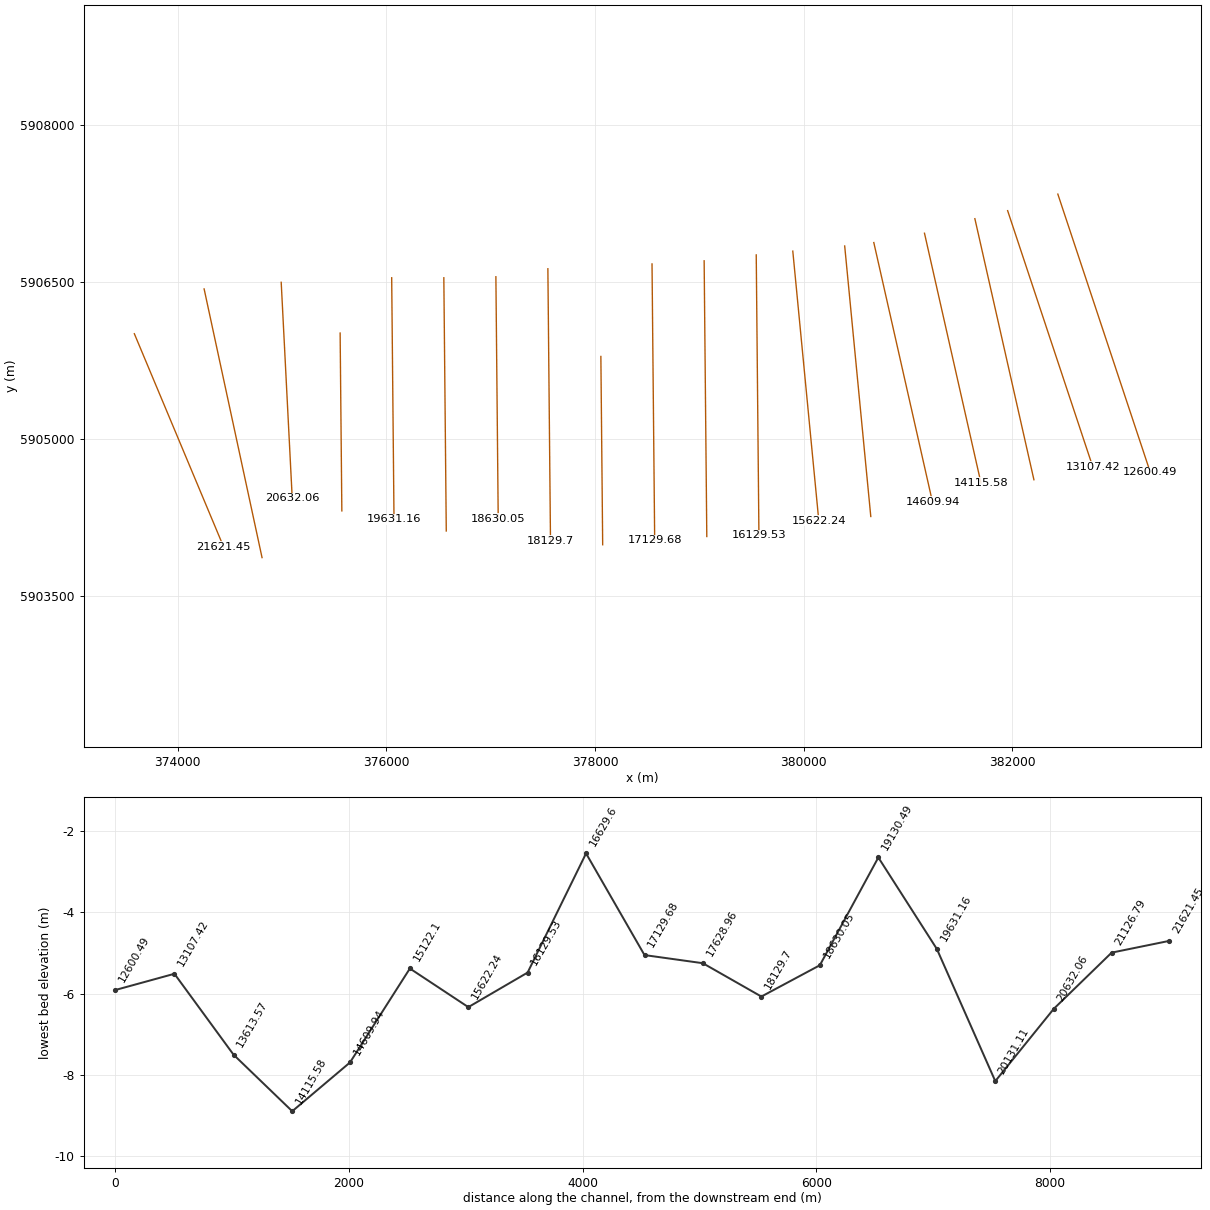
HEC-RAS study Churchill_Mapping.prj: Churchill River Flood Risk Mapping

--- Churchill_Mapping.g33 (geometry) --- (continued)

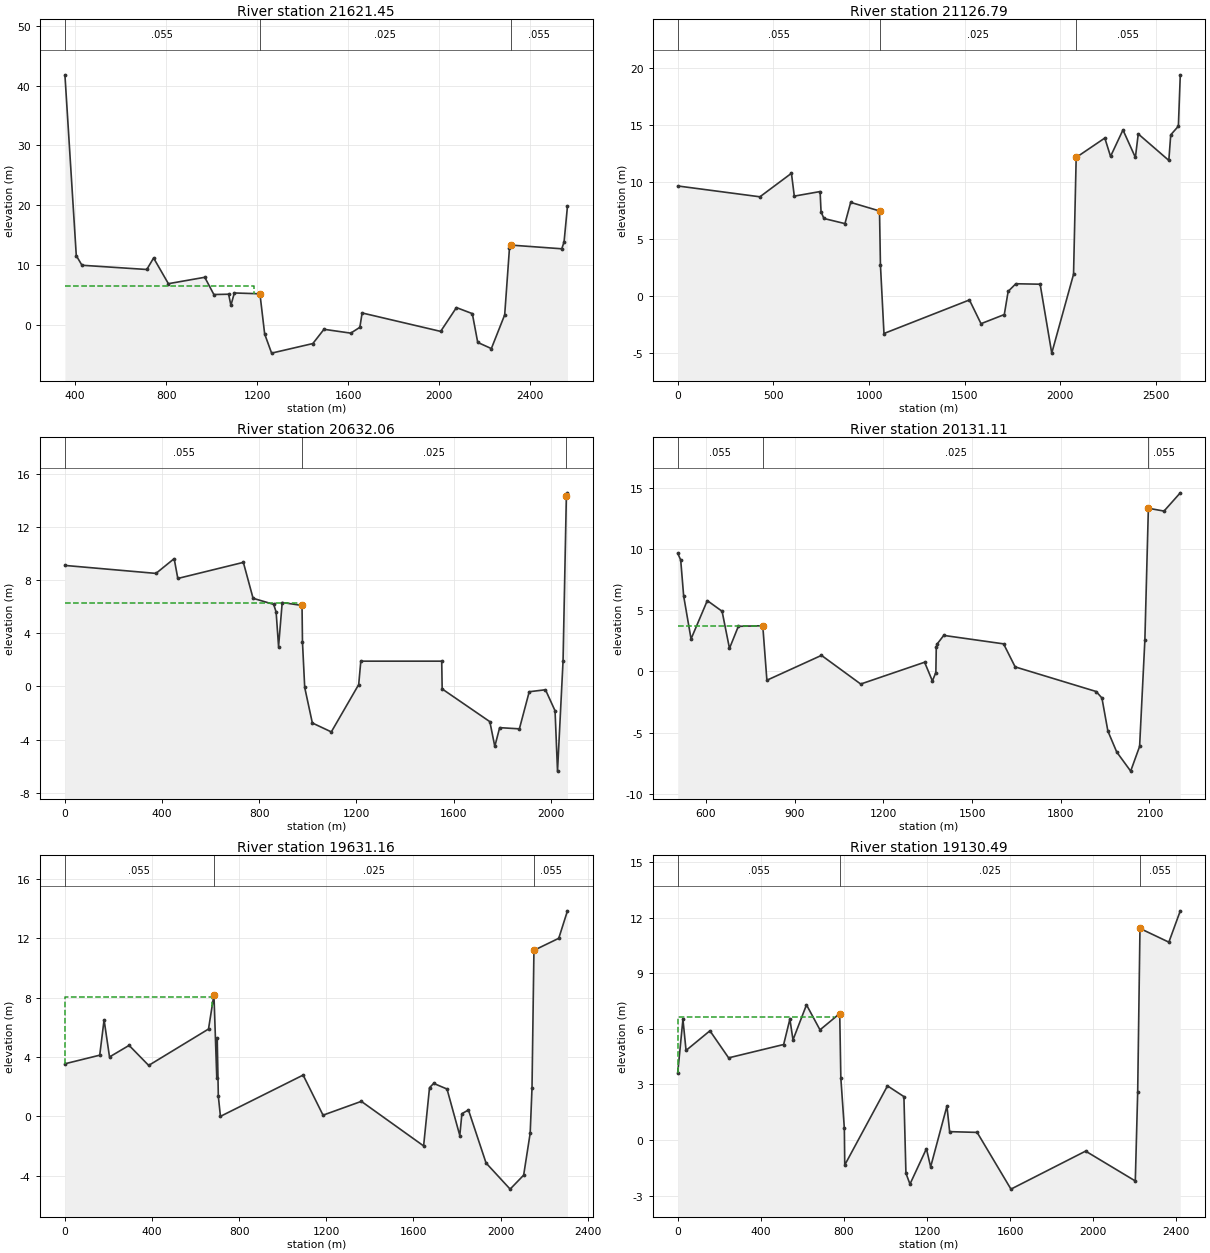
Type RM Length L Ch R = 1 ,21621.45,766.04,494.66,174.79
XS GIS Cut Line= 2
 373583.320066235906010.14302272374439.3020494875903973.13768515
#Sta/Elev= 30
  354.93   41.79  404.92   11.58  429.91    9.98  714.86    9.27  744.85   11.19
  809.84     6.9   969.8    7.97  1009.8    5.09 1074.78    5.14 1084.78    3.28
 1099.78    5.35 1212.37    5.21 1233.22   -1.51 1263.68    -4.7 1445.02    -3.1
 1493.91    -.72 1611.64   -1.36 1651.68    -.39 1661.66    2.01 2006.94   -1.07
  2076.3    2.91 2146.16     1.9 2169.93   -2.91 2229.83   -3.94 2288.49    1.69
 2309.53   12.87 2314.53   13.35 2539.49   12.73 2549.49   13.87 2564.48   19.83
#Mann= 3 , 0 , 0
  354.93    .055       0 1212.37    .025       0 2314.53    .055       0
#XS Ineff= 2 , 0
         1184.34    6.58
Permanent Ineff=
       F       F
Bank Sta=1212.37,2314.53
XS Rating Curve= 0 ,0
Exp/Cntr(USF)=0.5,0.3
Exp/Cntr=0.5,0.3

Type RM Length L Ch R = 1 ,21126.79,703.23,494.73,214.27
XS GIS Cut Line= 2
     374252.2828    5906438.1996 374807.811066495903870.93978839
#Sta/Elev= 30
       0    9.66  429.46    8.71  594.25   10.77  609.23    8.77  744.06    9.17
  749.05    7.39  764.03    6.81  873.89    6.36  903.86    8.22 1054.58    7.47
 1059.42    2.75 1077.89   -3.27 1524.56    -.33 1585.12   -2.41 1706.84   -1.61
 1726.93     .42 1767.15    1.09 1894.12    1.05 1954.84   -4.99 2068.74    1.92
 2082.54   12.16 2232.18   13.86 2262.14   12.25 2327.06   14.57 2391.97   12.16
 2406.95   14.22 2566.75    11.9 2576.74   14.14 2616.69    14.9 2626.67    19.4
#Mann= 3 , 0 , 0
       0    .055       0 1054.58    .025       0 2082.54    .055       0
Bank Sta=1054.58,2082.54
XS Rating Curve= 0 ,0
Exp/Cntr(USF)=0.5,0.3
Exp/Cntr=0.5,0.3

Type RM Length L Ch R = 1 ,20632.06,553.47,500.95,431.9
XS GIS Cut Line= 2
     374991.4999    5906501.4228 375097.32182344 5904435.6962342
#Sta/Elev= 30
       0     9.1  374.72     8.5  449.66    9.61  464.65    8.12  734.45    9.33
  774.42    6.63  859.36    6.17  869.35    5.59  879.34       3  894.33    6.31
  975.94    6.09  977.74    3.35  986.99    -.08 1018.44   -2.75 1096.46   -3.42
 1209.18     .14 1217.91     1.9  1550.9     1.9 1552.74    -.19    1749   -2.65
 1769.38   -4.51 1789.33    -3.1 1870.57   -3.19 1911.08     -.4 1977.94    -.25
 2017.36   -1.83 2027.52   -6.37 2050.31    1.92  2063.9    14.3 2068.45   14.56
#Mann= 3 , 0 , 0
       0    .055       0  975.94    .025       0  2063.9    .055       0
#XS Ineff= 2 , 0
          964.27    6.27
Permanent Ineff=
       F       F
Bank Sta=975.94,2063.9
XS Rating Curve= 0 ,0
Exp/Cntr(USF)=0.5,0.3
Exp/Cntr=0.5,0.3

Type RM Length L Ch R = 1 ,20131.11,499.39,499.95,502.28
XS GIS Cut Line= 2
375556.5160222625906016.66522887375572.9224601995904317.36490064
#Sta/Elev= 30
  504.81    9.63  514.81    9.09  524.81    6.15   549.8    2.64  604.78    5.77
  654.76     4.9  679.75    1.87  709.74    3.67  792.33    3.72  806.26    -.73
  990.83     1.3 1123.52   -1.04 1339.61     .74 1365.88    -.79 1377.65     -.1
 1379.04    1.95 1381.74    2.22 1404.28    2.93 1606.65    2.24 1645.75     .36
 1919.66   -1.65  1939.2   -2.18 1959.34   -4.88 1989.26   -6.59  2036.4   -8.15
 2066.62   -6.13 2084.43    2.55 2096.26   13.31  2149.2   13.08 2204.18   14.57
#Mann= 3 , 0 , 0
  504.81    .055       0  792.33    .025       0 2096.26    .055       0
#XS Ineff= 2 , 0
          784.57    3.72
Permanent Ineff=
       F       F
Bank Sta=792.33,2096.26
XS Rating Curve= 0 ,0
Exp/Cntr(USF)=0.5,0.3
Exp/Cntr=0.5,0.3

Type RM Length L Ch R = 1 ,19631.16,500,500.67,502.47
XS GIS Cut Line= 2
     376050.8276    5906544.7603376073.0993071895904237.96505875
#Sta/Elev= 30
       0    3.54  159.79    4.12  179.76     6.5  204.73       4  294.61    4.78
  384.49    3.43  659.12    5.88  684.08    8.19  697.08    2.61  699.15    5.25
  704.25    1.35  713.91       0 1093.54    2.78 1184.89     .08 1360.68    1.01
 1646.57   -1.99 1673.64    1.93 1692.82    2.22    1754    1.84 1812.65   -1.29
 1822.32     .18 1852.44     .43 1933.19   -3.14 2043.73    -4.9 2105.81   -3.96
  2135.8   -1.13 2144.17    1.91 2153.02   11.18 2266.97   11.99 2306.91   13.84
#Mann= 3 , 0 , 0
       0    .055       0  684.08    .025       0 2153.02    .055       0
#XS Ineff= 2 , 0
          674.99    8.07
Permanent Ineff=
       F       F
Bank Sta=684.08,2153.02
XS Rating Curve= 0 ,0
Exp/Cntr(USF)=0.5,0.3
Exp/Cntr=0.5,0.3

Type RM Length L Ch R = 1 ,19130.49,499.21,500.44,499.99
XS GIS Cut Line= 2
     376550.8517    5906544.6705376574.2087307785904125.46404562
#Sta/Elev= 30
       0    3.64   24.99    6.51   39.99    4.83  154.96    5.89  244.93    4.43
  509.85    5.15  539.85    6.52  554.84     5.4  619.82    7.29  684.81    5.94
  779.78    6.82  785.18    3.34  802.05     .62  803.99   -1.35 1009.71    2.92
 1088.83    2.34 1098.51   -1.79 1117.95   -2.38 1197.14    -.47 1217.48   -1.45
 1295.93    1.83 1308.92     .45 1441.29     .41 1604.12   -2.65 1963.51     -.6
 2202.71   -2.21 2214.22    2.57 2225.27   11.41 2364.33   10.67 2419.31   12.36
#Mann= 3 , 0 , 0
       0    .055       0  779.78    .025       0 2225.27    .055       0
#XS Ineff= 2 , 0
           754.4    6.63
Permanent Ineff=
       F       F
Bank Sta=779.78,2225.27
XS Rating Curve= 0 ,0
Exp/Cntr(USF)=0.5,0.3
Exp/Cntr=0.5,0.3

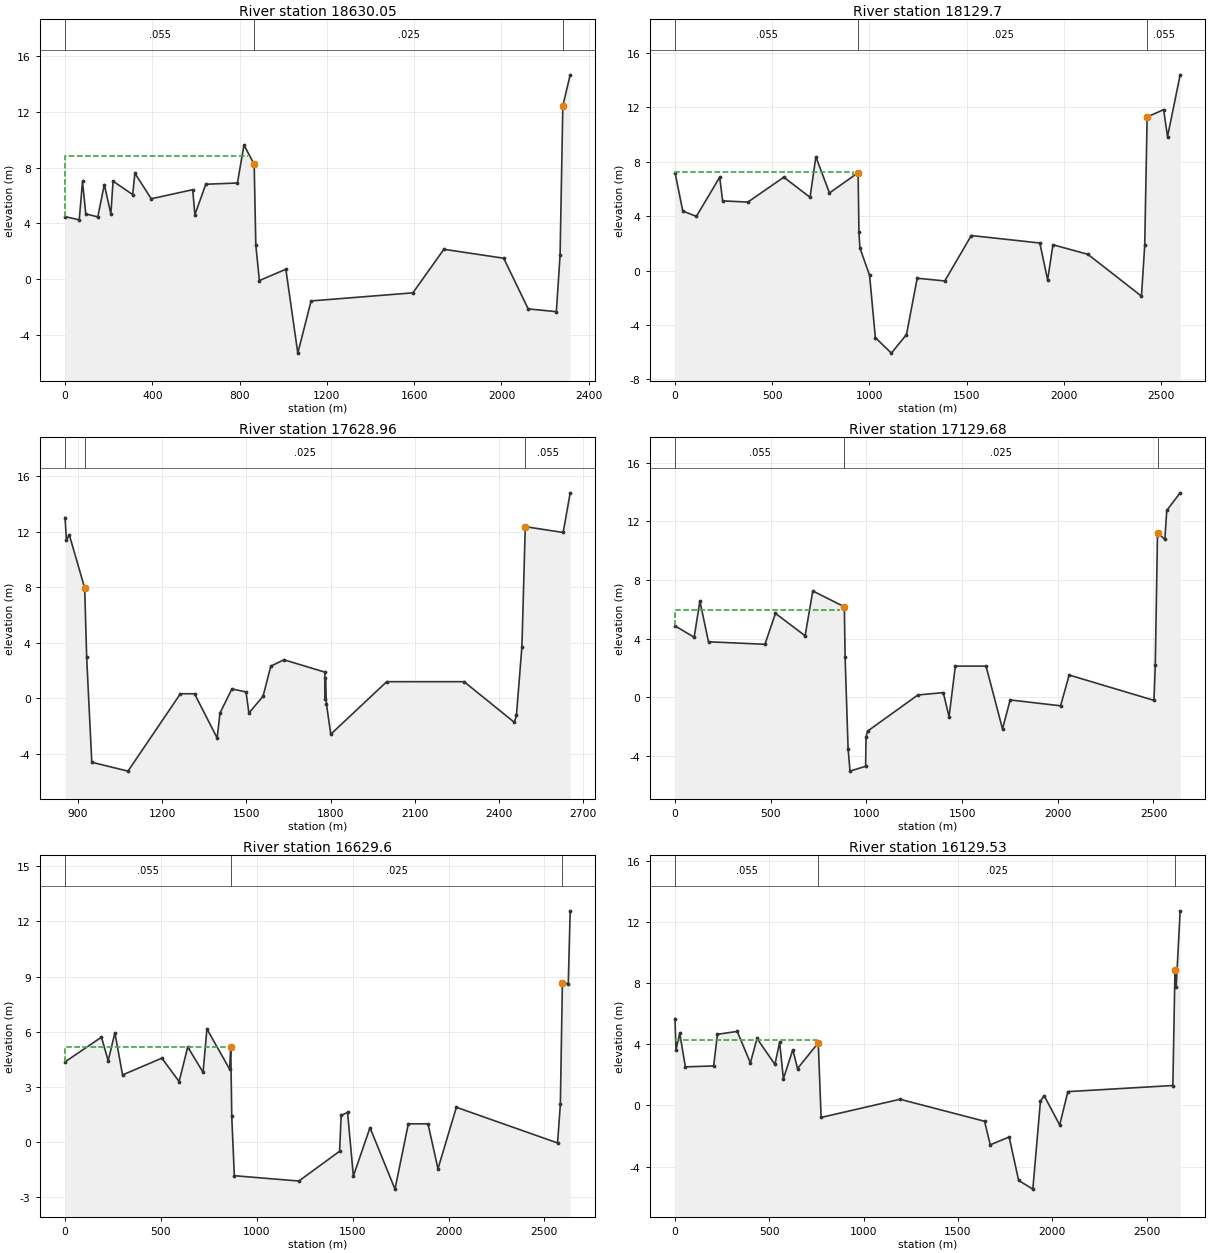
Type RM Length L Ch R = 1 ,18630.05,499.27,500.35,499.48
XS GIS Cut Line= 2
     377049.9631    5906554.4619377072.3123497025904239.62897053
#Sta/Elev= 30
       0    4.48      65    4.25      80       7      95    4.68     150    4.46
     180    6.78  209.99    4.67  219.99    7.02  309.99    6.06  319.99    7.59
  394.99    5.76  584.99    6.41  594.99    4.62  644.98     6.8  789.98    6.89
  819.98    9.61  866.73    8.23  874.22    2.44  890.58     -.1 1011.88     .71
 1066.66    -5.3 1127.61   -1.56 1594.08    -.98 1735.96    2.14 2010.17     1.5
 2122.49   -2.13 2251.54   -2.33 2268.63    1.73  2281.2   12.41 2314.94   14.64
#Mann= 3 , 0 , 0
       0    .055       0  866.73    .025       0  2281.2    .055       0
#XS Ineff= 2 , 0
          836.64    8.81
Permanent Ineff=
       F       F
Bank Sta=866.73,2281.2
XS Rating Curve= 0 ,0
Exp/Cntr(USF)=0.5,0.3
Exp/Cntr=0.5,0.3

Type RM Length L Ch R = 1 ,18129.7 ,500.09,500.74,500.29
XS GIS Cut Line= 2
     377548.4327    5906630.7123377573.5207013765904032.21740899
#Sta/Elev= 30
       0    7.21   39.98    4.38  109.94    3.99  229.88    6.87  244.87    5.13
   374.8    5.04   559.7    6.87  694.63    5.39  724.61    8.37  794.57    5.71
  941.89     7.2  946.23    2.82  950.89    1.68 1000.93    -.35 1030.62   -4.93
 1112.95   -6.07 1190.82    -4.7 1245.83    -.56 1387.73    -.76 1524.18    2.58
 1876.64    2.03 1916.79    -.69 1944.14     1.9 2123.73     1.2 2399.57   -1.88
  2416.3    1.85  2428.7    11.3 2513.65   11.84 2533.64    9.85 2598.61    14.4
#Mann= 3 , 0 , 0
       0    .055       0  941.89    .025       0  2428.7    .055       0
#XS Ineff= 2 , 0
          915.48    7.27
Permanent Ineff=
       F       F
Bank Sta=941.89,2428.7
XS Rating Curve= 0 ,0
Exp/Cntr(USF)=0.5,0.3
Exp/Cntr=0.5,0.3

Type RM Length L Ch R = 1 ,17628.96,499.07,499.28,499.22
XS GIS Cut Line= 2
 378056.545060315905792.88892357378073.9129169475903994.00978334
#Sta/Elev= 30
   854.5   13.04   859.5   11.39  869.49    11.8  924.46    7.95  931.49    2.95
  949.78   -4.61 1078.59   -5.25 1265.31     .33 1315.65     .33 1396.14   -2.86
 1406.32   -1.06 1448.73     .68 1499.06     .46 1509.21   -1.06 1559.67     .15
 1587.24    2.32 1634.05    2.78 1779.93    1.89 1780.46    -.04 1781.81    1.48
 1785.37     -.4 1800.81   -2.59 2000.01     1.2 2275.54     1.2 2454.56   -1.73
 2461.97   -1.23 2481.53    3.72  2493.5   12.38 2628.47   11.96 2653.46   14.82
#Mann= 3 , 0 , 0
   854.5    .055       0  924.46    .025       0  2493.5    .055       0
Bank Sta=924.46,2493.5
XS Rating Curve= 0 ,0
Exp/Cntr(USF)=0.5,0.3
Exp/Cntr=0.5,0.3

Type RM Length L Ch R = 1 ,17129.68,501.79,500.08,500.22
XS GIS Cut Line= 2
     378547.0115    5906676.9166378572.495428576 5904037.4062686
#Sta/Elev= 30
       0    4.87   99.99    4.09  129.98    6.56  174.98    3.78  469.93    3.61
  524.93    5.72  679.91    4.19   719.9    7.25  884.88    6.17   888.8    2.73
  904.45   -3.53  914.46   -5.05  996.04   -4.72  998.08   -2.74  1006.1   -2.32
 1269.23     .15 1401.87     .31 1431.96   -1.34  1464.9    2.12 1625.25    2.12
 1711.34   -2.17 1751.29    -.19 2014.72    -.59 2059.67    1.51  2502.9    -.22
 2509.63    2.18 2521.26   11.22 2559.65   10.77 2569.65   12.75 2639.63   13.95
#Mann= 3 , 0 , 0
       0    .055       0  884.88    .025       0 2521.26    .055       0
#XS Ineff= 2 , 0
          862.73    5.95
Permanent Ineff=
       F       F
Bank Sta=884.88,2521.26
XS Rating Curve= 0 ,0
Exp/Cntr(USF)=0.5,0.3
Exp/Cntr=0.5,0.3

Type RM Length L Ch R = 1 ,16629.6 ,502.37,500.06,500.22
XS GIS Cut Line= 2
     379046.7455     5906706.877379072.1816065765904072.32763726
#Sta/Elev= 30
       0    4.37  189.98    5.71  224.97    4.43  259.97    5.95  299.96    3.66
  504.94    4.57  594.93     3.3  639.92    5.18  719.91     3.8  739.91    6.16
  858.41    3.97  864.22     5.2  869.48    1.41   882.9   -1.82 1219.44   -2.11
 1431.91    -.49 1440.17    1.46 1473.51    1.62 1503.75   -1.84 1590.51     .79
 1720.87   -2.55  1790.4       1 1892.95       1 1945.19   -1.44 2040.99     1.9
 2568.74    -.04 2583.39    2.06 2593.96    8.65 2624.67    8.62 2634.67   12.58
#Mann= 3 , 0 , 0
       0    .055       0  864.22    .025       0 2593.96    .055       0
#XS Ineff= 2 , 0
          864.07    5.15
Permanent Ineff=
       F       F
Bank Sta=864.22,2593.96
XS Rating Curve= 0 ,0
Exp/Cntr(USF)=0.5,0.3
Exp/Cntr=0.5,0.3

Type RM Length L Ch R = 1 ,16129.53,375.92,507.29,629.41
XS GIS Cut Line= 2
     379546.2263    5906763.0699379572.0767816545904085.59561471
#Sta/Elev= 30
       0    5.68       5    3.63   24.98    4.72   54.95    2.52  204.82    2.58
   224.8    4.65  329.71    4.84  399.64    2.78  434.61    4.38  529.53    2.68
  554.51    4.13  574.49    1.74  624.44    3.64  649.42    2.41  759.32    4.09
  774.41    -.79 1192.63      .4 1640.88   -1.04 1670.98   -2.58 1771.25   -2.07
  1821.4   -4.91  1896.7   -5.48 1936.96     .27 1956.72     .63 2039.01   -1.28
 2082.48      .9 2638.91     1.3 2650.15    8.85 2656.64    7.77 2677.61   12.73
#Mann= 3 , 0 , 0
       0    .055       0  759.32    .025       0 2650.15    .055       0
#XS Ineff= 2 , 0
          752.13    4.29
Permanent Ineff=
       F       F
Bank Sta=759.32,2650.15
XS Rating Curve= 0 ,0
Exp/Cntr(USF)=0.5,0.3
Exp/Cntr=0.5,0.3

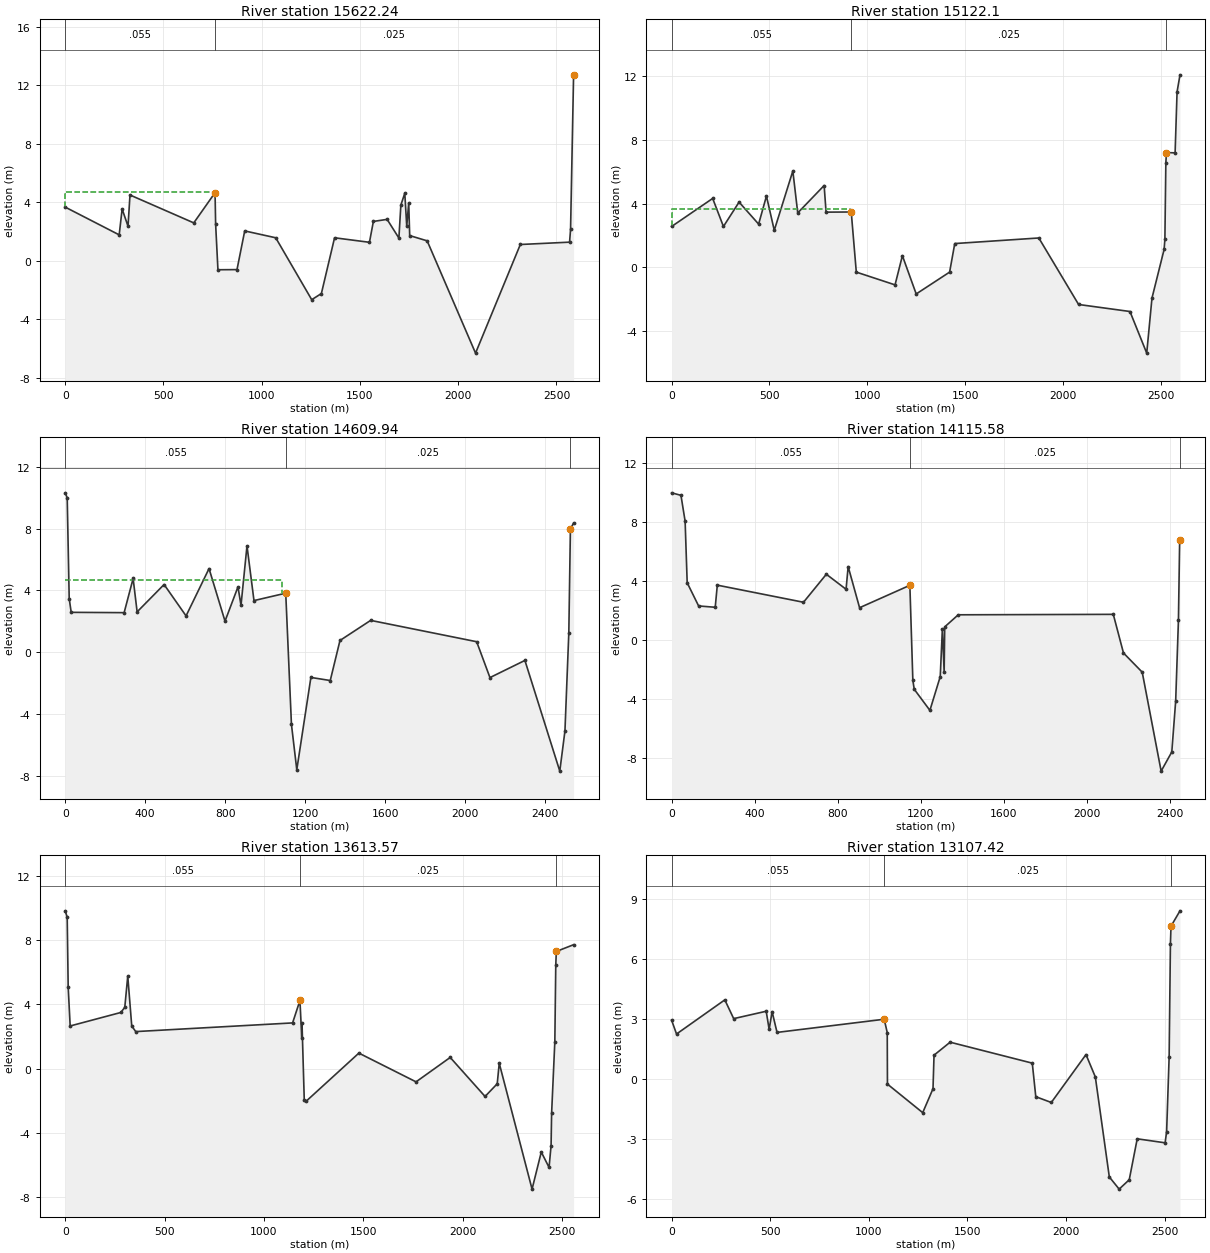
Type RM Length L Ch R = 1 ,15622.24,502.11,500.14,501.46
XS GIS Cut Line= 2
     379896.7436    5906799.3701380146.0105672965904224.39180596
#Sta/Elev= 30
       0    3.67  274.68    1.77  289.66    3.54  319.63    2.36  329.62     4.5
  654.24    2.59  762.51    4.66  765.46     2.5  777.19    -.62  874.17    -.61
  913.44    2.04  1071.2    1.57 1254.41   -2.67 1303.56   -2.25 1370.68    1.57
 1548.21    1.26 1568.19    2.69 1638.11    2.83 1698.04    1.55 1708.03    3.81
    1728    4.62 1737.99    2.36 1747.98    3.95 1752.97    1.72 1841.84    1.36
 2088.04   -6.33 2315.95    1.11 2566.55    1.27 2571.61    2.14 2587.01   12.73
#Mann= 3 , 0 , 0
       0    .055       0  762.51    .025       0 2587.01               0
#XS Ineff= 2 , 0
          750.43     4.7
Permanent Ineff=
       F       F
Bank Sta=762.51,2587.01
XS Rating Curve= 0 ,0
Exp/Cntr(USF)=0.5,0.3
Exp/Cntr=0.5,0.3

Type RM Length L Ch R = 1 ,15122.1 ,308.62,512.16,677.55
XS GIS Cut Line= 2
     380394.3265    5906848.4833380644.543516056 5904263.6917654
#Sta/Elev= 30
       0    2.56  209.75    4.32  264.68    2.56  344.59    4.09  444.47    2.71
  484.42    4.47  524.37    2.32  619.26    6.04  644.23    3.41  779.06    5.13
  789.05    3.46  917.53    3.47  943.42     -.3 1141.32    -1.1 1178.85     .73
 1249.38   -1.67 1420.06     -.3 1446.36    1.49  1875.7    1.84 2078.89   -2.33
  2341.3   -2.77 2426.93   -5.38 2453.74   -1.93  2515.7    1.12 2519.71    1.75
  2524.6    6.55 2527.68    7.19 2571.91    7.18  2581.9      11 2596.88   12.07
#Mann= 3 , 0 , 0
       0    .055       0  917.53    .025       0 2527.68    .055       0
#XS Ineff= 2 , 0
          908.68    3.67
Permanent Ineff=
       F       F
Bank Sta=917.53,2527.68
XS Rating Curve= 0 ,0
Exp/Cntr(USF)=0.5,0.3
Exp/Cntr=0.5,0.3

Type RM Length L Ch R = 1 ,14609.94,493.61,494.36,496.64
XS GIS Cut Line= 2
     380673.5607    5906880.9974381236.1318359115904402.35563074
#Sta/Elev= 30
       0   10.31    9.99    9.99   19.97    3.47   29.96    2.58  294.62    2.56
  339.56    4.77  359.53    2.61  494.36    4.38  604.21    2.35  719.07    5.41
  798.96    2.01  863.88    4.23  878.86    3.03  908.82    6.88  943.77    3.34
 1102.53    3.82 1131.08   -4.67 1157.77    -7.6 1228.28   -1.63 1325.07   -1.83
 1373.71     .76 1527.16    2.06  2057.1     .68 2123.53   -1.64 2298.28    -.53
 2472.66   -7.69 2498.49   -5.09  2517.8    1.25 2525.77    7.96 2541.69    8.36
#Mann= 3 , 0 , 0
       0    .055       0 1102.53    .025       0 2525.77    .055       0
#XS Ineff= 2 , 0
         1082.25    4.67
Permanent Ineff=
       F       F
Bank Sta=1102.53,2525.77
XS Rating Curve= 0 ,0
Exp/Cntr(USF)=0.5,0.3
Exp/Cntr=0.5,0.3

Type RM Length L Ch R = 1 ,14115.58,502.3,502.01,505.04
XS GIS Cut Line= 2
     381159.4143     5906970.222381701.0929724185904583.63085306
#Sta/Elev= 30
       0    9.98   44.99    9.81   64.99    8.06   74.98    3.88  129.97    2.31
  209.95    2.22  219.95    3.72  634.86    2.56  744.83    4.46  839.81    3.44
  849.81    4.98   904.8    2.19 1146.91    3.71 1161.28   -2.74    1168   -3.34
 1243.36   -4.77 1293.14   -2.48 1303.42     .76 1311.98   -2.16 1314.64     .89
 1379.81    1.71 2126.17    1.74 2175.17    -.88 2265.42   -2.18 2356.49   -8.89
 2407.79   -7.59 2426.51   -4.13 2439.79    1.35  2445.7    6.78 2447.27    6.86
#Mann= 3 , 0 , 0
       0    .055       0 1146.91    .025       0  2445.7    .055       0
#XS Ineff= 2 , 0
Permanent Ineff=
       F       F
Bank Sta=1146.91,2445.7
XS Rating Curve= 0 ,0
Exp/Cntr(USF)=0.5,0.3
Exp/Cntr=0.5,0.3

Type RM Length L Ch R = 1 ,13613.57,343.57,506.15,654.42
XS GIS Cut Line= 2
     381642.5406    5907109.1877382208.6682219365904614.87647494
#Sta/Elev= 30
       0    9.83    9.99    9.43   14.99    5.07   24.98    2.66  279.75     3.5
  299.74    3.82  314.72    5.77  334.71    2.66  354.69    2.31 1143.99    2.85
 1181.01    4.25    1190    1.94 1191.36    2.85 1202.68   -1.94 1212.78   -2.02
 1477.47     .97 1765.13    -.82 1936.96      .7 2112.32   -1.73 2173.55    -.94
 2183.64     .34 2348.79    -7.5 2395.23   -5.19 2434.35   -6.15 2444.49   -4.79
 2447.13   -2.79  2463.4    1.69 2468.09    6.45 2470.88     7.3 2557.75    7.72
#Mann= 3 , 0 , 0
       0    .055       0 1181.01    .025       0 2470.88    .055       0
#XS Ineff= 2 , 0
Permanent Ineff=
       F       F
Bank Sta=1181.01,2470.88
XS Rating Curve= 0 ,0
Exp/Cntr(USF)=0.5,0.3
Exp/Cntr=0.5,0.3

Type RM Length L Ch R = 1 ,13107.42,506.78,506.93,512.59
XS GIS Cut Line= 2
     381956.6837    5907185.7673382772.4212553455904739.81756802
#Sta/Elev= 30
       0    2.95   24.98    2.26  269.83    3.97   314.8    3.03   479.7     3.4
  494.69    2.49  509.68    3.38  534.67    2.34 1078.23       3 1093.61    2.33
 1094.65    -.25 1273.51   -1.68 1325.72    -.48 1330.92     1.2 1412.55    1.85
 1829.23      .8 1846.97    -.88 1925.68   -1.17 2101.66    1.23 2148.97     .11
 2219.94    -4.9 2269.78   -5.51 2320.98   -5.04 2361.43   -2.99 2502.92   -3.19
 2510.53   -2.64 2523.35    1.12 2529.88    6.79 2532.82    7.66 2578.39    8.43
#Mann= 3 , 0 , 0
       0    .055       0 1078.23    .025       0 2532.82    .055       0
#XS Ineff= 2 , 0
Permanent Ineff=
       F       F
Bank Sta=1078.23,2532.82
XS Rating Curve= 0 ,0
Exp/Cntr(USF)=0.5,0.3
Exp/Cntr=0.5,0.3

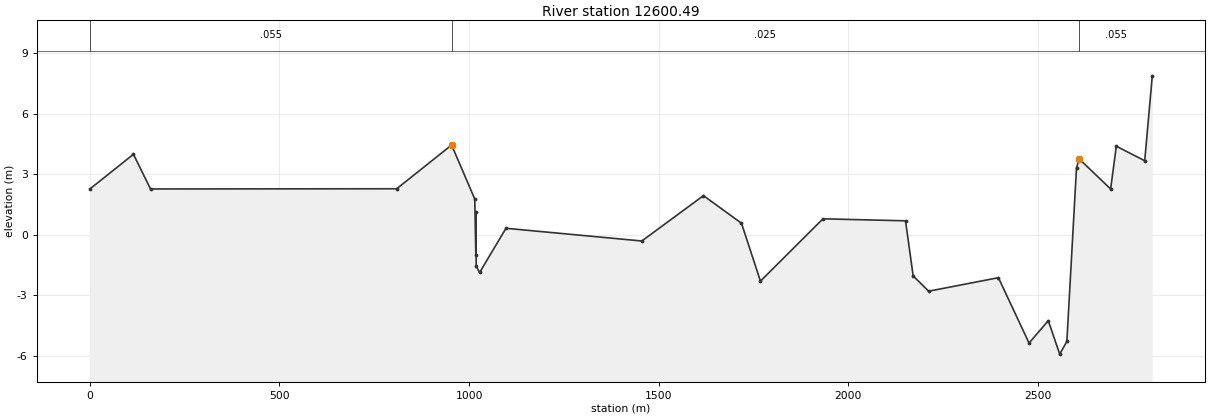
Type RM Length L Ch R = 1 ,12600.49,374.32,499.98,635.01
XS GIS Cut Line= 2
     382438.0603    5907344.0193383324.5546234145904685.90897557
#Sta/Elev= 30
       0    2.28  114.88       4  159.83    2.28  809.15    2.29     954    4.46
 1015.08    1.78  1017.9      -1  1018.2    1.13 1018.85   -1.55 1027.93   -1.86
  1097.4     .33  1455.7     -.3  1618.3    1.95 1718.56     .58 1768.55   -2.29
 1933.41      .8 2151.17      .7 2171.34   -2.03  2212.2   -2.79 2396.18   -2.12
 2477.01   -5.36 2527.74   -4.25 2557.87   -5.91 2576.72   -5.28 2602.17    3.33
 2609.16    3.77 2692.17    2.28 2707.16     4.4 2782.08    3.68 2802.06    7.89
#Mann= 3 , 0 , 0
       0    .055       0     954    .025       0 2609.16    .055       0
#XS Ineff= 2 , 0
Permanent Ineff=
       F       F
Bank Sta=954,2609.16
XS Rating Curve= 0 ,0
Exp/Cntr(USF)=0.5,0.3
Exp/Cntr=0.5,0.3