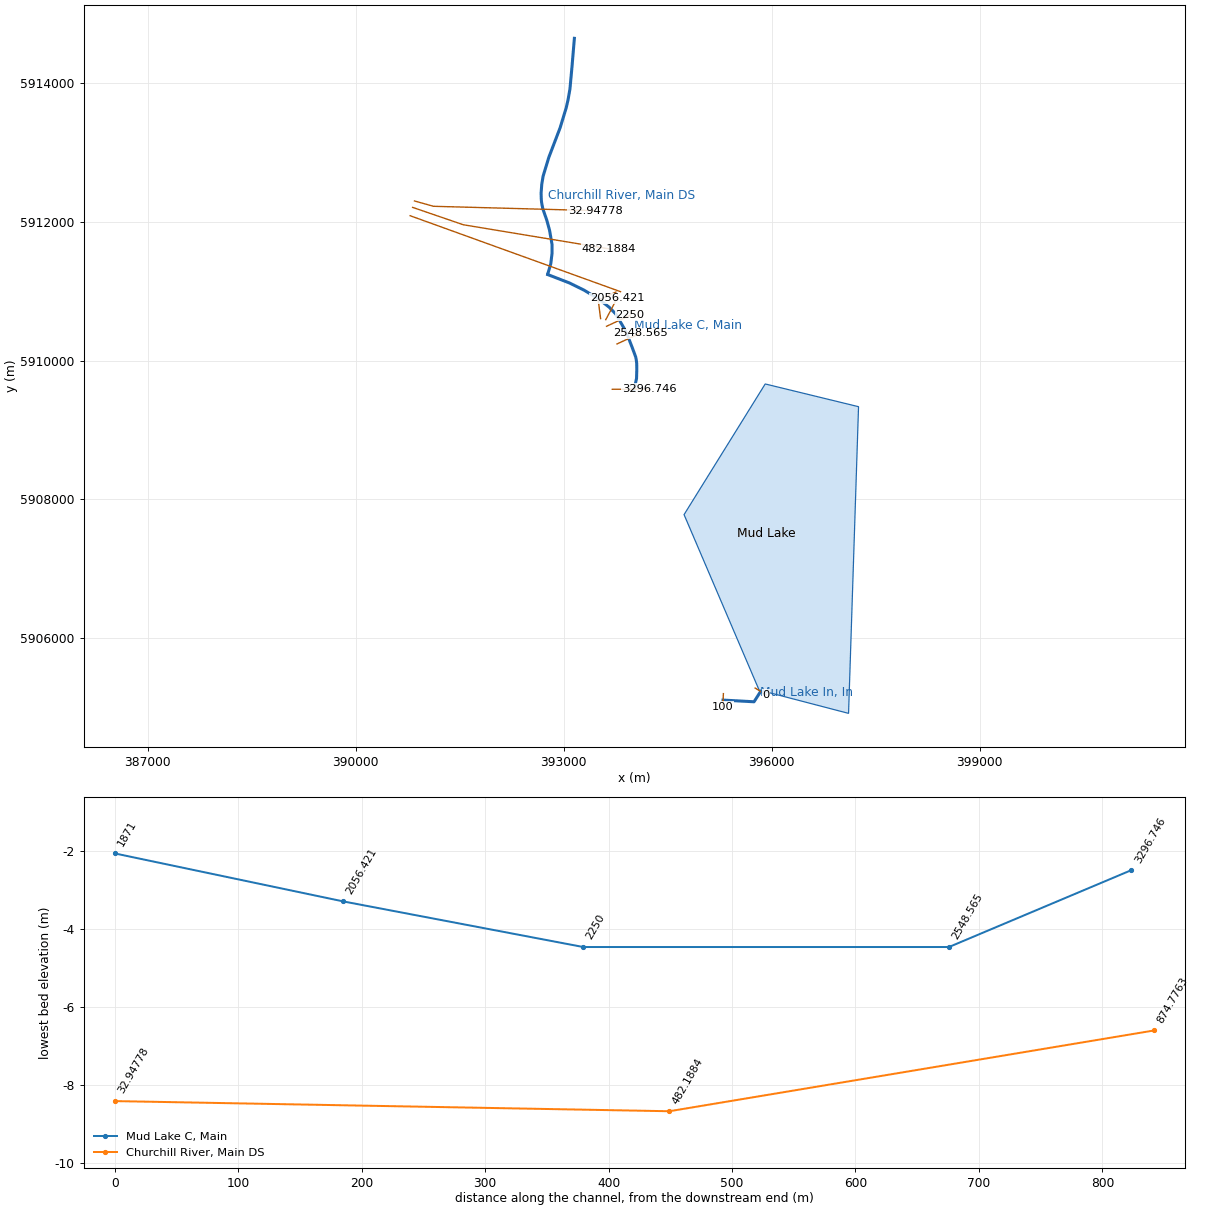
HEC-RAS study Churchill_Mapping.prj: Churchill River Flood Risk Mapping

--- Churchill_Mapping.g33 (geometry) --- (continued)

River Reach=Mud Lake C      ,Main
Reach XY= 30
394014.3860305595909575.33087705     394051.6425    5909745.1736
     394051.9867    5909758.4188     394052.5071    5909778.4379
     394052.5889    5909781.5878     394052.6678    5909784.6198
     394053.6362    5909821.8776     394054.0266    5909836.9014
     394054.0332    5909837.1526     394054.1982    5909843.5002
     394054.8567    5909868.8366     394054.0629    5909957.7367
     394046.9191    5910017.2681     394038.9816    5910054.5744
     393988.9753     5910190.306     393922.3001    5910361.7563
     393869.1188    5910472.0878      393844.398    5910514.7565
     393839.2588    5910523.6271     393833.7857    5910533.0736
      393829.723    5910540.0861     393809.8633    5910574.3645
     393771.3947    5910640.7622     393753.2311    5910672.1132
     393688.1051    5910739.0948      393658.047    5910770.0092
     393503.2655    5910891.7178       393296.89    5911016.0722
      393085.223    5911120.5828392769.8948848085911242.63821614

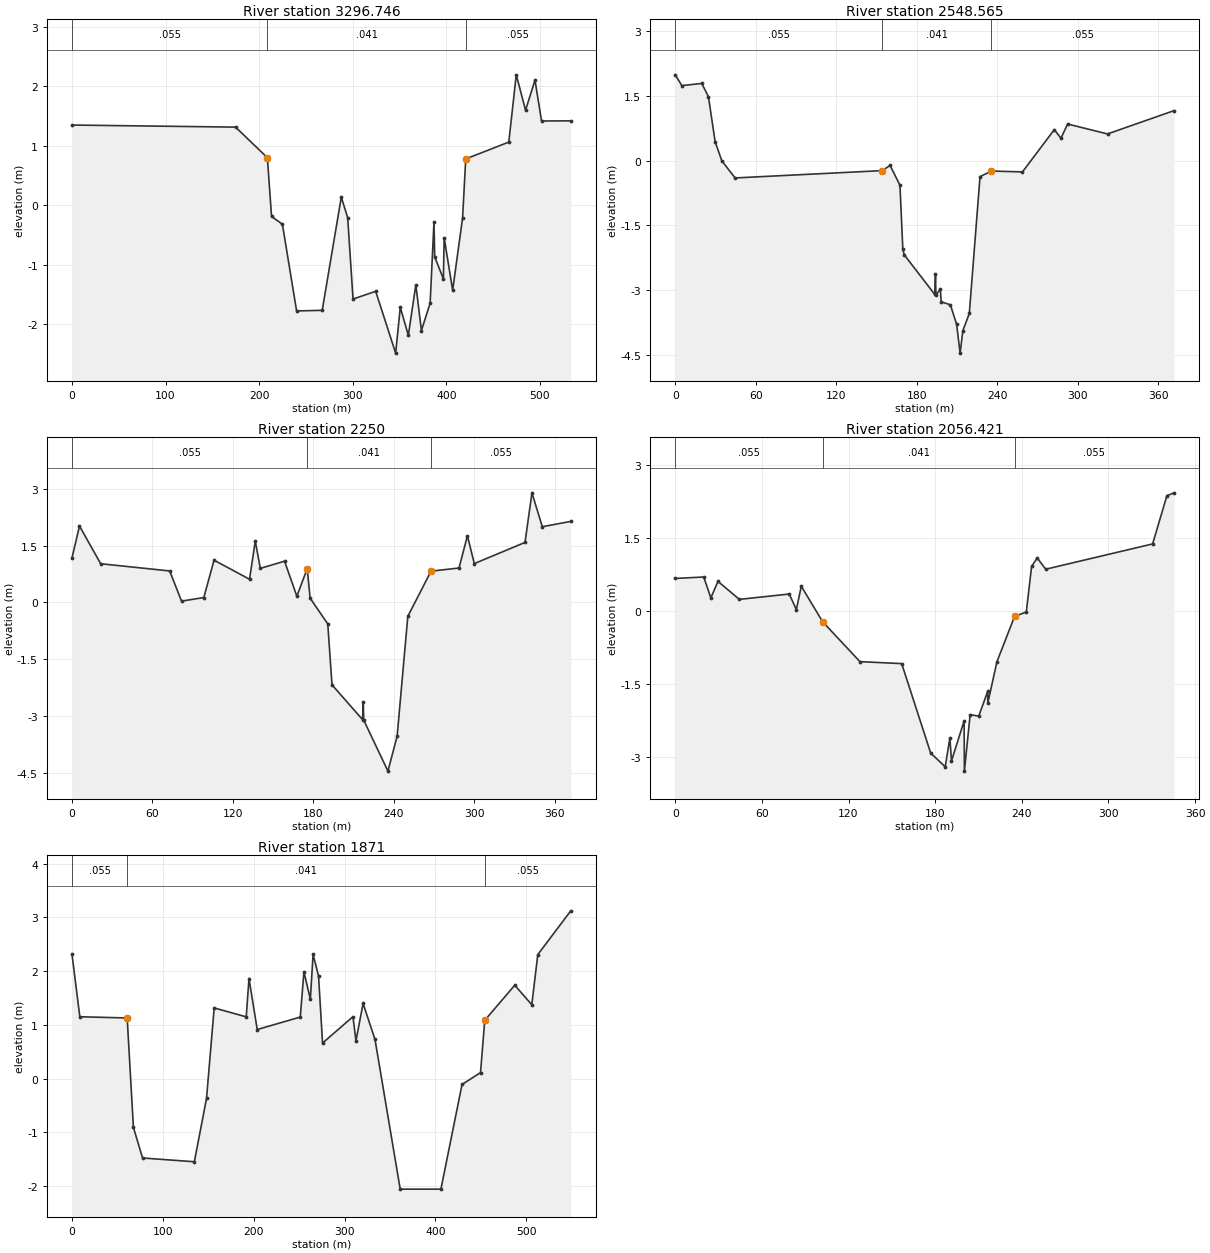
Type RM Length L Ch R = 1 ,3296.746,12.53,147.7,58.22
XS GIS Cut Line= 2
393701.6900129385909587.60951648     394234.7472    5909590.8934
#Sta/Elev= 30
       0   1.348 174.813   1.313 208.814    .799 213.275    -.19 224.865    -.32
 240.055   -1.78 267.425   -1.77 287.816    .135  294.63    -.21  300.36   -1.58
  324.56   -1.45  345.91   -2.49  350.86   -1.72  359.47   -2.19  367.48   -1.34
  373.44   -2.11  382.76   -1.65  386.89    -.28  387.62    -.87  396.93   -1.24
  397.75    -.55  406.83   -1.43  417.42    -.22 420.818    .778 466.819   1.061
 474.819   2.193 484.724   1.598 494.819   2.104  501.82   1.416 533.067   1.419
#Mann= 3 , 0 , 0
       0    .055       0 208.814    .041       0 420.818    .055       0
Bank Sta=208.814,420.818
XS Rating Curve= 0 ,0
Exp/Cntr=0.3,0.1

Type RM Length L Ch R = 1 ,2548.565,296.22,296.22,296.22
XS GIS Cut Line= 2
     393770.4026    5910241.7697      394107.747    5910398.1388
#Sta/Elev= 30
       0    1.99    4.96    1.74   19.83    1.79   24.79    1.48   29.75     .44
    34.7       0   44.62     -.4  154.25    -.23  160.18    -.11  167.53    -.57
  169.67   -2.05  170.69   -2.18  193.48    -3.1  194.01   -2.63   194.3   -3.11
  197.66   -2.98  198.24   -3.27  205.12   -3.34  209.75   -3.79  212.38   -4.46
  214.41   -3.94  219.23   -3.54  227.21    -.37  235.68    -.24  258.85    -.26
  282.59     .72  287.54     .52   292.5     .85  322.25     .62  371.82    1.16
#Mann= 3 , 0 , 0
       0    .055       0  154.25    .041       0  235.68    .055       0
Bank Sta=154.25,235.68
XS Rating Curve= 0 ,0
Exp/Cntr=0.3,0.1

Type RM Length L Ch R = 1 ,2250    ,194.53,194.53,194.53
XS GIS Cut Line= 2
393618.4152793485910496.16980559393955.7596793485910652.53890559
#Sta/Elev= 30
       0   1.173   5.604   2.015    21.4   1.019  72.839    .828  81.657    .031
  98.277    .126 105.905   1.112 132.358    .609 136.626   1.618 140.392    .896
 158.467   1.086 167.629     .16 175.344     .89 177.549    .107  190.67    -.57
  193.83   -2.18  216.62    -3.1  217.15   -2.63  217.44   -3.11  235.52   -4.46
  242.37   -3.54  250.35    -.37 267.669    .823 288.506    .906 294.781   1.759
 299.894   1.022 337.708   1.582  342.88   2.892 350.595   1.997 371.823   2.137
#Mann= 3 , 0 , 0
       0    .055       0 175.344    .041       0 267.669    .055       0
Bank Sta=175.344,267.669
XS Rating Curve= 0 ,0
Exp/Cntr=0.3,0.1

Type RM Length L Ch R = 1 ,2056.421,185,185,185
XS GIS Cut Line= 2
393607.8293380855910591.91434684393770.8354096455910900.42248424
#Sta/Elev= 30
       0     .67   19.74      .7   24.67     .27   29.61     .61   44.41     .24
   78.95     .35   83.88     .03    87.3     .51  102.08    -.22  127.93   -1.04
  156.83   -1.08  176.91   -2.92  186.96    -3.2   190.2   -2.61  191.31   -3.08
  200.04   -2.26  200.24   -3.29  204.23   -2.13  210.18   -2.16  216.39   -1.65
  216.46   -1.89  222.79   -1.04  235.01    -.11  243.11    -.02   246.8     .92
  250.68    1.09  256.58     .86  330.59    1.38  340.46    2.37   345.4    2.43
#Mann= 3 , 0 , 0
       0    .055       0  102.08    .041       0  235.01    .055       0
Bank Sta=102.08,235.01
XS Rating Curve= 0 ,0
Exp/Cntr=0.3,0.1

Type RM Length L Ch R = 1 ,1871    ,0,0,0
XS GIS Cut Line= 3
393532.8903050245910607.23035359393498.9762897065910872.52547194
393754.4351270725910991.04652588
#Sta/Elev= 30
       0   2.316   8.635   1.151   60.76   1.128  67.622    -.91  77.692   -1.48
 134.692   -1.55 148.112    -.37 156.533   1.315 191.818   1.149 194.842   1.863
 203.916    .913 251.298   1.145 255.315   1.988 262.388   1.478 265.412   2.312
 271.382   1.913  275.84    .661 309.279   1.152 312.623    .702 320.426   1.398
 333.553    .729 361.305   -2.06 406.115   -2.06 429.385    -.11 449.723     .11
 454.334   1.084 487.406   1.738 506.147   1.375 512.761   2.309 549.068   3.124
#Mann= 3 , 0 , 0
       0    .055       0   60.76    .041       0 454.334    .055       0
Bank Sta=60.76,454.334
XS Rating Curve= 0 ,0
Exp/Cntr=0.3,0.1

River Reach=Mud Lake In     ,In
Reach XY= 3
395299.2126349185905104.54782489395746.2383976745905080.16460147
395840.9106316165905228.34722851
Reach Downstream Storage Area=Mud Lake

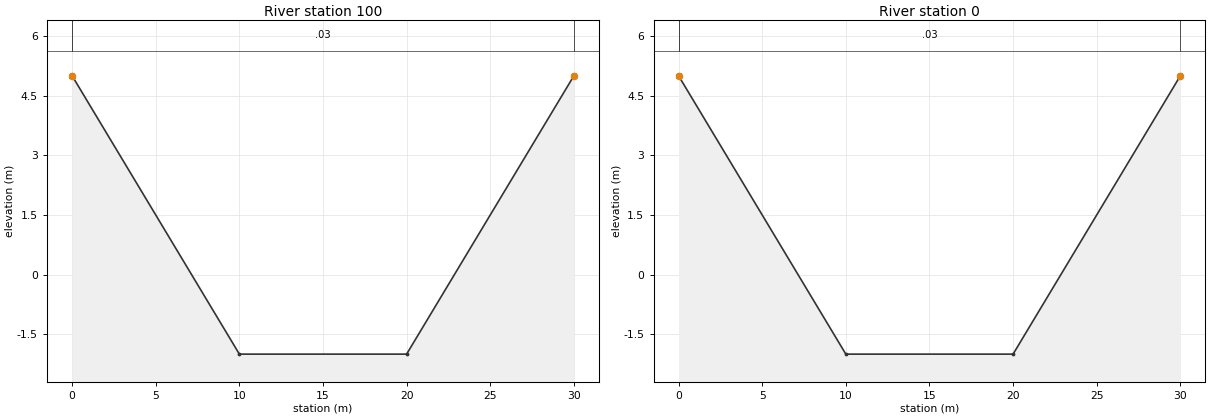
Type RM Length L Ch R = 1 ,100     ,100,100,100
XS GIS Cut Line= 5
395304.3067021795905197.93905802395304.3067021795905197.93905802
395299.2126349185905104.54782489395294.1185676575905011.15659176
395294.1185676575905011.15659176
#Sta/Elev= 4
       0       5      10      -2      20      -2      30       5
#Mann= 3 , 0 , 0
       0     .03       0       0     .03       0      30     .03       0
Bank Sta=0,30
XS Rating Curve= 0 ,0
Exp/Cntr=0.3,0.1

Type RM Length L Ch R = 1 ,0       ,0,0,0
XS GIS Cut Line= 5
 395762.093200675905278.70280939 395762.093200675905278.70280939
395840.9106316165905228.34722851395919.7280625625905177.99164763
395919.7280625625905177.99164763
#Sta/Elev= 4
       0       5      10      -2      20      -2      30       5
#Mann= 3 , 0 , 0
       0     .03       0       0     .03       0      30     .03       0
Bank Sta=0,30
XS Rating Curve= 0 ,0
Exp/Cntr=0.3,0.1

River Reach=Churchill River ,Main DS
Reach XY= 30
392769.8948848085911242.63821614392769.7238922575911242.46722359
     392772.3149     5911255.552     392814.3388    5911398.6122
      392832.745    5911550.1834     392832.5598    5911676.5487
     392796.5764    5911881.8658     392756.3596    5912027.9161
     392737.0326    5912083.6011     392727.0819    5912112.2715
     392707.4456    5912168.8477392701.4818186035912185.34551994
392697.9963241295912199.12185874392695.8341739975912207.77045927
     392695.2863    5912216.4103      392688.594    5912242.6005
     392681.5458     5912285.916     392677.5666    5912326.4725
     392674.8356    5912415.4487     392684.1423    5912543.1765
392703.5789864885912660.37382837     392733.0904    5912758.8124
     392786.0071    5912932.1148     392949.1619    5913359.9371
     393036.3696    5913645.8298     393062.4973    5913758.3882
     393090.6093    5913917.0282     393119.7135     5914233.206
     393151.7357    5914612.8969     393154.8395       5914649.7

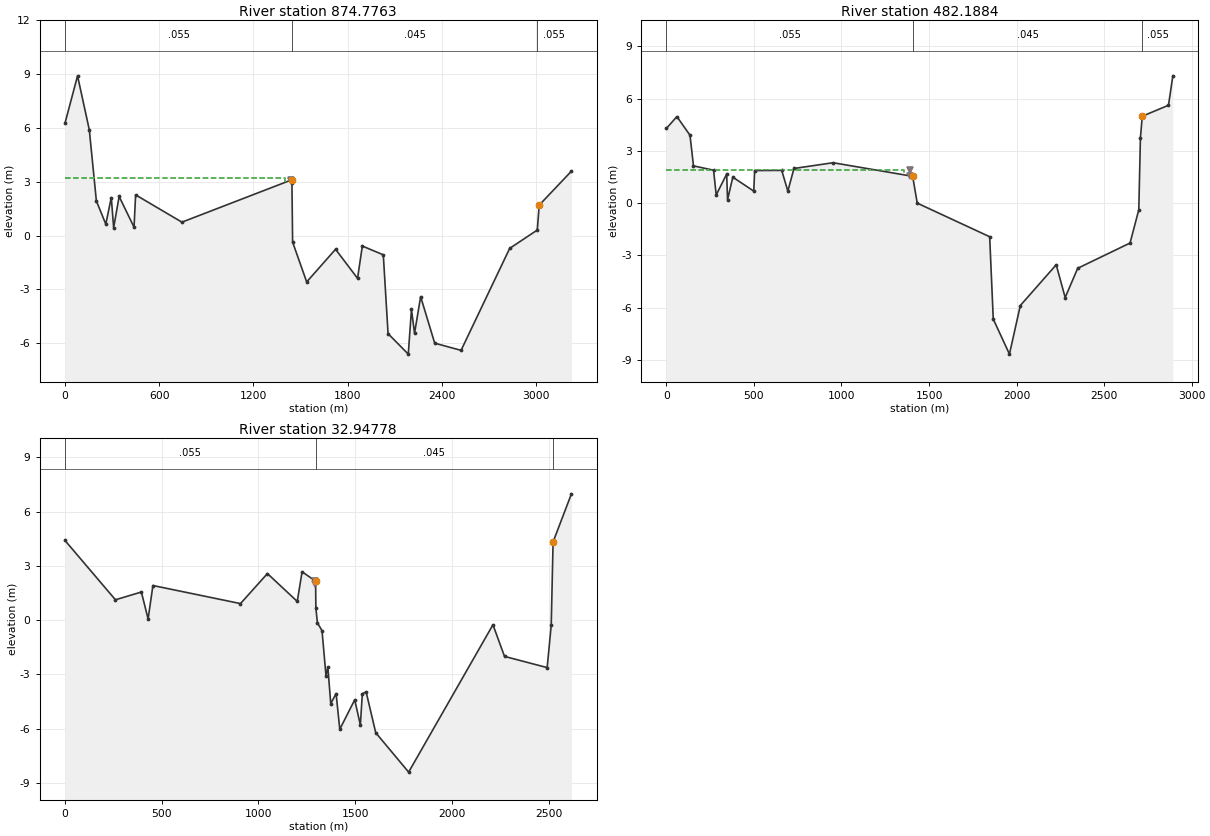
Type RM Length L Ch R = 1 ,874.7763,130.1,392.59,1051.87
XS GIS Cut Line= 2
     390785.9067    5912091.0588     393820.2728      5910995.65
#Sta/Elev= 30
       0    6.26   79.98     8.9  154.96    5.89  199.95    1.93  259.94     .64
  294.93    2.12  309.93     .44  344.92    2.18   439.9     .47   449.9    2.27
  744.83     .75 1444.97    3.11 1445.63    2.91  1449.9    -.36 1539.55   -2.58
 1723.42    -.76  1863.6   -2.38 1894.03    -.58 2027.62   -1.07 2057.93   -5.46
 2186.72    -6.6 2206.94   -4.11 2226.61   -5.44 2265.44    -3.4 2355.05   -5.99
 2522.92   -6.39 2832.65    -.71 3008.39     .31 3020.78     1.7 3226.03    3.59
#Mann= 3 ,-1 , 0
       0    .055       0 1445.63    .045       0 3008.39    .055       0
Levee=-1,1438.84,3.03,0,,,,
#XS Ineff= 2 , 0
         1399.38    3.19
Permanent Ineff=
       F       F
Bank Sta=1444.97,3020.78
XS Rating Curve= 0 ,0
Exp/Cntr(USF)=0.5,0.3
Exp/Cntr=0.5,0.3

Type RM Length L Ch R = 1 ,482.1884,112.67,449.24,807.63
XS GIS Cut Line= 5
     390821.6015    5912211.3718      391553.291    5911960.6071
     392048.4026     5911878.808     392049.5722    5911878.6148
393644.0986969595911615.17765598
#Sta/Elev= 30
       0    4.29   59.88    4.97  134.73     3.9  154.69    2.14  269.47    1.89
  284.44     .47  344.32    1.67  349.31     .19  379.25    1.49  499.01     .69
     504    1.87  658.69    1.88  693.63     .69  728.56    1.99  952.34    2.32
 1406.43    1.54 1432.73       0 1846.32   -1.93 1866.93   -6.66  1959.3   -8.67
 2021.33   -5.88 2226.43   -3.54 2277.58   -5.42 2349.14   -3.74 2648.16   -2.29
 2698.07    -.38 2707.39    3.75 2717.95    4.99 2867.68    5.62 2892.62    7.31
#Mann= 3 , 0 , 0
       0    .055       0 1406.43    .045       0 2717.95    .055       0
Levee=-1,1391.71,1.88,0,,,,
#XS Ineff= 2 , 0
         1359.75    1.91
Permanent Ineff=
       F       F
Bank Sta=1406.43,2717.95
XS Rating Curve= 0 ,0
Exp/Cntr(USF)=0.5,0.3
Exp/Cntr=0.5,0.3

Type RM Length L Ch R = 1 ,32.94778,207.75,207.75,207.75
XS GIS Cut Line= 5
     390848.0599    5912303.9762     391122.9355    5912226.9858
     392022.9791    5912202.7855     393444.9376     5912164.552
393454.9701555535912164.28224541
#Sta/Elev= 30
       0     4.4  260.85    1.12  394.89    1.55  429.71     .06  454.58    1.91
  907.26     .91 1046.54    2.57  1200.8    1.03 1225.75    2.67 1295.63    2.15
 1296.99     .67 1304.89    -.15 1328.88    -.59 1349.33   -3.08 1359.13   -2.61
 1373.84   -4.62 1401.63   -4.07 1420.65   -6.04 1497.82   -4.41 1527.11   -5.81
 1537.09   -4.08 1556.75   -3.97 1606.47   -6.23 1776.63   -8.41 2212.53    -.26
 2272.25   -2.01 2492.79   -2.63 2513.79    -.28 2523.36    4.32  2618.3    6.98
#Mann= 3 , 0 , 0
       0    .055       0 1295.63    .045       0 2523.36    .055       0
Levee=-1,1291.44,1.98,0,,,,
#XS Ineff= 2 , 0
         1282.28    2.16
Permanent Ineff=
       F       F
Bank Sta=1295.63,2523.36
XS Rating Curve= 0 ,0
Exp/Cntr(USF)=0.5,0.3
Exp/Cntr=0.5,0.3

Storage Area=Mud Lake        ,396337.6516592,5907388.0053815
Storage Area Surface Line= 6
394736.7335840415907779.68460828
395907.3849676535909664.43333589
397253.6340588065909336.65094848
397109.6146895315904912.82561114
395818.8498630855905249.78656694
394736.7335840415907779.68460828
Storage Area Type= 0
Storage Area Area=8000
Storage Area Min Elev=-5
Storage Area Vol Elev= 1
               0

Chan Stop Cuts=-1
Use User Specified Reach Order=0
Composite Channel Slope=5

--- Churchill_Mapping.g06 (geometry) ---

Geom Title=Current Conditions - KGS LiDAR
Program Version=4.10

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
Junct Name=J2
Junct Desc=, 0 , 0 ,-1 ,0
Up River,Reach=Mud Lake A      ,Main A
Up River,Reach=Mud Lake B      ,Main
Dn River,Reach=Mud Lake C      ,Main
Junc L&A=239.3,0
Junc L&A=256.52,0

Junct Name=J3
Junct Desc=, 0 , 0 ,-1 ,0
Up River,Reach=Churchill River ,Main
Up River,Reach=Mud Lake C      ,Main
Dn River,Reach=Churchill River ,Main DS
Junc L&A=460.87,
Junc L&A=832.64,

River Reach=Churchill River ,Main

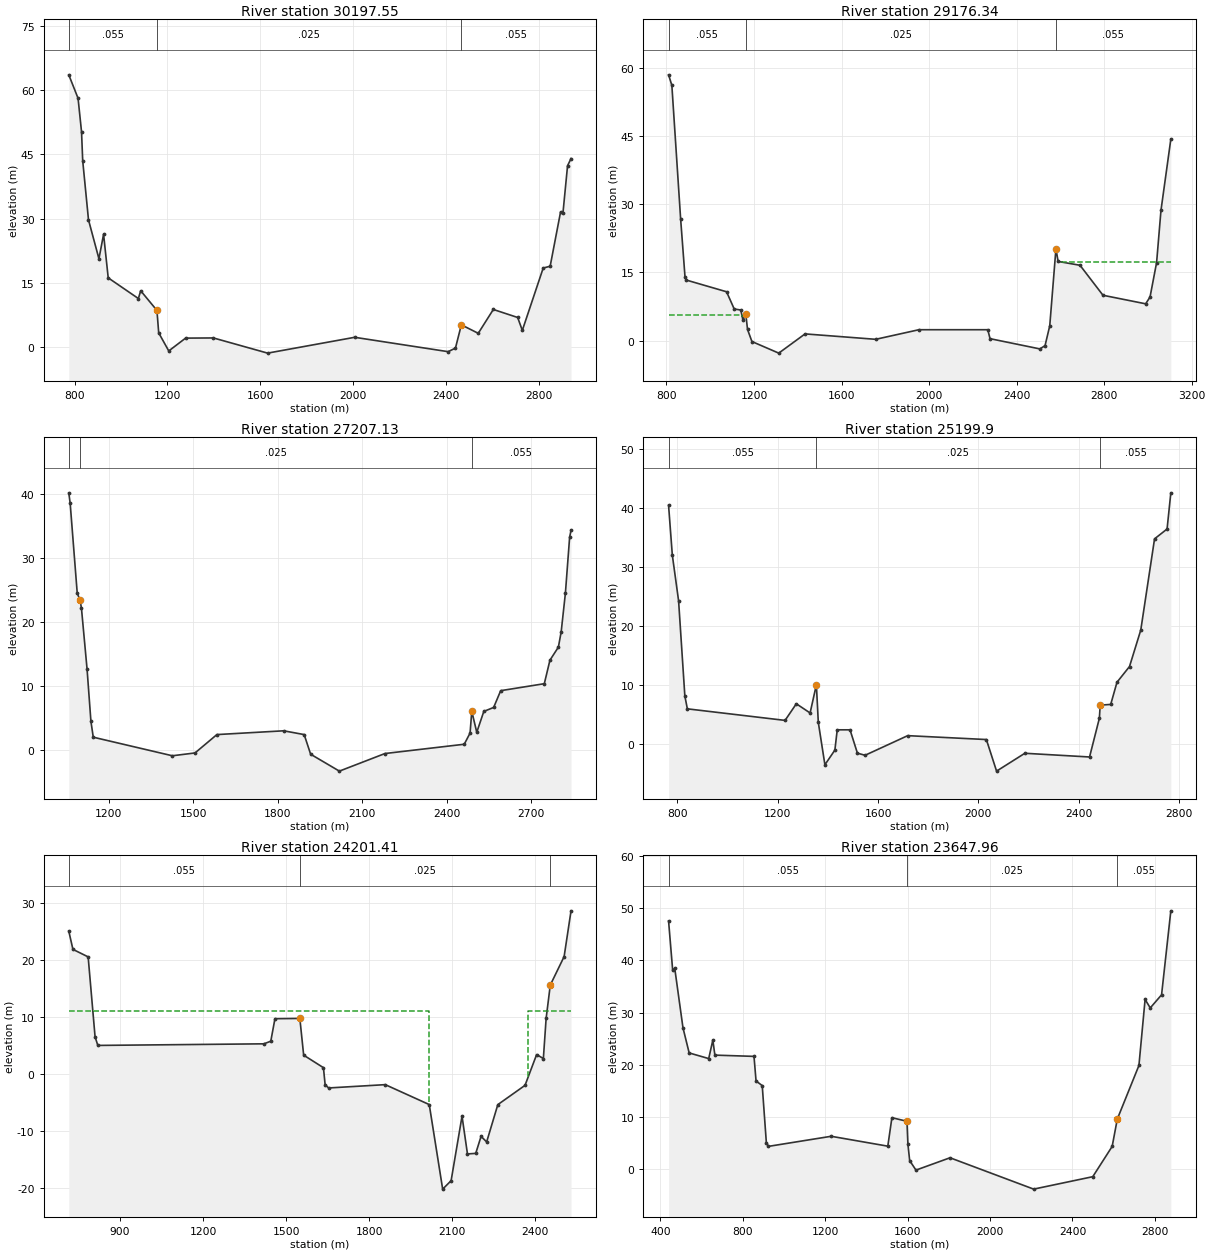
Type RM Length L Ch R = 1 ,30197.55,1025.02,1021.21,1018.34
XS GIS Cut Line= 2
365551.1467196745904527.67976934366021.5640176275902414.65468567
#Sta/Elev= 30
  774.91    63.5  814.91   58.03  829.91    50.2   834.9   43.49   859.9   29.68
   904.9   20.61  924.89   26.32  944.89   16.16 1074.88   11.34 1084.88   13.15
 1154.87    8.57 1162.47    3.34 1205.81    -.88 1278.44    2.11 1398.24    2.15
 1631.86   -1.39 2007.11     2.3 2409.88   -1.05 2441.47    -.22 2466.92    5.21
 2539.71    3.23  2604.7    8.79 2709.69    6.92 2729.69    3.91 2819.68   18.45
 2849.67   18.87 2894.67   31.57 2904.67   31.18 2924.66   42.31 2939.66   43.98
#Mann= 3 , 0 , 0
  774.91    .055       0 1154.87    .025       0 2466.92    .055       0
Bank Sta=1154.87,2466.92
XS Rating Curve= 0 ,0
Exp/Cntr(USF)=0.3,0.1
Exp/Cntr=0.5,0.3

Type RM Length L Ch R = 1 ,29176.34,1138.34,976.42,790.73
XS GIS Cut Line= 2
366560.9276692795904678.03350944367059.5760711035902438.19974385
#Sta/Elev= 30
  809.88   58.48  824.88   56.17  864.87   26.84  884.87    14.1  889.87   13.34
 1074.84   10.75 1109.84    6.95 1139.83    6.74 1149.83    4.47 1162.71    5.88
 1170.58    2.46 1190.71     -.2 1313.32   -2.75 1433.44    1.48 1756.23     .29
 1953.58     2.4 2268.33     2.4 2278.55     .43 2506.13   -1.82 2529.83   -1.11
 2551.38    3.26 2579.62   20.19 2589.62   17.42 2689.61   16.58 2794.59    9.98
 2989.56     8.1 3009.56     9.6 3039.55   17.18 3059.55   28.68 3104.55   44.32
#Mann= 3 , 0 , 0
  809.88    .055       0 1162.71    .025       0 2579.62    .055       0
#XS Ineff= 2 ,-1
  809.88 1146.63    5.57 2601.53 3104.55   17.35
Permanent Ineff=
       F       F
Bank Sta=1162.71,2579.62
XS Rating Curve= 0 ,0
Exp/Cntr(USF)=0.3,0.1
Exp/Cntr=0.5,0.3

Type RM Length L Ch R = 1 ,27207.13,1086.67,1005.59,915.85
XS GIS Cut Line= 2
368653.9797961015904684.76221193368844.699946377  5902912.006482
#Sta/Elev= 30
  1058.8   40.17  1063.8   38.51 1088.77   24.51 1098.76   23.39 1103.75   22.16
  1123.8   12.59 1137.41    4.46 1145.74    1.99 1426.43    -.91 1506.89    -.47
  1584.6     2.4  1821.6    2.99 1894.43     2.4 1917.42    -.67 2019.36   -3.31
 2181.25    -.56 2462.69     .89  2483.4    2.64 2489.38    6.04 2507.16    2.76
 2532.14    6.02  2567.1    6.64 2592.07    9.26 2746.89   10.35 2766.87   14.02
 2796.84   16.06 2806.83   18.46 2821.81   24.51 2836.79   33.24 2841.79   34.31
#Mann= 3 , 0 , 0
  1058.8    .055       0 1098.76    .025       0 2489.38    .055       0
Bank Sta=1098.76,2489.38
XS Rating Curve= 0 ,0
Exp/Cntr(USF)=0.3,0.1
Exp/Cntr=0.5,0.3

Type RM Length L Ch R = 1 ,25199.9 ,1065.31,998.49,975.09
XS GIS Cut Line= 2
370718.3077095245905191.75483746370741.7553093775903188.30404968
#Sta/Elev= 30
  764.45   40.49  779.44   32.04  804.43   24.29  829.41    8.13   839.4    5.96
 1229.12       4 1274.09    6.82 1329.05    5.26 1354.04   10.06 1361.74    3.67
 1388.08   -3.53 1427.87   -1.04 1437.24     2.4 1488.35     2.4 1517.74   -1.56
  1548.3   -1.92 1718.39    1.41 2032.18     .75 2072.87   -4.61 2185.69   -1.58
 2443.79   -2.21 2482.95    4.36 2486.28    6.59  2528.2    6.71 2553.18   10.47
 2603.14   13.14 2648.11   19.33 2703.07   34.81 2753.03   36.48 2768.02   42.62
#Mann= 3 , 0 , 0
  764.45    .055       0 1354.04    .025       0 2486.28    .055       0
Bank Sta=1354.04,2486.28
XS Rating Curve= 0 ,0
Exp/Cntr(USF)=0.3,0.1
Exp/Cntr=0.5,0.3

Type RM Length L Ch R = 1 ,24201.41,139.37,137.37,138.3
XS GIS Cut Line= 2
371756.7121453255905380.33097292371720.4204786075903565.74943093
#Sta/Elev= 30
  714.98   25.08  729.98   21.87  784.98   20.55  809.97    6.52  819.97       5
 1419.95    5.28 1444.95    5.74 1459.95    9.69 1549.95    9.74 1563.74    3.29
 1635.23    1.09 1641.31   -1.91 1653.94   -2.47  1858.7   -1.89 2017.59   -5.39
 2066.03  -20.24 2096.55  -18.76 2136.02   -7.43 2155.63  -14.06 2185.55  -13.96
 2204.82  -10.97 2224.98  -11.95 2265.34    -5.4 2363.69   -2.01 2405.55    3.39
 2429.92     2.7 2439.92    9.75 2454.92    15.6 2504.92    20.6 2529.92   28.64
#Mann= 3 , 0 , 0
  714.98    .055       0 1549.95    .025       0 2454.92    .055       0
#XS Ineff= 2 , 0
            2015      11    2375              11
Permanent Ineff=
       F       F
Bank Sta=1549.95,2454.92
XS Rating Curve= 0 ,0
Exp/Cntr(USF)=0.3,0.1
Exp/Cntr=0.5,0.3

Type RM Length L Ch R = 1 ,23647.96,505.71,502.05,500
XS GIS Cut Line= 2
 372283.76814197 5905725.6832207372276.5909787285903288.52239177
#Sta/Elev= 30
  439.63   47.56  459.62   38.08  469.61   38.48  509.58    27.1  539.55    22.3
  634.47   21.22  654.46   24.75  664.45   21.88  854.29   21.64  864.28   16.93
  894.26   16.05  914.24    5.13  924.23    4.42 1228.98    6.35 1503.75    4.46
 1523.73    9.91 1596.74    9.22 1601.42    4.82 1609.95     1.7 1640.47    -.12
 1805.82    2.24 2211.82   -3.76 2498.71   -1.38 2592.85    4.41 2617.83    9.65
 2722.74    19.9 2752.71   32.54 2777.69   30.91 2832.65   33.42 2877.61   49.49
#Mann= 3 , 0 , 0
  439.63    .055       0 1596.74    .025       0 2617.83    .055       0
#XS Ineff= 2 , 0
         1570.62    8.99
Permanent Ineff=
       F       F
Bank Sta=1596.74,2617.83
XS Rating Curve= 0 ,0
Exp/Cntr(USF)=0.5,0.3
Exp/Cntr=0.5,0.3

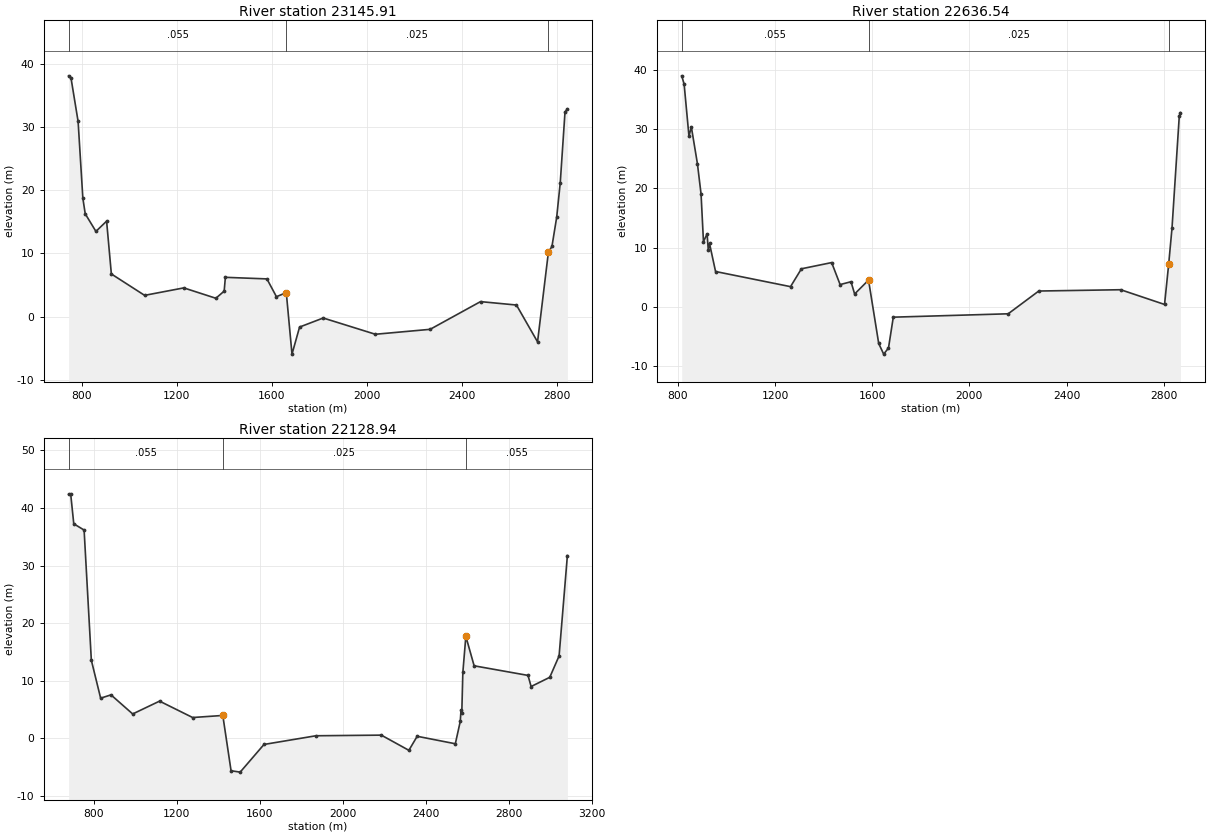
Type RM Length L Ch R = 1 ,23145.91,131.3,509.36,874.95
XS GIS Cut Line= 2
     372782.06125905486.04409512     372782.06125903387.08730234
#Sta/Elev= 30
  744.63   38.07  754.63   37.75  784.61   30.86   804.6   18.71   814.6   16.26
  859.58   13.48  904.55    15.1  924.54    6.75 1064.47    3.37 1229.39    4.55
 1364.33    2.91 1399.31    4.04 1404.31    6.22 1579.22    5.97  1619.2    3.16
 1660.71     3.8 1684.71   -5.92 1716.64   -1.64  1816.1    -.21 2035.59   -2.78
 2266.02      -2 2478.04    2.38 2629.31    1.84 2718.07   -3.98 2763.64   10.17
 2778.63    11.1 2798.62   15.72 2813.61   21.18  2833.6   32.35  2843.6   32.84
#Mann= 3 , 0 , 0
  744.63    .055       0 1660.71    .025       0 2763.64    .055       0
Bank Sta=1660.71,2763.64
XS Rating Curve= 0 ,0
Exp/Cntr(USF)=0.5,0.3
Exp/Cntr=0.5,0.3

Type RM Length L Ch R = 1 ,22636.54,243.38,507.6,678.94
XS GIS Cut Line= 4
372915.9574064325905440.96374746     372916.6397     5905346.413
     373087.2052     5904768.912373471.2682796985903468.55016847
#Sta/Elev= 30
  816.19   39.05  826.14   37.66  846.05   28.86     856   30.39  880.88   24.19
  895.81   19.08  905.77   11.02   920.7   12.32  925.67    9.55  930.65    10.7
  955.53    5.96 1264.08     3.4 1308.87    6.42 1433.28    7.47 1468.12    3.75
 1512.91    4.23 1527.86    2.16  1585.1    4.51 1626.94   -6.21 1647.35   -8.01
 1667.18   -6.98 1686.98   -1.76 2159.79   -1.19 2285.57    2.66 2622.79    2.88
 2803.24     .39 2820.13    7.15 2833.91   13.28 2863.82   32.22  2868.8   32.83
#Mann= 3 , 0 , 0
  816.19    .055       0  1585.1    .025       0 2820.13    .055       0
Bank Sta=1585.1,2820.13
XS Rating Curve= 0 ,0
Exp/Cntr(USF)=0.5,0.3
Exp/Cntr=0.5,0.3

Type RM Length L Ch R = 1 ,22128.94,396.14,507.49,502.51
XS GIS Cut Line= 4
373202.0571685045905621.70403538     373431.5829    5905075.4949
      373964.584    5903807.0964374132.8194875145903406.74148285
#Sta/Elev= 30
  679.37   42.35  689.33   42.46  704.26   37.25  754.05   36.16   788.9   13.53
  833.71    6.94   883.5    7.52  988.05     4.2  1117.5    6.43 1276.83    3.58
 1422.15    3.94 1461.91   -5.67 1505.84   -5.91 1620.56    -1.1 1870.69     .41
 2185.71     .52 2318.46   -2.12 2358.41     .32 2542.19    -.98 2565.98    2.91
 2569.67    4.91 2573.33    4.36 2578.41   11.41 2592.85   17.69 2632.73   12.57
 2892.26    10.9 2907.24    8.97 2997.08   10.57 3042.01   14.29 3081.94   31.73
#Mann= 3 , 0 , 0
  679.37    .055       0 1422.15    .025       0 2592.85    .055       0
Bank Sta=1422.15,2592.85
XS Rating Curve= 0 ,0
Exp/Cntr(USF)=0.5,0.3
Exp/Cntr=0.5,0.3