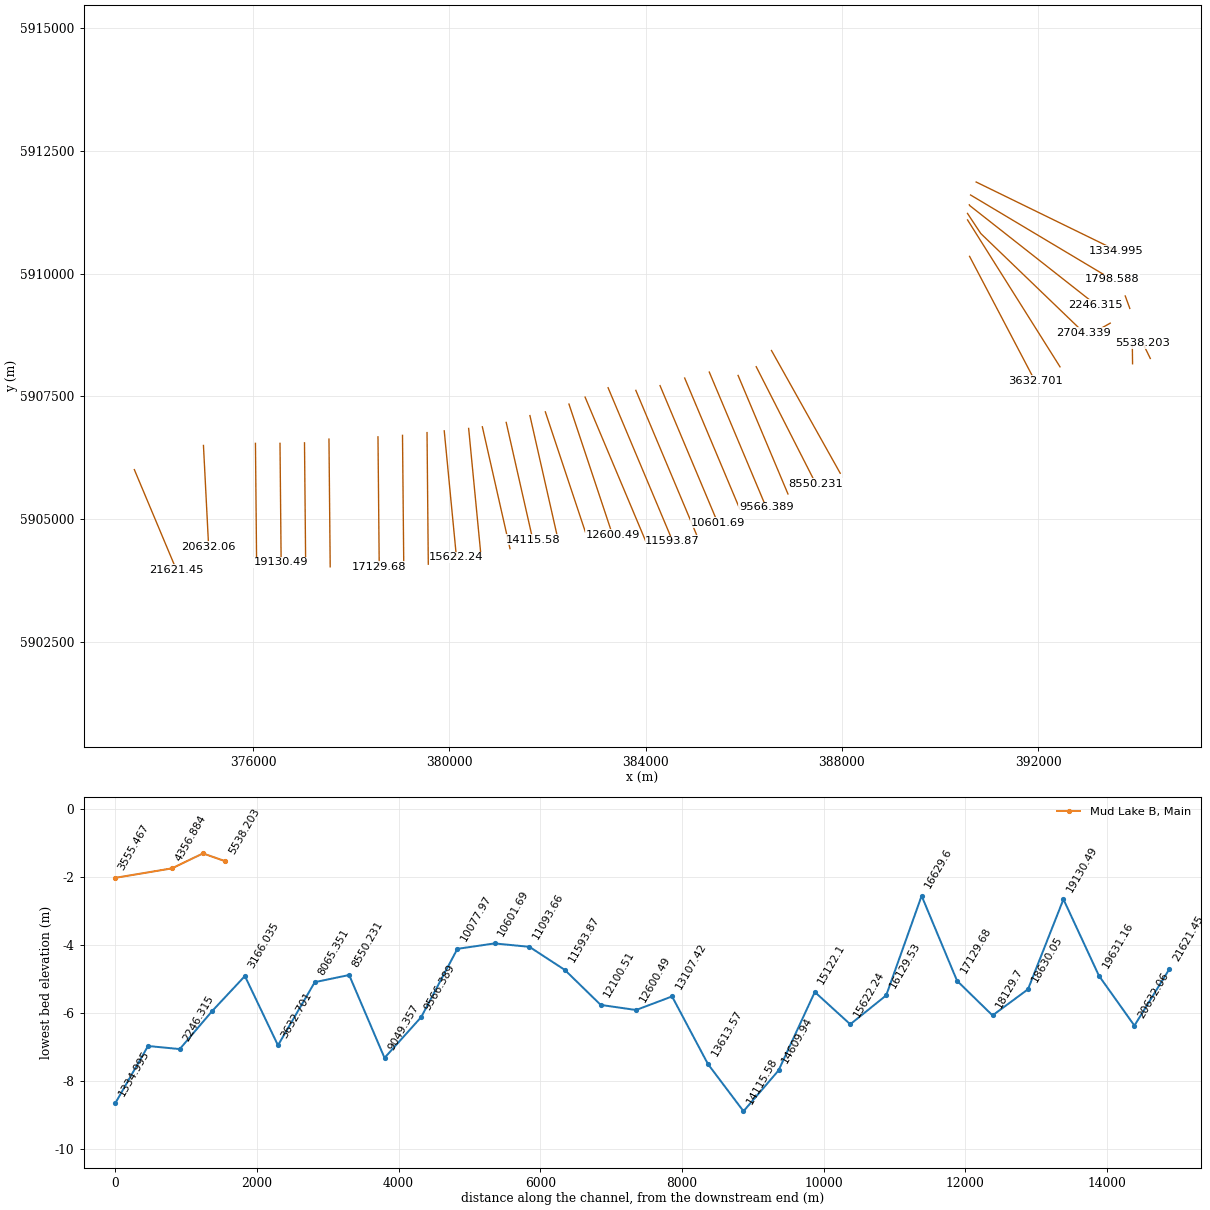
HEC-RAS study Churchill_Mapping.prj: Churchill River Flood Risk Mapping

--- Churchill_Mapping.g06 (geometry) --- (continued)

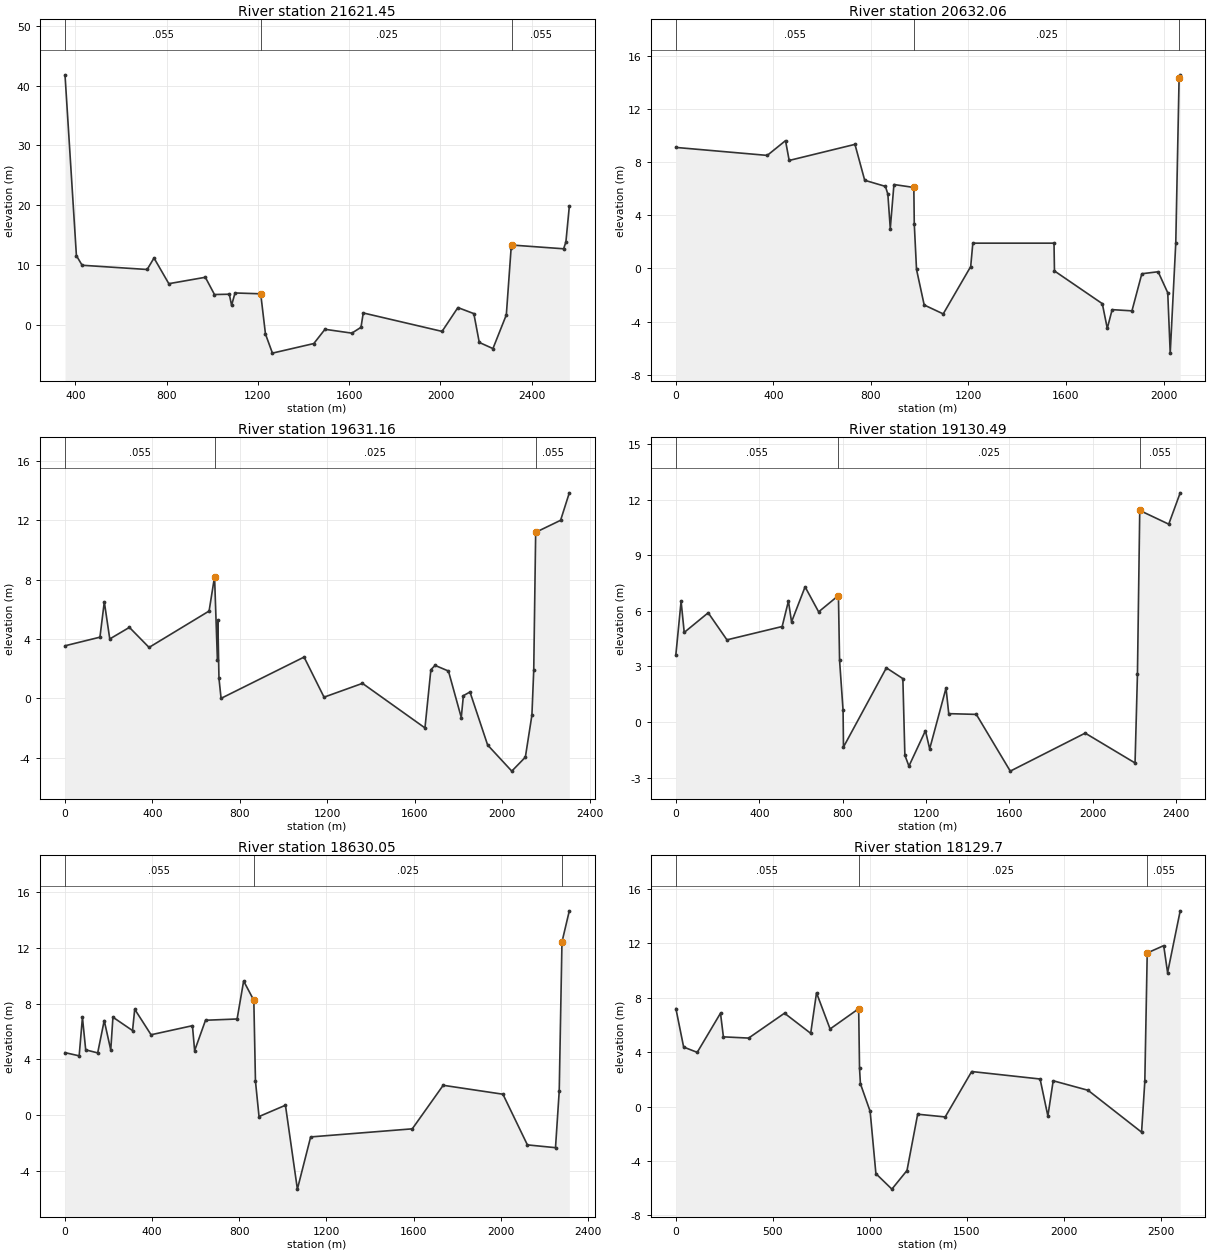
Type RM Length L Ch R = 1 ,21621.45,766.04,494.66,174.79
XS GIS Cut Line= 2
 373583.320066235906010.14302272374439.3020494875903973.13768515
#Sta/Elev= 30
  354.93   41.79  404.92   11.58  429.91    9.98  714.86    9.27  744.85   11.19
  809.84     6.9   969.8    7.97  1009.8    5.09 1074.78    5.14 1084.78    3.28
 1099.78    5.35 1212.37    5.21 1233.22   -1.51 1263.68    -4.7 1445.02    -3.1
 1493.91    -.72 1611.64   -1.36 1651.68    -.39 1661.66    2.01 2006.94   -1.07
  2076.3    2.91 2146.16     1.9 2169.93   -2.91 2229.83   -3.94 2288.49    1.69
 2309.53   12.87 2314.53   13.35 2539.49   12.73 2549.49   13.87 2564.48   19.83
#Mann= 3 , 0 , 0
  354.93    .055       0 1212.37    .025       0 2314.53    .055       0
Bank Sta=1212.37,2314.53
XS Rating Curve= 0 ,0
Exp/Cntr(USF)=0.5,0.3
Exp/Cntr=0.5,0.3

Type RM Length L Ch R = 1 ,20632.06,553.47,500.95,431.9
XS GIS Cut Line= 2
     374991.4999    5906501.4228 375097.32182344 5904435.6962342
#Sta/Elev= 30
       0     9.1  374.72     8.5  449.66    9.61  464.65    8.12  734.45    9.33
  774.42    6.63  859.36    6.17  869.35    5.59  879.34       3  894.33    6.31
  975.94    6.09  977.74    3.35  986.99    -.08 1018.44   -2.75 1096.46   -3.42
 1209.18     .14 1217.91     1.9  1550.9     1.9 1552.74    -.19    1749   -2.65
 1769.38   -4.51 1789.33    -3.1 1870.57   -3.19 1911.08     -.4 1977.94    -.25
 2017.36   -1.83 2027.52   -6.37 2050.31    1.92  2063.9    14.3 2068.45   14.56
#Mann= 3 , 0 , 0
       0    .055       0  975.94    .025       0  2063.9    .055       0
Bank Sta=975.94,2063.9
XS Rating Curve= 0 ,0
Exp/Cntr(USF)=0.5,0.3
Exp/Cntr=0.5,0.3

Type RM Length L Ch R = 1 ,19631.16,500,500.67,502.47
XS GIS Cut Line= 2
     376050.8276    5906544.7603376073.0993071895904237.96505875
#Sta/Elev= 30
       0    3.54  159.79    4.12  179.76     6.5  204.73       4  294.61    4.78
  384.49    3.43  659.12    5.88  684.08    8.19  697.08    2.61  699.15    5.25
  704.25    1.35  713.91       0 1093.54    2.78 1184.89     .08 1360.68    1.01
 1646.57   -1.99 1673.64    1.93 1692.82    2.22    1754    1.84 1812.65   -1.29
 1822.32     .18 1852.44     .43 1933.19   -3.14 2043.73    -4.9 2105.81   -3.96
  2135.8   -1.13 2144.17    1.91 2153.02   11.18 2266.97   11.99 2306.91   13.84
#Mann= 3 , 0 , 0
       0    .055       0  684.08    .025       0 2153.02    .055       0
Bank Sta=684.08,2153.02
XS Rating Curve= 0 ,0
Exp/Cntr(USF)=0.5,0.3
Exp/Cntr=0.5,0.3

Type RM Length L Ch R = 1 ,19130.49,499.21,500.44,499.99
XS GIS Cut Line= 2
     376550.8517    5906544.6705376574.2087307785904125.46404562
#Sta/Elev= 30
       0    3.64   24.99    6.51   39.99    4.83  154.96    5.89  244.93    4.43
  509.85    5.15  539.85    6.52  554.84     5.4  619.82    7.29  684.81    5.94
  779.78    6.82  785.18    3.34  802.05     .62  803.99   -1.35 1009.71    2.92
 1088.83    2.34 1098.51   -1.79 1117.95   -2.38 1197.14    -.47 1217.48   -1.45
 1295.93    1.83 1308.92     .45 1441.29     .41 1604.12   -2.65 1963.51     -.6
 2202.71   -2.21 2214.22    2.57 2225.27   11.41 2364.33   10.67 2419.31   12.36
#Mann= 3 , 0 , 0
       0    .055       0  779.78    .025       0 2225.27    .055       0
Bank Sta=779.78,2225.27
XS Rating Curve= 0 ,0
Exp/Cntr(USF)=0.5,0.3
Exp/Cntr=0.5,0.3

Type RM Length L Ch R = 1 ,18630.05,499.27,500.35,499.48
XS GIS Cut Line= 2
     377049.9631    5906554.4619377072.3123497025904239.62897053
#Sta/Elev= 30
       0    4.48      65    4.25      80       7      95    4.68     150    4.46
     180    6.78  209.99    4.67  219.99    7.02  309.99    6.06  319.99    7.59
  394.99    5.76  584.99    6.41  594.99    4.62  644.98     6.8  789.98    6.89
  819.98    9.61  866.73    8.23  874.22    2.44  890.58     -.1 1011.88     .71
 1066.66    -5.3 1127.61   -1.56 1594.08    -.98 1735.96    2.14 2010.17     1.5
 2122.49   -2.13 2251.54   -2.33 2268.63    1.73  2281.2   12.41 2314.94   14.64
#Mann= 3 , 0 , 0
       0    .055       0  866.73    .025       0  2281.2    .055       0
Bank Sta=866.73,2281.2
XS Rating Curve= 0 ,0
Exp/Cntr(USF)=0.5,0.3
Exp/Cntr=0.5,0.3

Type RM Length L Ch R = 1 ,18129.7 ,500.09,500.74,500.29
XS GIS Cut Line= 2
     377548.4327    5906630.7123377573.5207013765904032.21740899
#Sta/Elev= 30
       0    7.21   39.98    4.38  109.94    3.99  229.88    6.87  244.87    5.13
   374.8    5.04   559.7    6.87  694.63    5.39  724.61    8.37  794.57    5.71
  941.89     7.2  946.23    2.82  950.89    1.68 1000.93    -.35 1030.62   -4.93
 1112.95   -6.07 1190.82    -4.7 1245.83    -.56 1387.73    -.76 1524.18    2.58
 1876.64    2.03 1916.79    -.69 1944.14     1.9 2123.73     1.2 2399.57   -1.88
  2416.3    1.85  2428.7    11.3 2513.65   11.84 2533.64    9.85 2598.61    14.4
#Mann= 3 , 0 , 0
       0    .055       0  941.89    .025       0  2428.7    .055       0
Bank Sta=941.89,2428.7
XS Rating Curve= 0 ,0
Exp/Cntr(USF)=0.5,0.3
Exp/Cntr=0.5,0.3

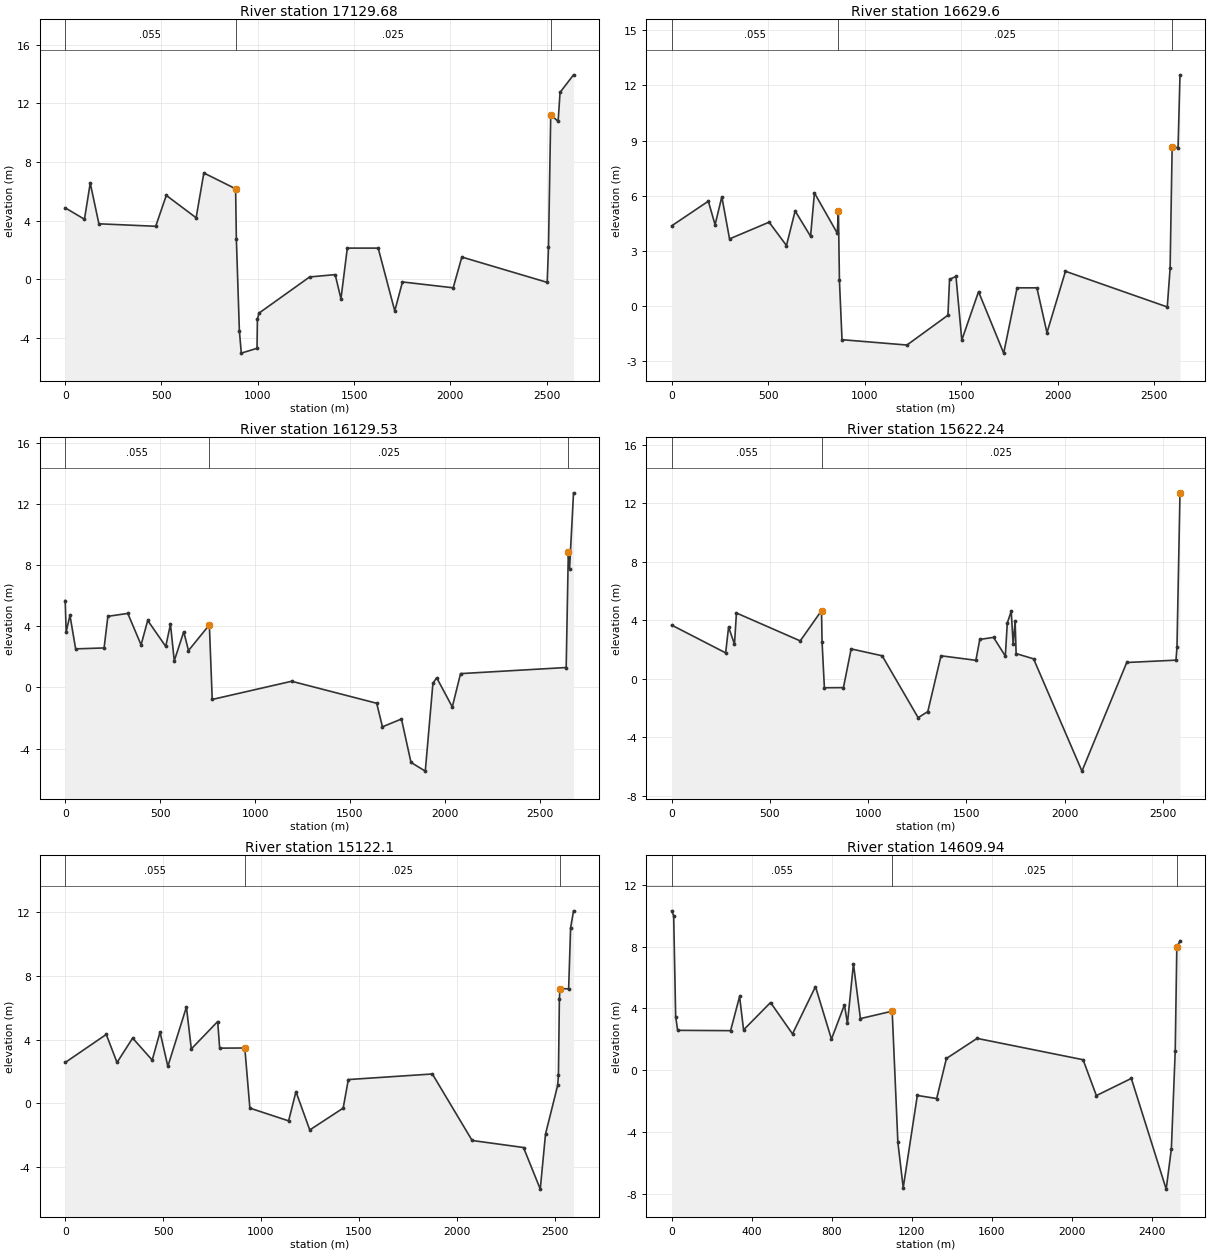
Type RM Length L Ch R = 1 ,17129.68,501.79,500.08,500.22
XS GIS Cut Line= 2
     378547.0115    5906676.9166378572.495428576 5904037.4062686
#Sta/Elev= 30
       0    4.87   99.99    4.09  129.98    6.56  174.98    3.78  469.93    3.61
  524.93    5.72  679.91    4.19   719.9    7.25  884.88    6.17   888.8    2.73
  904.45   -3.53  914.46   -5.05  996.04   -4.72  998.08   -2.74  1006.1   -2.32
 1269.23     .15 1401.87     .31 1431.96   -1.34  1464.9    2.12 1625.25    2.12
 1711.34   -2.17 1751.29    -.19 2014.72    -.59 2059.67    1.51  2502.9    -.22
 2509.63    2.18 2521.26   11.22 2559.65   10.77 2569.65   12.75 2639.63   13.95
#Mann= 3 , 0 , 0
       0    .055       0  884.88    .025       0 2521.26    .055       0
Bank Sta=884.88,2521.26
XS Rating Curve= 0 ,0
Exp/Cntr(USF)=0.5,0.3
Exp/Cntr=0.5,0.3

Type RM Length L Ch R = 1 ,16629.6 ,502.37,500.06,500.22
XS GIS Cut Line= 2
     379046.7455     5906706.877379072.1816065765904072.32763726
#Sta/Elev= 30
       0    4.37  189.98    5.71  224.97    4.43  259.97    5.95  299.96    3.66
  504.94    4.57  594.93     3.3  639.92    5.18  719.91     3.8  739.91    6.16
  858.41    3.97  864.22     5.2  869.48    1.41   882.9   -1.82 1219.44   -2.11
 1431.91    -.49 1440.17    1.46 1473.51    1.62 1503.75   -1.84 1590.51     .79
 1720.87   -2.55  1790.4       1 1892.95       1 1945.19   -1.44 2040.99     1.9
 2568.74    -.04 2583.39    2.06 2593.96    8.65 2624.67    8.62 2634.67   12.58
#Mann= 3 , 0 , 0
       0    .055       0  864.22    .025       0 2593.96    .055       0
Bank Sta=864.22,2593.96
XS Rating Curve= 0 ,0
Exp/Cntr(USF)=0.5,0.3
Exp/Cntr=0.5,0.3

Type RM Length L Ch R = 1 ,16129.53,375.92,507.29,629.41
XS GIS Cut Line= 2
     379546.2263    5906763.0699379572.0767816545904085.59561471
#Sta/Elev= 30
       0    5.68       5    3.63   24.98    4.72   54.95    2.52  204.82    2.58
   224.8    4.65  329.71    4.84  399.64    2.78  434.61    4.38  529.53    2.68
  554.51    4.13  574.49    1.74  624.44    3.64  649.42    2.41  759.32    4.09
  774.41    -.79 1192.63      .4 1640.88   -1.04 1670.98   -2.58 1771.25   -2.07
  1821.4   -4.91  1896.7   -5.48 1936.96     .27 1956.72     .63 2039.01   -1.28
 2082.48      .9 2638.91     1.3 2650.15    8.85 2656.64    7.77 2677.61   12.73
#Mann= 3 , 0 , 0
       0    .055       0  759.32    .025       0 2650.15    .055       0
Bank Sta=759.32,2650.15
XS Rating Curve= 0 ,0
Exp/Cntr(USF)=0.5,0.3
Exp/Cntr=0.5,0.3

Type RM Length L Ch R = 1 ,15622.24,502.11,500.14,501.46
XS GIS Cut Line= 2
     379896.7436    5906799.3701380146.0105672965904224.39180596
#Sta/Elev= 30
       0    3.67  274.68    1.77  289.66    3.54  319.63    2.36  329.62     4.5
  654.24    2.59  762.51    4.66  765.46     2.5  777.19    -.62  874.17    -.61
  913.44    2.04  1071.2    1.57 1254.41   -2.67 1303.56   -2.25 1370.68    1.57
 1548.21    1.26 1568.19    2.69 1638.11    2.83 1698.04    1.55 1708.03    3.81
    1728    4.62 1737.99    2.36 1747.98    3.95 1752.97    1.72 1841.84    1.36
 2088.04   -6.33 2315.95    1.11 2566.55    1.27 2571.61    2.14 2587.01   12.73
#Mann= 3 , 0 , 0
       0    .055       0  762.51    .025       0 2587.01               0
Bank Sta=762.51,2587.01
XS Rating Curve= 0 ,0
Exp/Cntr(USF)=0.5,0.3
Exp/Cntr=0.5,0.3

Type RM Length L Ch R = 1 ,15122.1 ,308.62,512.16,677.55
XS GIS Cut Line= 2
     380394.3265    5906848.4833380644.543516056 5904263.6917654
#Sta/Elev= 30
       0    2.56  209.75    4.32  264.68    2.56  344.59    4.09  444.47    2.71
  484.42    4.47  524.37    2.32  619.26    6.04  644.23    3.41  779.06    5.13
  789.05    3.46  917.53    3.47  943.42     -.3 1141.32    -1.1 1178.85     .73
 1249.38   -1.67 1420.06     -.3 1446.36    1.49  1875.7    1.84 2078.89   -2.33
  2341.3   -2.77 2426.93   -5.38 2453.74   -1.93  2515.7    1.12 2519.71    1.75
  2524.6    6.55 2527.68    7.19 2571.91    7.18  2581.9      11 2596.88   12.07
#Mann= 3 , 0 , 0
       0    .055       0  917.53    .025       0 2527.68    .055       0
Bank Sta=917.53,2527.68
XS Rating Curve= 0 ,0
Exp/Cntr(USF)=0.5,0.3
Exp/Cntr=0.5,0.3

Type RM Length L Ch R = 1 ,14609.94,493.61,494.36,496.64
XS GIS Cut Line= 2
     380673.5607    5906880.9974381236.1318359115904402.35563074
#Sta/Elev= 30
       0   10.31    9.99    9.99   19.97    3.47   29.96    2.58  294.62    2.56
  339.56    4.77  359.53    2.61  494.36    4.38  604.21    2.35  719.07    5.41
  798.96    2.01  863.88    4.23  878.86    3.03  908.82    6.88  943.77    3.34
 1102.53    3.82 1131.08   -4.67 1157.77    -7.6 1228.28   -1.63 1325.07   -1.83
 1373.71     .76 1527.16    2.06  2057.1     .68 2123.53   -1.64 2298.28    -.53
 2472.66   -7.69 2498.49   -5.09  2517.8    1.25 2525.77    7.96 2541.69    8.36
#Mann= 3 , 0 , 0
       0    .055       0 1102.53    .025       0 2525.77    .055       0
Bank Sta=1102.53,2525.77
XS Rating Curve= 0 ,0
Exp/Cntr(USF)=0.5,0.3
Exp/Cntr=0.5,0.3

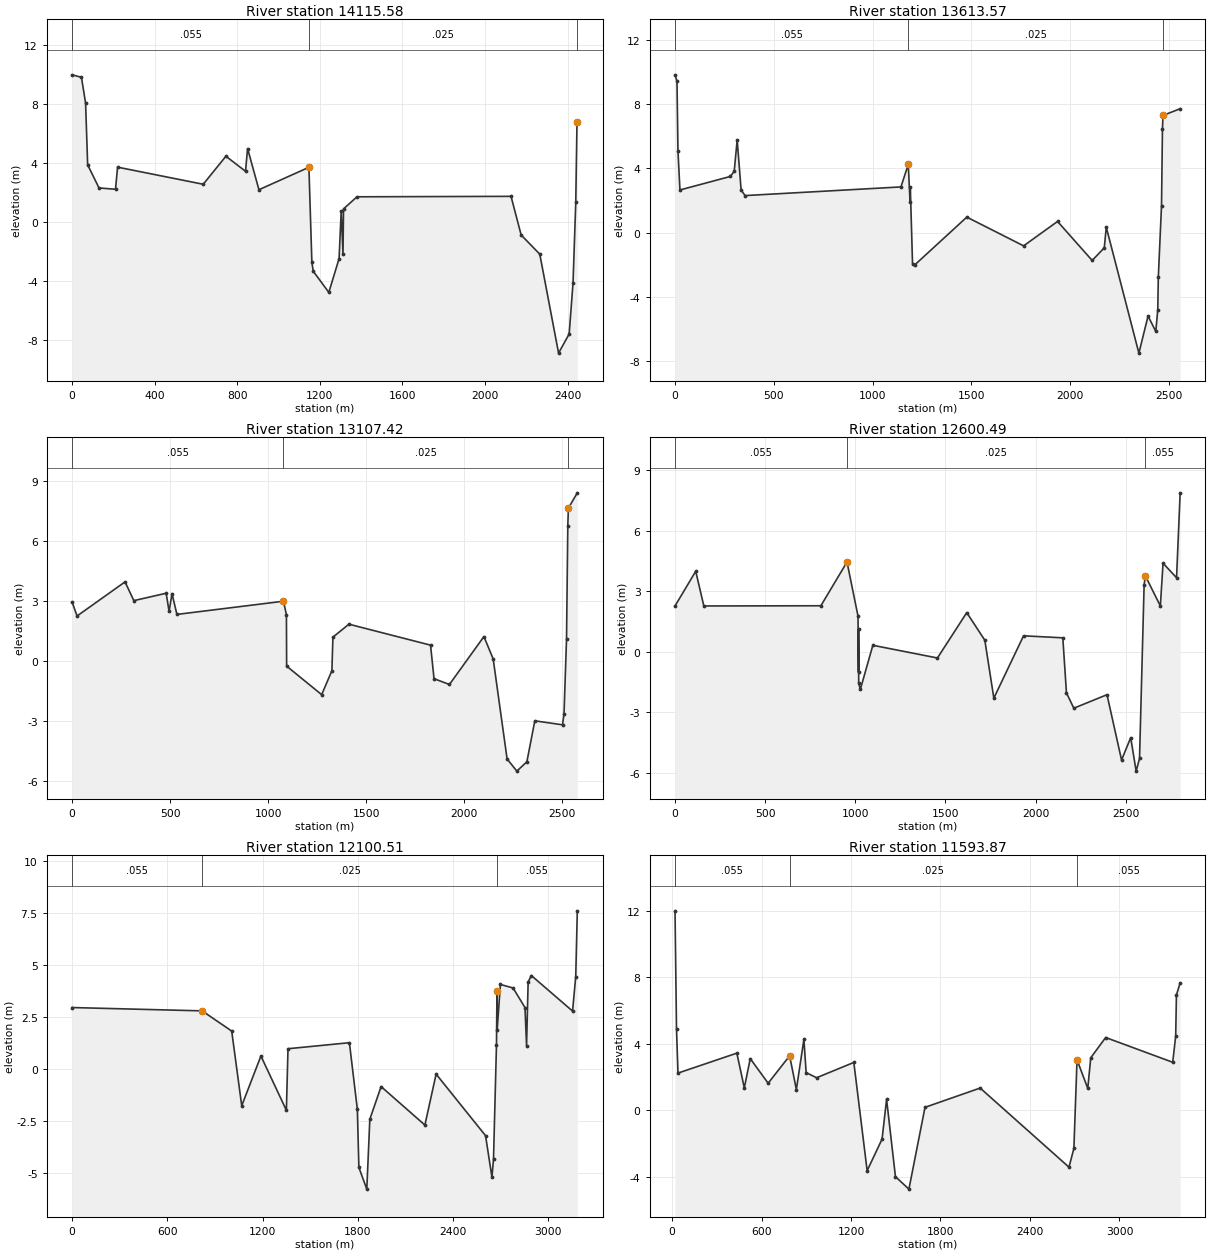
Type RM Length L Ch R = 1 ,14115.58,502.3,502.01,505.04
XS GIS Cut Line= 2
     381159.4143     5906970.222381701.0929724185904583.63085306
#Sta/Elev= 30
       0    9.98   44.99    9.81   64.99    8.06   74.98    3.88  129.97    2.31
  209.95    2.22  219.95    3.72  634.86    2.56  744.83    4.46  839.81    3.44
  849.81    4.98   904.8    2.19 1146.91    3.71 1161.28   -2.74    1168   -3.34
 1243.36   -4.77 1293.14   -2.48 1303.42     .76 1311.98   -2.16 1314.64     .89
 1379.81    1.71 2126.17    1.74 2175.17    -.88 2265.42   -2.18 2356.49   -8.89
 2407.79   -7.59 2426.51   -4.13 2439.79    1.35  2445.7    6.78 2447.27    6.86
#Mann= 3 , 0 , 0
       0    .055       0 1146.91    .025       0  2445.7    .055       0
Bank Sta=1146.91,2445.7
XS Rating Curve= 0 ,0
Exp/Cntr(USF)=0.5,0.3
Exp/Cntr=0.5,0.3

Type RM Length L Ch R = 1 ,13613.57,343.57,506.15,654.42
XS GIS Cut Line= 2
     381642.5406    5907109.1877382208.6682219365904614.87647494
#Sta/Elev= 30
       0    9.83    9.99    9.43   14.99    5.07   24.98    2.66  279.75     3.5
  299.74    3.82  314.72    5.77  334.71    2.66  354.69    2.31 1143.99    2.85
 1181.01    4.25    1190    1.94 1191.36    2.85 1202.68   -1.94 1212.78   -2.02
 1477.47     .97 1765.13    -.82 1936.96      .7 2112.32   -1.73 2173.55    -.94
 2183.64     .34 2348.79    -7.5 2395.23   -5.19 2434.35   -6.15 2444.49   -4.79
 2447.13   -2.79  2463.4    1.69 2468.09    6.45 2470.88     7.3 2557.75    7.72
#Mann= 3 , 0 , 0
       0    .055       0 1181.01    .025       0 2470.88    .055       0
Bank Sta=1181.01,2470.88
XS Rating Curve= 0 ,0
Exp/Cntr(USF)=0.5,0.3
Exp/Cntr=0.5,0.3

Type RM Length L Ch R = 1 ,13107.42,506.78,506.93,512.59
XS GIS Cut Line= 2
     381956.6837    5907185.7673382772.4212553455904739.81756802
#Sta/Elev= 30
       0    2.95   24.98    2.26  269.83    3.97   314.8    3.03   479.7     3.4
  494.69    2.49  509.68    3.38  534.67    2.34 1078.23       3 1093.61    2.33
 1094.65    -.25 1273.51   -1.68 1325.72    -.48 1330.92     1.2 1412.55    1.85
 1829.23      .8 1846.97    -.88 1925.68   -1.17 2101.66    1.23 2148.97     .11
 2219.94    -4.9 2269.78   -5.51 2320.98   -5.04 2361.43   -2.99 2502.92   -3.19
 2510.53   -2.64 2523.35    1.12 2529.88    6.79 2532.82    7.66 2578.39    8.43
#Mann= 3 , 0 , 0
       0    .055       0 1078.23    .025       0 2532.82    .055       0
Bank Sta=1078.23,2532.82
XS Rating Curve= 0 ,0
Exp/Cntr(USF)=0.5,0.3
Exp/Cntr=0.5,0.3

Type RM Length L Ch R = 1 ,12600.49,374.32,499.98,635.01
XS GIS Cut Line= 2
     382438.0603    5907344.0193383324.5546234145904685.90897557
#Sta/Elev= 30
       0    2.28  114.88       4  159.83    2.28  809.15    2.29     954    4.46
 1015.08    1.78  1017.9      -1  1018.2    1.13 1018.85   -1.55 1027.93   -1.86
  1097.4     .33  1455.7     -.3  1618.3    1.95 1718.56     .58 1768.55   -2.29
 1933.41      .8 2151.17      .7 2171.34   -2.03  2212.2   -2.79 2396.18   -2.12
 2477.01   -5.36 2527.74   -4.25 2557.87   -5.91 2576.72   -5.28 2602.17    3.33
 2609.16    3.77 2692.17    2.28 2707.16     4.4 2782.08    3.68 2802.06    7.89
#Mann= 3 , 0 , 0
       0    .055       0     954    .025       0 2609.16    .055       0
Bank Sta=954,2609.16
XS Rating Curve= 0 ,0
Exp/Cntr(USF)=0.5,0.3
Exp/Cntr=0.5,0.3

Type RM Length L Ch R = 1 ,12100.51,507.84,506.64,517.95
XS GIS Cut Line= 2
     382766.0584    5907486.1563 384001.262909315904553.53791462
#Sta/Elev= 30
       0    2.97  818.58    2.81 1004.94    1.84  1068.1   -1.75    1189     .64
  1349.4   -1.97 1359.59     .99 1746.41    1.28 1796.38   -1.92 1806.19   -4.72
 1856.04   -5.76 1875.11    -2.4 1946.11    -.83 2221.91   -2.68 2292.68    -.23
  2604.1   -3.19 2644.36   -5.19 2654.18   -4.31 2672.93    1.19 2675.95    3.76
 2677.04    1.87 2697.57    4.08  2777.5    3.91 2852.44    2.97 2862.43    1.14
 2872.42     4.2  2892.4    4.51 3152.17     2.8 3172.15    4.46 3182.15    7.62
#Mann= 3 , 0 , 0
       0    .055       0  818.58    .025       0 2675.95    .055       0
Bank Sta=818.58,2675.95
XS Rating Curve= 0 ,0
Exp/Cntr(USF)=0.5,0.3
Exp/Cntr=0.5,0.3

Type RM Length L Ch R = 1 ,11593.87,500.02,500.21,510.72
XS GIS Cut Line= 2
 383235.19200717 5907676.2821641384550.0233749435904554.61404688
#Sta/Elev= 30
   19.98   12.01   29.98    4.92   39.97    2.25  434.65    3.45  484.61    1.36
  524.57    3.12  644.48    1.64  788.61    3.29  833.66    1.26  884.28    4.28
  899.27    2.28  969.21    1.97 1219.01    2.89 1308.37   -3.62 1408.39   -1.72
 1438.68     .67 1498.12   -3.98 1588.45   -4.73 1696.26     .19 2066.15    1.35
 2661.77   -3.41 2694.65   -2.28 2715.69    3.05 2787.74    1.33 2807.72    3.17
 2907.64    4.39 3357.27     2.9 3377.25    4.47 3382.25    6.95 3407.23    7.68
#Mann= 3 , 0 , 0
   19.98    .055       0  788.61    .025       0 2715.69    .055       0
Bank Sta=788.61,2715.69
XS Rating Curve= 0 ,0
Exp/Cntr(USF)=0.5,0.3
Exp/Cntr=0.5,0.3

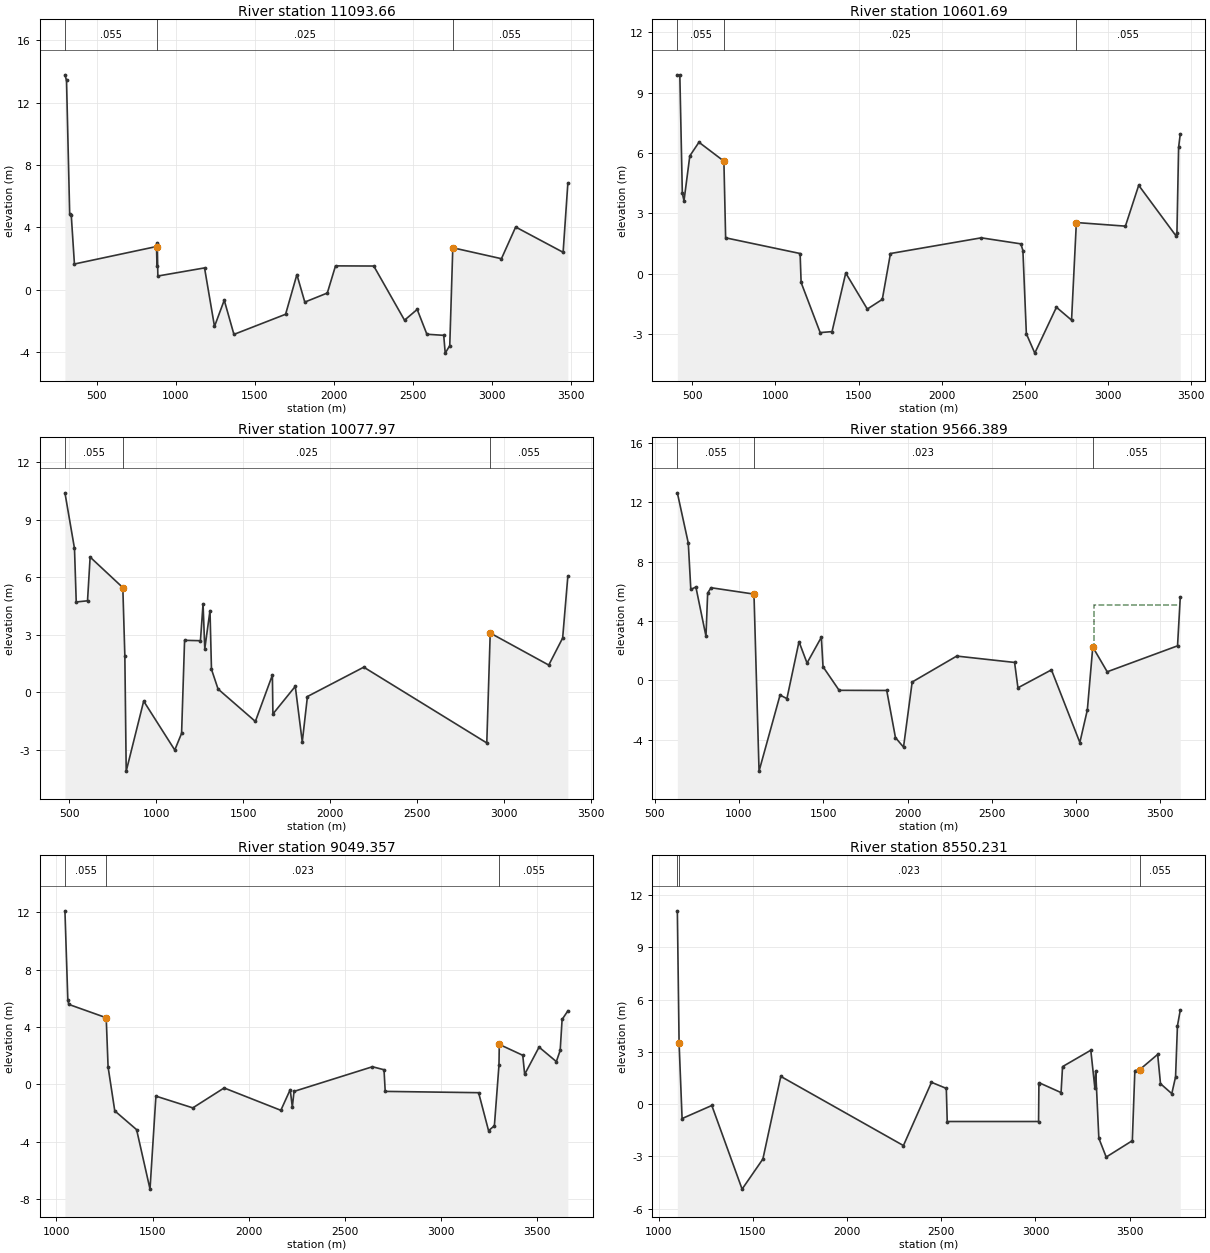
Type RM Length L Ch R = 1 ,11093.66,491.8,491.97,502.32
XS GIS Cut Line= 2
383800.1946876555907622.95499716385034.300776109 5904692.9446058
#Sta/Elev= 30
  299.93   13.78  309.93   13.42  329.93    4.88  339.93    4.78  359.92    1.66
  878.87    2.78  881.81    1.55  883.79    2.99  887.23     .89 1182.45    1.41
 1245.39   -2.34 1307.02    -.66 1368.24   -2.85 1694.85   -1.56 1766.19     .98
  1816.3    -.78 1958.54     -.2 2010.35    1.54 2252.25    1.53 2446.72   -1.94
 2526.73   -1.25 2588.05   -2.84 2694.48   -2.91 2703.86   -4.05 2732.63   -3.57
 2751.84     2.7 3059.32       2  3149.3    4.03 3449.24    2.41 3479.23    6.84
#Mann= 3 , 0 , 0
  299.93    .055       0  878.87    .025       0 2751.84    .055       0
Bank Sta=878.87,2751.84
XS Rating Curve= 0 ,0
Exp/Cntr(USF)=0.5,0.3
Exp/Cntr=0.5,0.3

Type RM Length L Ch R = 1 ,10601.69,526.02,523.72,530.89
XS GIS Cut Line= 2
384293.2460566355907719.28759255385467.0402656825904932.46954074
#Sta/Elev= 30
  409.86    9.88  424.85    9.85  439.84    3.99  449.84    3.62  484.83    5.85
  539.81    6.53  689.76    5.59  700.17    1.78 1148.02       1 1154.09    -.44
  1268.7   -2.93    1340   -2.88 1422.37     .03 1552.05   -1.76 1642.12   -1.28
 1691.26       1 2237.27    1.78 2475.53    1.48 2487.58    1.15  2508.4   -2.99
 2559.13   -3.95  2689.2   -1.67 2780.12   -2.31 2809.01    2.54 3103.91    2.36
 3183.88    4.39  3408.8    1.87  3413.8    2.04  3423.8    6.28  3433.8    6.94
#Mann= 3 , 0 , 0
  409.86    .055       0  689.76    .025       0 2809.01    .055       0
Bank Sta=689.76,2809.01
XS Rating Curve= 0 ,0
Exp/Cntr(USF)=0.5,0.3
Exp/Cntr=0.5,0.3

Type RM Length L Ch R = 1 ,10077.97,521.17,511.58,513.31
XS GIS Cut Line= 2
384795.2810404965907873.63267348 385917.752832965905208.66400365
#Sta/Elev= 30
  474.46    10.4   529.4     7.5  539.39    4.71  604.31    4.77   619.3    7.05
  807.31    5.46  818.93     1.9  826.78   -4.11  927.22    -.46 1105.96   -3.01
 1145.18   -2.14 1162.38    2.71 1253.58    2.69 1268.56    4.61 1278.55    2.27
 1308.51    4.26 1317.02     1.2 1354.91     .17 1569.39   -1.52 1667.29      .9
 1670.29   -1.13 1798.86     .31 1839.09   -2.59 1868.77    -.22 2192.76    1.31
 2900.01   -2.64 2919.77    3.09 3256.31    1.42 3336.22    2.83 3366.18    6.06
#Mann= 3 , 0 , 0
  474.46    .055       0  807.31    .025       0 2919.77    .055       0
Bank Sta=807.31,2919.77
XS Rating Curve= 0 ,0
Exp/Cntr(USF)=0.5,0.3
Exp/Cntr=0.5,0.3

Type RM Length L Ch R = 1 ,9566.389,526.44,517.03,518.5
XS GIS Cut Line= 2
 385296.612877025907995.23420049386454.6404151235905245.84921144
#Sta/Elev= 30
  634.42   12.65  699.36    9.26  714.35    6.13  744.32     6.3  804.26    2.98
  814.25    5.89  834.24    6.25    1089    5.82 1119.08   -6.12 1243.67    -.99
 1284.32   -1.23 1356.07    2.61 1403.71    1.17 1488.64    2.91 1498.63     .92
 1594.13    -.67 1876.51    -.68 1928.28   -3.86 1976.05    -4.5 2027.41    -.11
 2291.75    1.64 2634.89    1.21 2654.81     -.5  2853.6     .71 3022.05   -4.19
 3066.55   -1.99 3098.76    2.25  3184.3     .58 3601.54    2.33 3617.74    5.61
#Mann= 3 , 0 , 0
  634.42    .055       0    1089    .023       0 3098.76    .055       0
#XS Ineff= 2 , 0
                         3104.65            5.08
Permanent Ineff=
       F       F
Bank Sta=1089,3098.76
XS Rating Curve= 0 ,0
Exp/Cntr(USF)=0.5,0.3
Exp/Cntr=0.5,0.3

Type RM Length L Ch R = 1 ,9049.357,354.9,499.13,661.51
XS GIS Cut Line= 2
385883.6950816455907926.49353693386899.7105420385905514.27323009
#Sta/Elev= 30
 1043.99    12.1 1058.97    5.91 1063.97    5.57 1258.78    4.64 1268.55    1.21
 1303.36   -1.86 1416.97   -3.17 1486.76   -7.32 1517.45    -.83 1709.48   -1.65
  1872.4    -.26 2167.67   -1.82 2216.36    -.38 2227.44   -1.59 2236.34     -.5
 2644.43    1.22 2704.67    1.01 2710.79     -.5 3196.95    -.59 3248.71   -3.24
 3279.04    -2.9  3302.9    1.33 3304.57    2.78 3426.67    2.02 3436.66     .69
 3511.59    2.59  3601.5    1.58 3621.48    2.36 3631.47    4.52 3661.44    5.12
#Mann= 3 , 0 , 0
 1043.99    .055       0 1258.78    .023       0 3304.57    .055       0
Bank Sta=1258.78,3304.57
XS Rating Curve= 0 ,0
Exp/Cntr(USF)=0.5,0.3
Exp/Cntr=0.5,0.3

Type RM Length L Ch R = 1 ,8550.231,401.22,484.88,570.88
XS GIS Cut Line= 2
386252.8336119025908104.28574356387465.3059809445905726.79048895
#Sta/Elev= 30
  1099.5   11.09 1108.77     3.5 1124.65    -.83 1282.46    -.08 1443.08   -4.88
 1553.51   -3.15 1648.26    1.59 2299.18   -2.38 2448.08    1.25 2526.77      .9
 2531.65      -1 3016.34      -1 3018.12    1.14 3020.37    1.22 3135.74     .66
 3143.58    2.15 3293.51    3.09 3315.13     .92 3319.51     1.9 3336.26   -1.96
 3375.21   -3.04 3513.83    -2.1  3527.3    1.91 3553.39    1.98 3648.35    2.85
 3663.35    1.17 3723.32      .6 3743.31    1.56 3753.31    4.49  3768.3    5.39
#Mann= 3 , 0 , 0
  1099.5    .055       0 1108.77    .023       0 3553.39    .055       0
Bank Sta=1108.77,3553.39
XS Rating Curve= 0 ,0
Exp/Cntr(USF)=0.5,0.3
Exp/Cntr=0.5,0.3

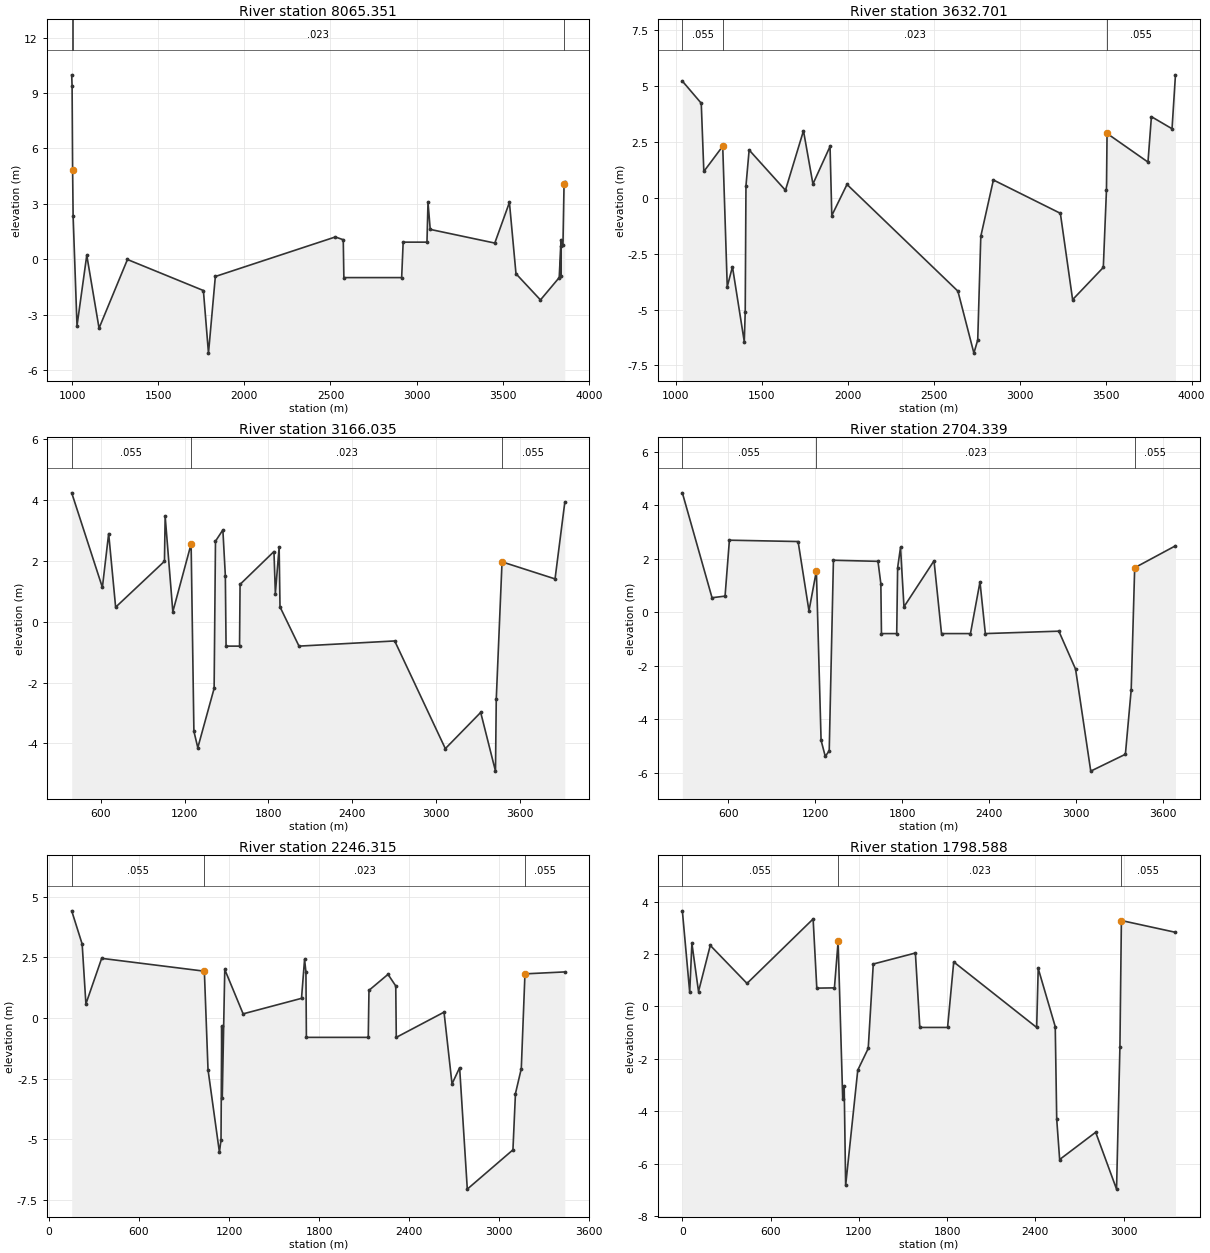
Type RM Length L Ch R = 1 ,8065.351,440.96,519.76,595.84
XS GIS Cut Line= 2
386564.0103795195908433.80417394387964.1980761895905936.22034573
#Sta/Elev= 30
  997.45    9.98  999.76    9.35 1002.73    4.85 1005.73    2.32 1028.28   -3.61
 1084.99     .21 1156.31   -3.74 1321.15    -.02 1762.15    -1.7 1791.68   -5.09
 1831.54    -.94 2528.16     1.2 2574.33    1.05 2577.82      -1 2913.43      -1
 2922.13     .92 3060.44     .92 3066.35    3.08 3079.25    1.61 3454.16     .87
 3539.14    3.07 3577.24    -.79 3719.38   -2.21 3828.24      -1 3837.38     .71
 3837.43    -.92 3837.63    1.05 3849.92     .74 3856.35    4.07 3860.76    4.16
#Mann= 3 , 0 , 0
  997.45    .055       0 1002.73    .023       0 3856.35    .055       0
Bank Sta=1002.73,3856.35
XS Rating Curve= 0 ,0
Exp/Cntr(USF)=0.5,0.3
Exp/Cntr=0.5,0.3

Type RM Length L Ch R = 1 ,3632.701,300.31,466.67,610.79
XS GIS Cut Line= 2
390599.5966915445910350.16917659391933.7067771495907812.47081517
#Sta/Elev= 30
 1038.91    5.21  1148.8    4.22 1163.78    1.17 1273.62     2.3 1299.91   -3.98
  1330.2   -3.09 1398.96   -6.44 1404.43   -5.09 1408.77     .53 1427.19    2.13
 1638.28     .33 1743.17    2.99 1798.12     .61 1897.54    2.29 1907.79     -.8
  1996.1     .59    2641   -4.18 2733.99   -6.95 2756.27   -6.36 2774.08   -1.73
 2847.29     .79 3236.67     -.7  3307.9   -4.56 3486.37   -3.12 3504.78     .36
 3508.17    2.87 3746.08    1.59 3766.05    3.62 3885.93    3.08 3905.91    5.49
#Mann= 3 , 0 , 0
 1038.91    .055       0 1273.62    .023       0 3508.17    .055       0
Bank Sta=1273.62,3508.17
XS Rating Curve= 0 ,0
Exp/Cntr(USF)=0.5,0.3
Exp/Cntr=0.5,0.3

Type RM Length L Ch R = 1 ,3166.035,68.41,461.7,992
XS GIS Cut Line= 2
 390558.187221075911092.08614936392442.0912198995908101.93129383
#Sta/Elev= 30
  389.91    4.24  609.85    1.13  654.84     2.9  704.83     .48 1054.74    1.99
 1059.74    3.47 1114.73     .33 1245.82    2.56 1265.75    -3.6 1293.72   -4.14
 1410.68   -2.19 1420.43    2.65 1473.37    3.02 1491.07    1.52  1496.3     -.8
 1592.88     -.8 1596.63    1.23 1839.55    2.31 1849.55     .93 1876.68    2.46
 1882.83     .49 2019.01     -.8 2704.89    -.63 3067.76   -4.17 3321.18   -2.98
 3427.21   -4.91 3432.73   -2.55 3474.16    1.97 3854.07    1.41 3924.05    3.93
#Mann= 3 , 0 , 0
  389.91    .055       0 1245.82    .023       0 3474.16    .055       0
Bank Sta=1245.82,3474.16
XS Rating Curve= 0 ,0
Exp/Cntr(USF)=0.5,0.3
Exp/Cntr=0.5,0.3

Type RM Length L Ch R = 1 ,2704.339,128.41,458.02,614.94
XS GIS Cut Line= 5
390557.5089563065911223.56462229      390827.651     5910815.629
     391054.1582    5910597.9076     392772.7882    5908945.9397
     392927.3156    5908797.4061
#Sta/Elev= 30
  284.58    4.46  489.28     .54  579.14      .6   609.1    2.69 1083.05    2.64
    1158     .05 1209.06    1.54 1241.56   -4.79 1270.54   -5.39 1297.72   -5.18
 1326.74    1.94 1634.07     1.9 1653.89    1.06    1658     -.8  1763.3     -.8
 1769.59    1.66 1789.49    2.42 1813.31      .2 2020.62    1.92 2072.28     -.8
    2272     -.8 2337.72    1.13 2374.67     -.8 2881.73    -.71 2997.17   -2.13
  3101.8   -5.94 3340.77   -5.31 3380.81    -2.9 3404.89    1.66 3686.21    2.48
#Mann= 3 , 0 , 0
  284.58    .055       0 1209.06    .023       0 3404.89    .055       0
Bank Sta=1209.06,3404.89
XS Rating Curve= 0 ,0
Exp/Cntr(USF)=0.5,0.3
Exp/Cntr=0.5,0.3

Type RM Length L Ch R = 1 ,2246.315,201.07,447.73,605.77
XS GIS Cut Line= 5
390594.0541738285911398.76487304     390604.7077    5911382.2168
     391119.4203    5910977.8704     393002.1305    5909498.8561
       393171.52    5909365.7876
#Sta/Elev= 30
  152.49    4.42  222.14    3.05  247.12     .58  352.04    2.46 1035.91    1.93
 1060.28   -2.13  1136.3   -5.54 1146.87   -5.02 1151.37    -.35 1155.11   -3.31
 1171.88       2 1294.11     .17 1682.95     .81 1703.29    2.42 1712.37    1.89
 1715.38     -.8 2127.38     -.8 2132.15    1.14 2258.94     1.8 2310.52    1.32
 2314.03     -.8 2632.03     .24 2685.18   -2.72 2735.84   -2.05 2786.97   -7.06
 3090.88   -5.44  3107.6   -3.12 3146.49   -2.09 3170.91    1.82  3436.3     1.9
#Mann= 3 , 0 , 0
  152.49    .055       0 1035.91    .023       0 3170.91    .055       0
Bank Sta=1035.91,3170.91
XS Rating Curve= 0 ,0
Exp/Cntr(USF)=0.5,0.3
Exp/Cntr=0.5,0.3

Type RM Length L Ch R = 1 ,1798.588,304.53,463.59,591.06
XS GIS Cut Line= 2
     390619.9044    5911599.3556     393499.5249     5909881.113
#Sta/Elev= 30
       0    3.65   49.96     .54   64.95    2.41  109.91     .57  189.85    2.33
  439.64     .88  889.28    3.34  914.26      .7 1034.16     .71 1059.14    2.48
 1090.51   -3.53 1100.51   -3.04 1110.43   -6.83 1192.81   -2.43 1263.96    -1.6
 1298.26    1.62 1584.67    2.04  1614.8     -.8 1803.58     -.8 1845.37     1.7
 2409.38     -.8 2419.93    1.45 2535.72    -.77 2545.77    -4.3 2565.72   -5.84
 2810.65    -4.8 2952.61   -6.97  2975.6   -1.53 2985.54    3.28 3353.29    2.83
#Mann= 3 , 0 , 0
       0    .055       0 1059.14    .023       0 2985.54    .055       0
Bank Sta=1059.14,2985.54
XS Rating Curve= 0 ,0
Exp/Cntr(USF)=0.5,0.3
Exp/Cntr=0.5,0.3

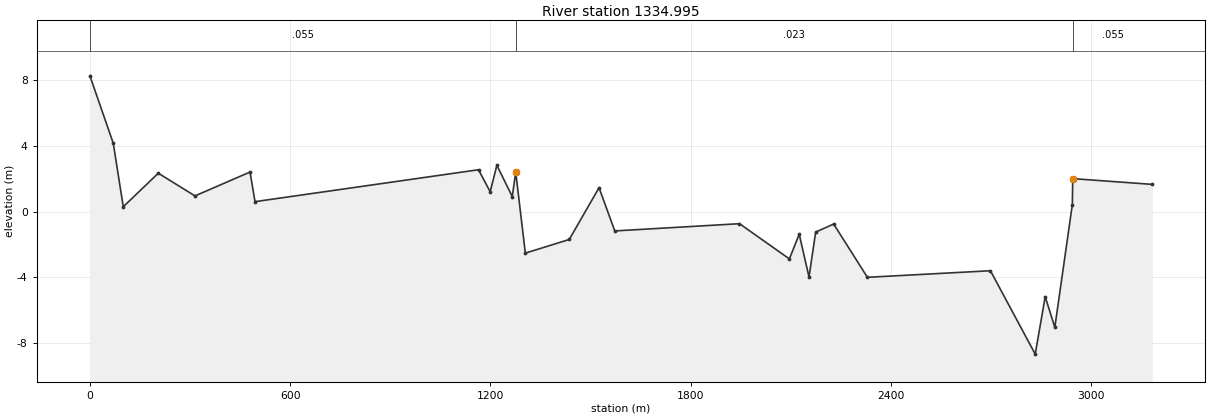
Type RM Length L Ch R = 1 ,1334.995,253.1,460.22,569.19
XS GIS Cut Line= 2
     390733.8232    5911863.2676     393595.2788    5910467.9192
#Sta/Elev= 30
       0    8.26   69.97    4.16   99.96      .3  204.91    2.34  314.86     .96
  479.79    2.41  494.79     .61  1164.5    2.55 1199.48    1.21 1219.47    2.82
  1265.6     .92 1276.04     2.4 1304.79   -2.52 1436.39   -1.69 1525.65    1.46
 1572.79   -1.17 1946.52    -.73 2096.06   -2.87 2125.52   -1.37 2154.84   -3.97
 2174.77   -1.24 2228.71    -.75 2329.86   -3.99 2698.49   -3.59  2832.7   -8.66
 2862.63   -5.17 2891.47   -7.03 2943.95     .43 2945.11    2.01 3183.54    1.66
#Mann= 3 , 0 , 0
       0    .055       0 1276.04    .023       0 2945.11    .055       0
Bank Sta=1276.04,2945.11
XS Rating Curve= 0 ,0
Exp/Cntr(USF)=0.5,0.3
Exp/Cntr=0.5,0.3

River Reach=Mud Lake A      ,Main A

River Reach=Mud Lake B      ,Main

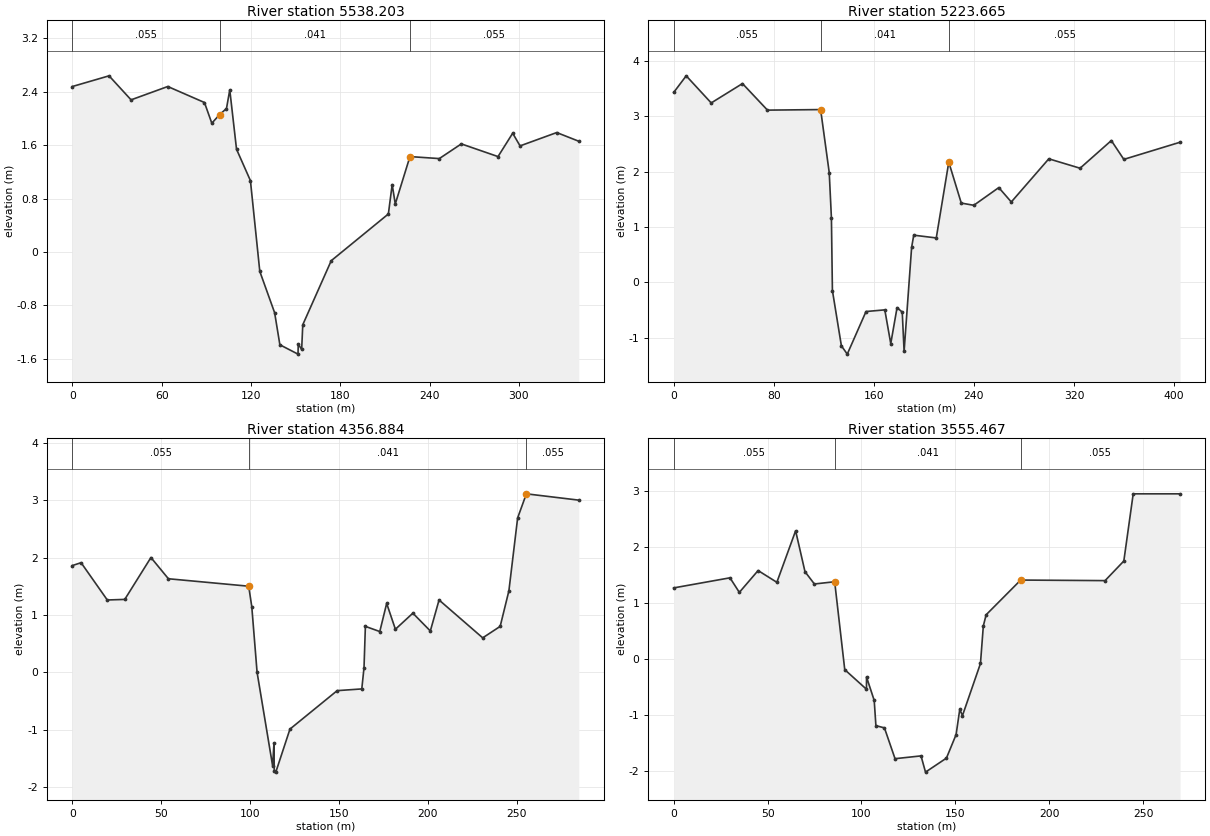
Type RM Length L Ch R = 1 ,5538.203,369.68,314.54,237.82
XS GIS Cut Line= 2
     394281.4992    5908272.3662     394132.0093    5908577.9606
#Sta/Elev= 30
       0    2.48   24.65    2.64   39.44    2.28    64.1    2.48   88.75    2.24
   93.68    1.93   98.97    2.06  103.54    2.15  105.75    2.43  110.29    1.54
  119.62    1.07  125.92    -.29  135.89    -.91  139.41   -1.39  151.59   -1.53
  151.76   -1.38  154.05   -1.46  154.79   -1.09  173.92    -.13   212.3     .57
  214.85    1.01  216.94     .72   226.8    1.43  246.52     1.4  261.31    1.62
  285.96    1.43  295.82    1.78  300.76    1.59  325.41    1.79   340.2    1.66
#Mann= 3 , 0 , 0
       0    .055       0   98.97    .041       0   226.8    .055       0
Bank Sta=98.97,226.8
XS Rating Curve= 0 ,0
Exp/Cntr=0.3,0.1

Type RM Length L Ch R = 1 ,5223.665,548.39,437.64,252.47
XS GIS Cut Line= 2
     393920.3422    5908163.8868     393915.0506    5908568.7001
#Sta/Elev= 30
       0    3.43      10    3.73   29.99    3.24   54.98    3.59   74.97    3.11
  117.46    3.12  124.35    1.98  126.09    1.16  126.88    -.15  134.06   -1.15
  138.76    -1.3  153.75    -.53  168.77     -.5  173.53   -1.11  178.56    -.46
  182.71    -.54   184.2   -1.25  190.21     .63  191.91     .85  209.92      .8
  219.92    2.17  229.91    1.43  239.91    1.39   259.9    1.71   269.9    1.45
  299.89    2.23  324.88    2.06  349.87    2.56  359.87    2.22  404.85    2.53
#Mann= 3 , 0 , 0
       0    .055       0  117.46    .041       0  219.92    .055       0
Bank Sta=117.46,219.92
XS Rating Curve= 0 ,0
Exp/Cntr=0.3,0.1

Type RM Length L Ch R = 1 ,4356.884,981.54,801.42,578.46
XS GIS Cut Line= 2
     393217.1577    5908851.1169     393465.6019    5908990.8172
#Sta/Elev= 30
       0    1.86    4.91    1.91   19.66    1.26   29.49    1.27   44.23       2
   54.06    1.63   99.26     1.5     101    1.14  103.97       0  112.72   -1.63
  113.47   -1.24  113.65   -1.72  114.51   -1.74  122.48    -.99  149.05    -.32
  162.91    -.29  164.16     .08  164.93      .8  173.04     .71  176.91     1.2
  181.83     .75  191.66    1.03  201.49     .72   206.4    1.26  230.97      .6
   240.8      .8  245.71    1.42  250.63    2.69  255.54    3.11  285.03       3
#Mann= 3 , 0 , 0
       0    .055       0   99.26    .041       0  255.54    .055       0
Bank Sta=99.26,255.54
XS Rating Curve= 0 ,0
Exp/Cntr=0.3,0.1

Type RM Length L Ch R = 1 ,3555.467,174.93,406.42,96.08
XS GIS Cut Line= 2
     393771.1963    5909544.0621     393864.0652    5909290.8553
#Sta/Elev= 30
       0    1.27   29.97    1.45   34.96    1.19   44.95    1.58   54.94    1.37
   64.93    2.29   69.92    1.56   74.92    1.34   85.73    1.38    91.1    -.19
  102.67    -.54  102.69    -.32  106.79    -.74  107.69   -1.19  112.24   -1.23
  117.88   -1.78  131.72   -1.73  134.11   -2.02  145.25   -1.77   150.4   -1.35
  152.35     -.9   153.8   -1.01  163.38    -.08   164.9     .59   166.4     .79
  184.79    1.41  229.74     1.4  239.73    1.75  244.73    2.95   269.7    2.95
#Mann= 3 , 0 , 0
       0    .055       0   85.73    .041       0  184.79    .055       0
Bank Sta=85.73,184.79
XS Rating Curve= 0 ,0
Exp/Cntr=0.3,0.1

River Reach=Mud Lake C      ,Main