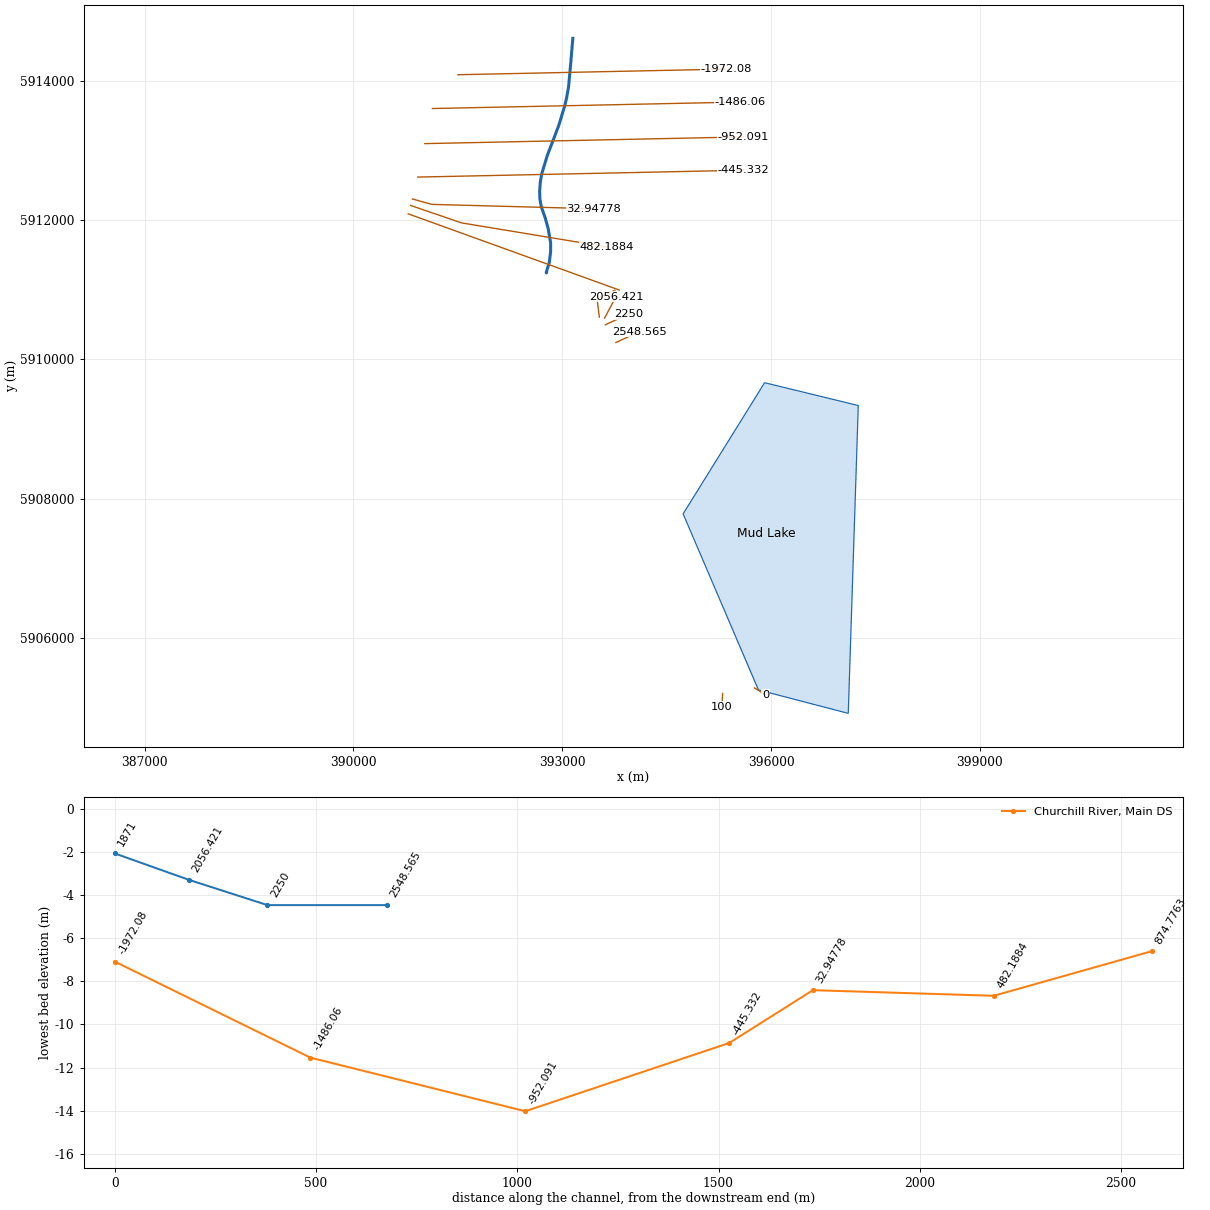
HEC-RAS study Churchill_Mapping.prj: Churchill River Flood Risk Mapping

--- Churchill_Mapping.g18 (geometry) --- (continued)

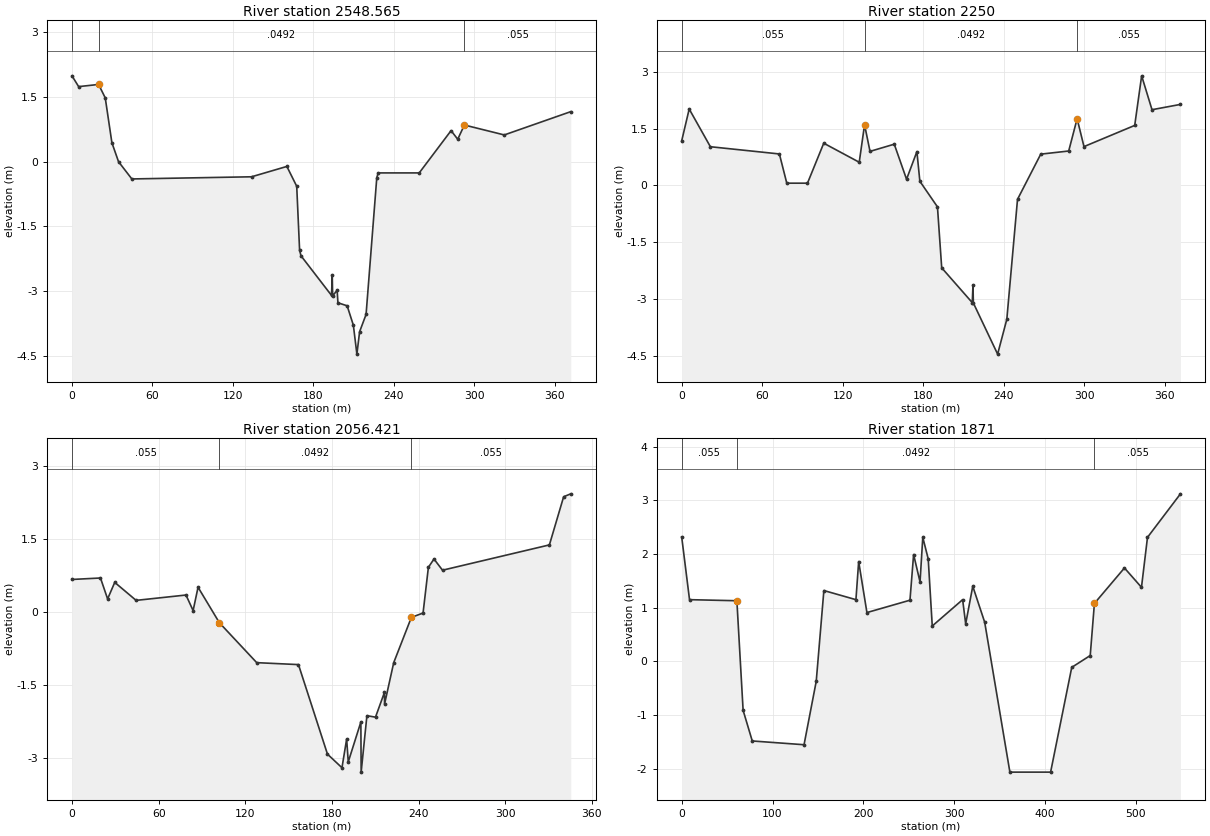
Type RM Length L Ch R = 1 ,2548.565,296.22,296.22,296.22
XS GIS Cut Line= 2
     393770.4026    5910241.7697      394107.747    5910398.1388
#Sta/Elev= 30
       0    1.99    4.96    1.74   19.83    1.79   24.79    1.48   29.75     .44
    34.7       0   44.62     -.4  133.86    -.35  160.18    -.11  167.53    -.57
  169.67   -2.05  170.69   -2.18  193.48    -3.1  194.01   -2.63   194.3   -3.11
  197.66   -2.98  198.24   -3.27  205.12   -3.34  209.75   -3.79  212.38   -4.46
  214.41   -3.94  219.23   -3.54  227.21    -.37   228.3    -.26  258.85    -.26
  282.59     .72  287.54     .52   292.5     .85  322.25     .62  371.82    1.16
#Mann= 3 , 0 , 0
       0    .055       0   19.83   .0492       0   292.5    .055       0
Bank Sta=19.83,292.5
XS Rating Curve= 0 ,0
Exp/Cntr=0.3,0.1

Type RM Length L Ch R = 1 ,2250    ,194.53,194.53,194.53
XS GIS Cut Line= 2
393618.4152793485910496.16980559393955.7596793485910652.53890559
#Sta/Elev= 30
       0   1.173   5.604   2.015    21.4   1.019  72.839    .828   78.35    .056
  93.781    .056 105.905   1.112 132.358    .609 136.323     1.6 140.392    .896
 158.467   1.086 167.629     .16 175.344     .89 177.549    .107  190.67    -.57
  193.83   -2.18  216.62    -3.1  217.15   -2.63  217.44   -3.11  235.52   -4.46
  242.37   -3.54  250.35    -.37 267.669    .823 288.506    .906 294.781   1.759
 299.894   1.022 337.708   1.582  342.88   2.892 350.595   1.997 371.823   2.137
#Mann= 3 , 0 , 0
       0    .055       0 136.323   .0492       0 294.781    .055       0
Bank Sta=136.323,294.781
XS Rating Curve= 0 ,0
Exp/Cntr=0.3,0.1

Type RM Length L Ch R = 1 ,2056.421,185,185,185
XS GIS Cut Line= 2
393607.8293380855910591.91434684393770.8354096455910900.42248424
#Sta/Elev= 30
       0     .67   19.74      .7   24.67     .27   29.61     .61   44.41     .24
   78.95     .35   83.88     .03    87.3     .51  102.08    -.22  127.93   -1.04
  156.83   -1.08  176.91   -2.92  186.96    -3.2   190.2   -2.61  191.31   -3.08
  200.04   -2.26  200.24   -3.29  204.23   -2.13  210.18   -2.16  216.39   -1.65
  216.46   -1.89  222.79   -1.04  235.01    -.11  243.11    -.02   246.8     .92
  250.68    1.09  256.58     .86  330.59    1.38  340.46    2.37   345.4    2.43
#Mann= 3 , 0 , 0
       0    .055       0  102.08   .0492       0  235.01    .055       0
Bank Sta=102.08,235.01
XS Rating Curve= 0 ,0
Exp/Cntr=0.3,0.1

Type RM Length L Ch R = 1 ,1871    ,0,0,0
XS GIS Cut Line= 3
393532.8903050245910607.23035359393498.9762897065910872.52547194
393754.4351270725910991.04652588
#Sta/Elev= 30
       0    2.32    8.64    1.15   60.76    1.13   67.63    -.91    77.7   -1.48
   134.7   -1.55  148.12    -.37  156.53    1.32  191.82    1.15  194.84    1.86
  203.92     .91   251.3    1.14  255.31    1.99  262.39    1.48  265.41    2.31
  271.38    1.91  275.84     .66  309.28    1.15  312.63      .7  320.43     1.4
  333.56     .73   361.3   -2.06  406.12   -2.06  429.39    -.11  449.73     .11
  454.34    1.08  487.41    1.74  506.15    1.38  512.77    2.31  549.08    3.12
#Mann= 3 , 0 , 0
       0    .055       0   60.76   .0492       0  454.34    .055       0
Bank Sta=60.76,454.34
XS Rating Curve= 0 ,0
Exp/Cntr=0.3,0.1

River Reach=Mud Lake In     ,In

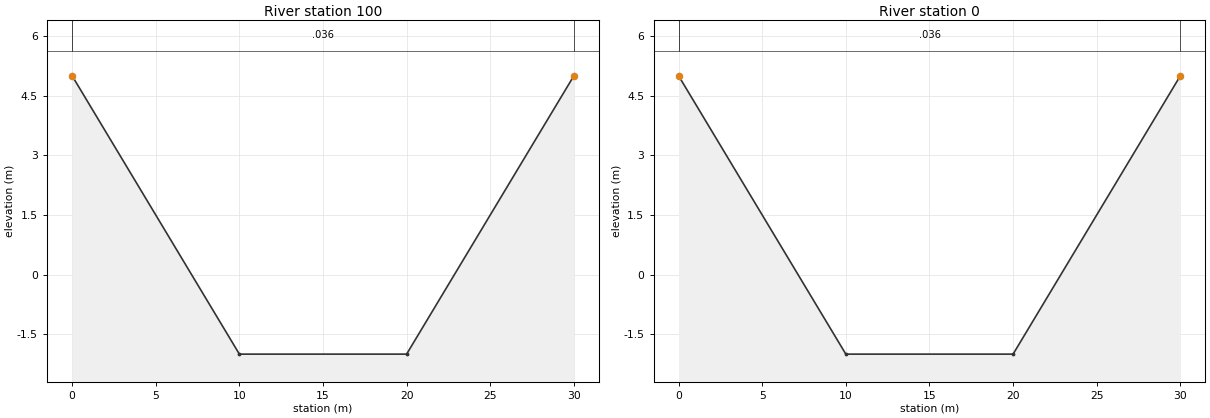
Type RM Length L Ch R = 1 ,100     ,100,100,100
XS GIS Cut Line= 5
395304.3067021795905197.93905802395304.3067021795905197.93905802
395299.2126349185905104.54782489395294.1185676575905011.15659176
395294.1185676575905011.15659176
#Sta/Elev= 4
       0       5      10      -2      20      -2      30       5
#Mann= 3 , 0 , 0
       0     .03       0       0    .036       0      30     .03       0
Bank Sta=0,30
XS Rating Curve= 0 ,0
Exp/Cntr=0.3,0.1

Type RM Length L Ch R = 1 ,0       ,0,0,0
XS GIS Cut Line= 5
 395762.093200675905278.70280939 395762.093200675905278.70280939
395840.9106316165905228.34722851395919.7280625625905177.99164763
395919.7280625625905177.99164763
#Sta/Elev= 4
       0       5      10      -2      20      -2      30       5
#Mann= 3 , 0 , 0
       0     .03       0       0    .036       0      30     .03       0
Bank Sta=0,30
XS Rating Curve= 0 ,0
Exp/Cntr=0.3,0.1

River Reach=Churchill River ,Main DS
Reach XY= 30
392769.8948848085911242.63821614392769.7238922575911242.46722359
     392772.3149     5911255.552     392814.3388    5911398.6122
      392832.745    5911550.1834     392832.5598    5911676.5487
     392796.5764    5911881.8658     392756.3596    5912027.9161
     392737.0326    5912083.6011     392727.0819    5912112.2715
      392720.153    5912132.2349     392707.4456    5912168.8477
392701.4818186035912185.34551994392697.9963241295912199.12185874
392695.8341739975912207.77045927     392695.2863    5912216.4103
      392688.594    5912242.6005     392681.5458     5912285.916
     392677.5666    5912326.4725     392674.8356    5912415.4487
     392684.1423    5912543.1765392703.5789864885912660.37382837
     392733.0904    5912758.8124     392786.0071    5912932.1148
     392949.1619    5913359.9371     393036.3696    5913645.8298
     393062.4973    5913758.3882     393090.6093    5913917.0282
     393119.7135     5914233.206     393151.7357    5914612.8969

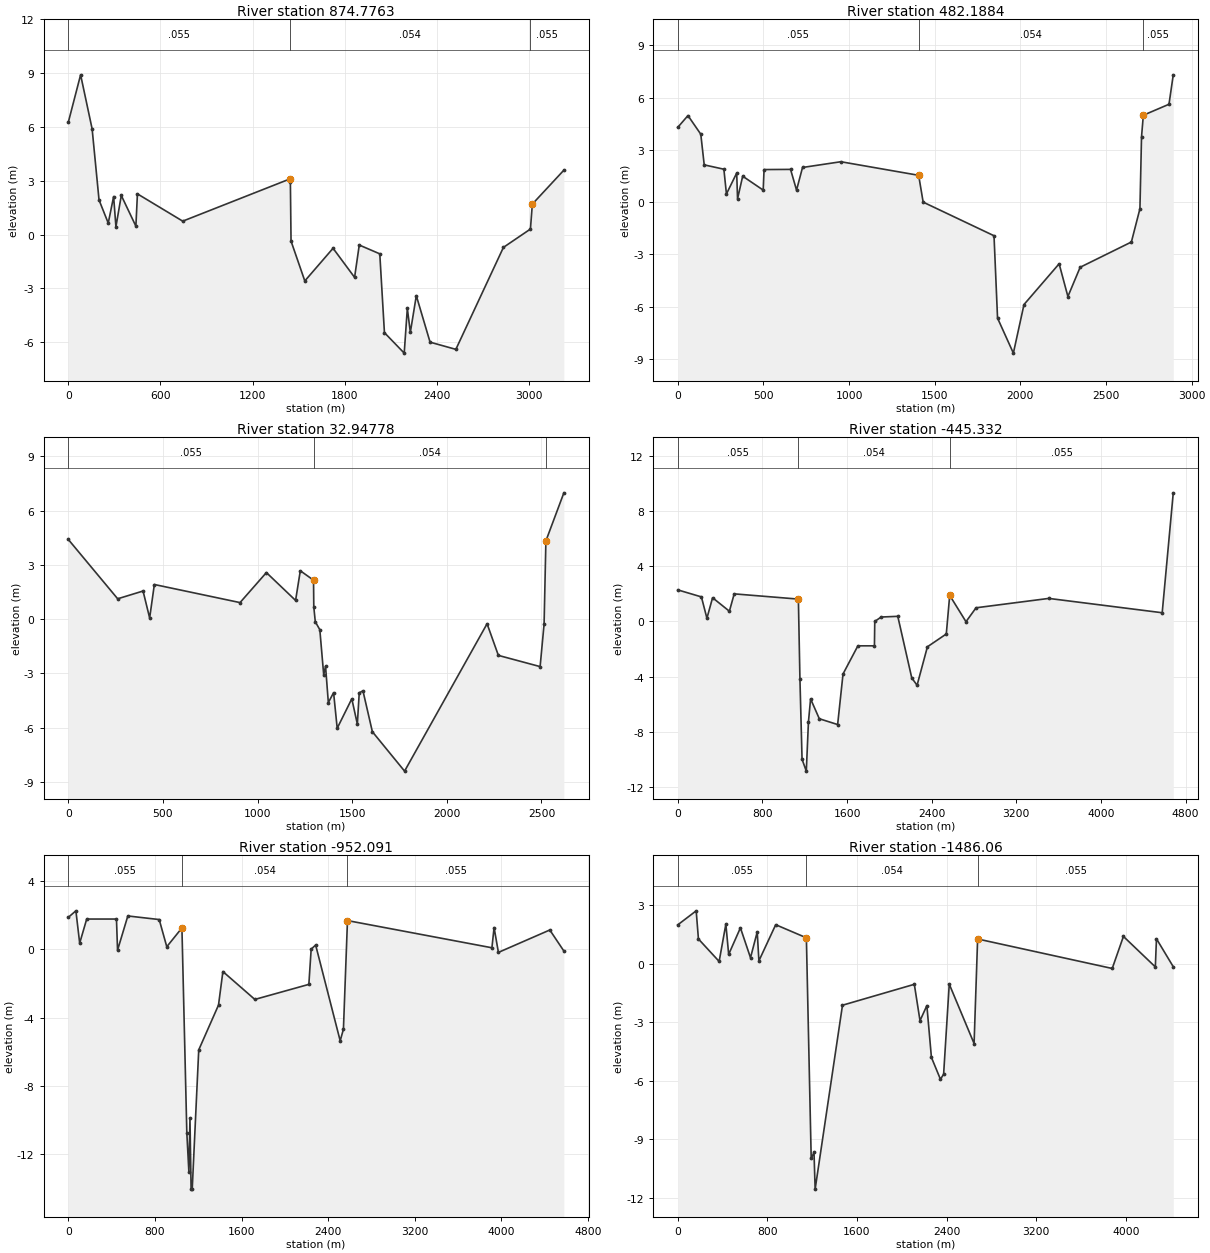
Type RM Length L Ch R = 1 ,874.7763,130.1,392.59,1051.87
XS GIS Cut Line= 2
     390785.9067    5912091.0588     393820.2728      5910995.65
#Sta/Elev= 30
       0    6.26   79.98     8.9  154.96    5.89  199.95    1.93  259.94     .64
  294.93    2.12  309.93     .44  344.92    2.18   439.9     .47   449.9    2.27
  744.83     .75 1444.97    3.11 1445.63    2.91  1449.9    -.36 1539.55   -2.58
 1723.42    -.76  1863.6   -2.38 1894.03    -.58 2027.62   -1.07 2057.93   -5.46
 2186.72    -6.6 2206.94   -4.11 2226.61   -5.44 2265.44    -3.4 2355.05   -5.99
 2522.92   -6.39 2832.65    -.71 3008.39     .31 3020.78     1.7 3226.03    3.59
#Mann= 3 ,-1 , 0
       0    .055       0 1445.63    .054       0 3008.39    .055       0
Bank Sta=1444.97,3020.78
XS Rating Curve= 0 ,0
Exp/Cntr(USF)=0.5,0.3
Exp/Cntr=0.5,0.3

Type RM Length L Ch R = 1 ,482.1884,112.67,449.24,807.63
XS GIS Cut Line= 5
     390821.6015    5912211.3718      391553.291    5911960.6071
     392048.4026     5911878.808     392049.5722    5911878.6148
393644.0986969595911615.17765598
#Sta/Elev= 30
       0    4.29   59.88    4.97  134.73     3.9  154.69    2.14  269.47    1.89
  284.44     .47  344.32    1.67  349.31     .19  379.25    1.49  499.01     .69
     504    1.87  658.69    1.88  693.63     .69  728.56    1.99  952.34    2.32
 1406.43    1.54 1432.73       0 1846.32   -1.93 1866.93   -6.66  1959.3   -8.67
 2021.33   -5.88 2226.43   -3.54 2277.58   -5.42 2349.14   -3.74 2648.16   -2.29
 2698.07    -.38 2707.39    3.75 2717.95    4.99 2867.68    5.62 2892.62    7.31
#Mann= 3 , 0 , 0
       0    .055       0 1406.43    .054       0 2717.95    .055       0
Bank Sta=1406.43,2717.95
XS Rating Curve= 0 ,0
Exp/Cntr(USF)=0.5,0.3
Exp/Cntr=0.5,0.3

Type RM Length L Ch R = 1 ,32.94778,207.75,207.75,207.75
XS GIS Cut Line= 5
     390848.0599    5912303.9762     391122.9355    5912226.9858
     392022.9791    5912202.7855     393444.9376     5912164.552
393454.9701555535912164.28224541
#Sta/Elev= 30
       0     4.4  260.85    1.12  394.89    1.55  429.71     .06  454.58    1.91
  907.26     .91 1046.54    2.57  1200.8    1.03 1225.75    2.67 1295.63    2.15
 1296.99     .67 1304.89    -.15 1328.88    -.59 1349.33   -3.08 1359.13   -2.61
 1373.84   -4.62 1401.63   -4.07 1420.65   -6.04 1497.82   -4.41 1527.11   -5.81
 1537.09   -4.08 1556.75   -3.97 1606.47   -6.23 1776.63   -8.41 2212.53    -.26
 2272.25   -2.01 2492.79   -2.63 2513.79    -.28 2523.36    4.32  2618.3    6.98
#Mann= 3 , 0 , 0
       0    .055       0 1295.63    .054       0 2523.36    .055       0
Bank Sta=1295.63,2523.36
XS Rating Curve= 0 ,0
Exp/Cntr(USF)=0.5,0.3
Exp/Cntr=0.5,0.3

Type RM Length L Ch R = 1 ,-445.332,503.69,506.76,490.08
XS GIS Cut Line= 2
     390922.1354    5912619.2117     395604.1073    5912717.8173
#Sta/Elev= 30
       0    2.29  223.91    1.78  276.06     .23   329.5    1.72  488.35     .74
   533.9       2  1140.3    1.62 1154.96   -4.16 1175.05     -10 1215.24  -10.86
 1235.39   -7.29 1255.77   -5.62 1338.17   -7.06 1511.34   -7.48 1562.29   -3.81
 1702.69   -1.77 1859.05   -1.77 1862.23       0 1922.54     .32 2079.76     .37
 2211.82    -4.1 2262.08   -4.63 2359.67   -1.84 2538.18    -.91 2570.34    1.89
 2724.33    -.02 2819.36     .99 3506.61    1.67 4578.46     .63 4683.01    9.33
#Mann= 3 , 0 , 0
       0    .055       0  1140.3    .054       0 2570.34    .055       0
Bank Sta=1140.3,2570.34
XS Rating Curve= 0 ,0
Exp/Cntr=0.3,0.1

Type RM Length L Ch R = 1 ,-952.091,534.3,533.97,511.38
XS GIS Cut Line= 2
     391024.7287    5913099.8707     395599.7588    5913196.2241
#Sta/Elev= 30
       0    1.86   69.94    2.24  104.91     .35  169.85    1.76  444.62    1.76
  454.61    -.06  549.52    1.94  839.28    1.73  909.21     .14 1049.09    1.24
  1094.3  -10.74 1113.27  -13.02 1123.35    -9.9 1133.78  -14.03 1144.23  -14.02
 1204.32   -5.89 1386.91   -3.27  1427.4   -1.31 1722.41   -2.94 2221.13   -2.06
 2242.52       0 2283.87     .24 2510.54   -5.36 2540.43   -4.68 2577.77    1.67
  3911.6     .08 3931.58    1.26 3971.55    -.19 4446.13    1.12 4576.01    -.11
#Mann= 3 , 0 , 0
       0    .055       0 1049.09    .054       0 2577.77    .055       0
Bank Sta=1049.09,2577.77
XS Rating Curve= 0 ,0
Exp/Cntr=0.3,0.1

Type RM Length L Ch R = 1 ,-1486.06,487.84,486.02,490.18
XS GIS Cut Line= 2
     391133.8455    5913604.0628     395556.5846    5913697.2088
#Sta/Elev= 30
       0    1.98  164.95     2.7  184.95    1.26  369.89     .11  429.88    2.02
  454.87     .47  559.84    1.83  649.81      .3  709.79    1.62  724.79     .14
  874.75    1.99 1148.59    1.32 1191.67   -9.97  1216.7   -9.66 1226.86  -11.54
 1470.92   -2.13 2112.22   -1.06 2162.92   -2.92 2224.21   -2.15 2264.84    -4.8
 2345.45   -5.92  2373.8   -5.66 2423.99   -1.05 2645.68   -4.09 2677.29    1.26
 3878.88    -.25 3978.85    1.39 4263.76    -.17 4273.76    1.27 4423.72    -.16
#Mann= 3 , 0 , 0
       0    .055       0 1148.59    .054       0 2677.29    .055       0
Bank Sta=1148.59,2677.29
XS Rating Curve= 0 ,0
Exp/Cntr=0.3,0.1

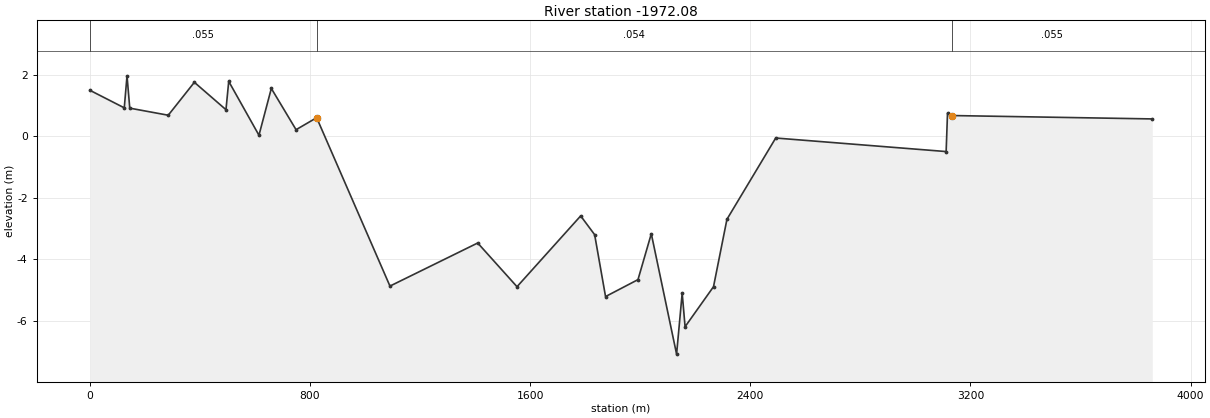
Type RM Length L Ch R = 1 ,-1972.08,100,100,100
XS GIS Cut Line= 2
      391501.249    5914089.8532     395361.2289    5914171.1471
#Sta/Elev= 30
       0    1.49  124.87     .92  134.85    1.96  144.84     .91  284.69     .68
  379.59    1.75  494.47     .86  504.46    1.78  614.34     .03  659.29    1.55
  749.19     .21  824.04      .6  1090.4   -4.87  1409.3   -3.47 1552.14   -4.89
  1783.5   -2.59 1834.26    -3.2 1873.89   -5.21 1991.78   -4.66 2040.17   -3.17
 2132.07   -7.08 2152.39    -5.1 2162.92   -6.19 2266.22   -4.89 2315.06    -2.7
 2492.31    -.06 3111.65     -.5 3116.64     .75 3132.86     .67 3860.84     .56
#Mann= 3 , 0 , 0
       0    .055       0  824.04    .054       0 3132.86    .055       0
Bank Sta=824.04,3132.86
XS Rating Curve= 0 ,0
Exp/Cntr=0.3,0.1

Storage Area=Mud Lake        ,396360.7636923,5907381.7871506
Storage Area Surface Line= 6
   394736.733584 5907779.6846083
  395907.3849677 5909664.4333359
  397253.6340588 5909336.6509485
  397109.6146895 5904912.8256111
  395818.8498631 5905249.7865669
   394736.733584 5907779.6846083
Storage Area Type= 0
Storage Area Area=8000
Storage Area Min Elev=-5
Storage Area Vol Elev= 1
               0

--- Churchill_Mapping.g19 (geometry) ---

Geom Title=Current Conditions - KGS LiDAR_n+30%
Program Version=4.10

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
Junct Name=J2
Junct Desc=, 0 , 0 ,-1 ,0
Up River,Reach=Mud Lake A      ,Main A
Up River,Reach=Mud Lake B      ,Main
Dn River,Reach=Mud Lake C      ,Main
Junc L&A=239.3,0
Junc L&A=256.52,0

Junct Name=J3
Junct Desc=, 0 , 0 ,-1 ,0
Up River,Reach=Churchill River ,Main
Up River,Reach=Mud Lake C      ,Main
Dn River,Reach=Churchill River ,Main DS
Junc L&A=460.87,
Junc L&A=832.64,

River Reach=Churchill River ,Main

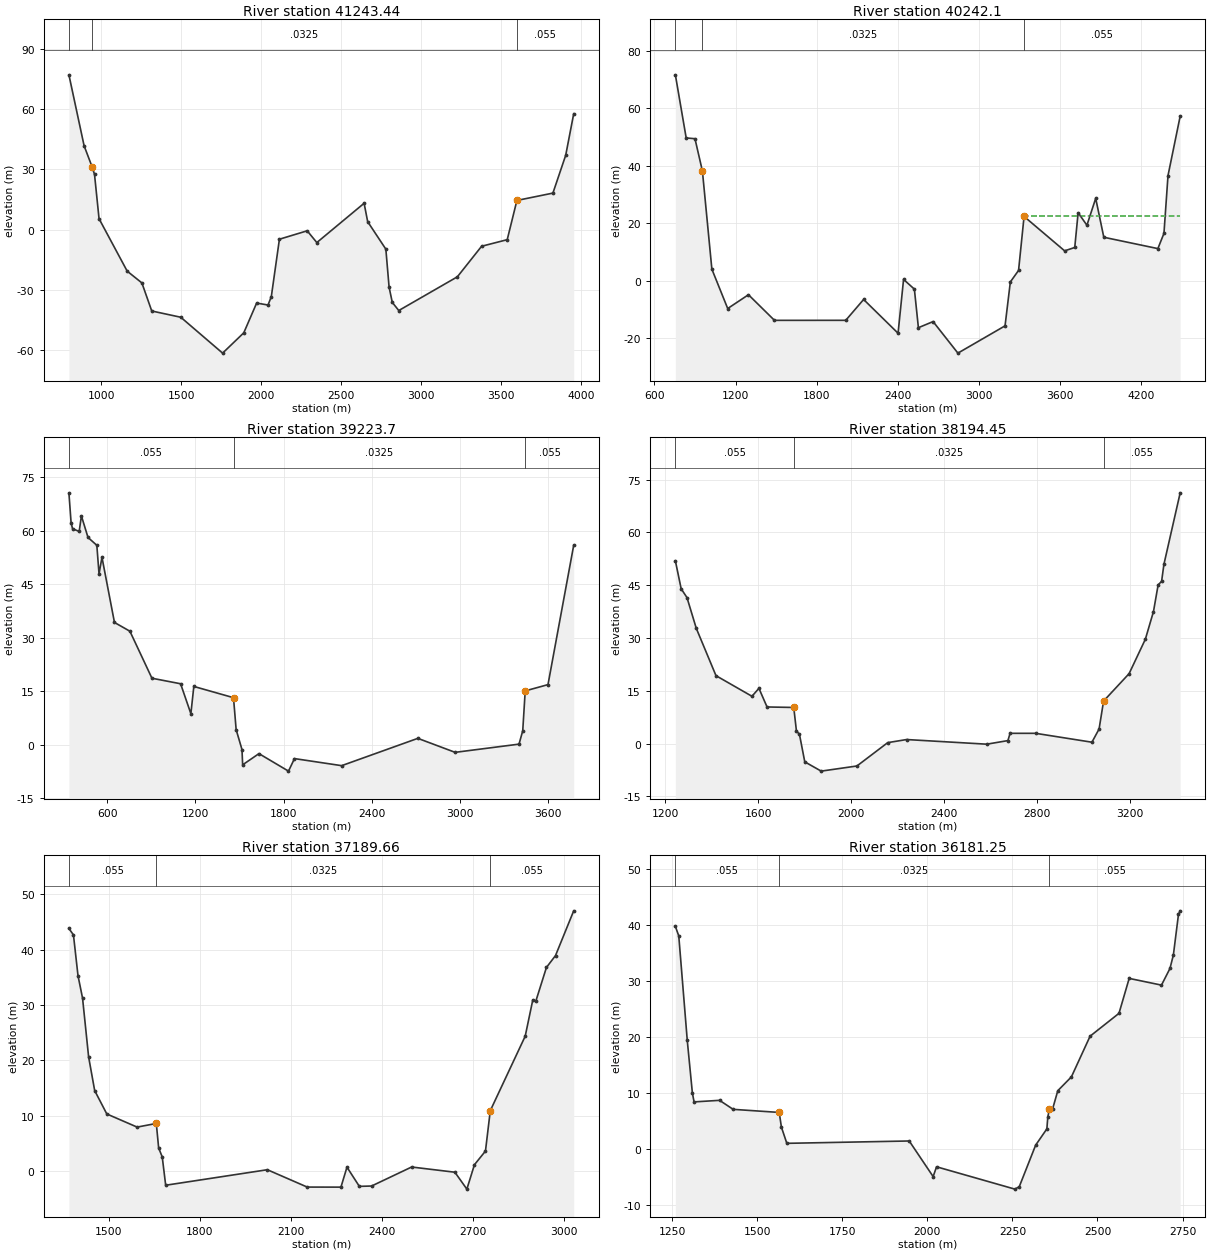
Type RM Length L Ch R = 1 ,41243.44,1199.65,1001.34,790.16
XS GIS Cut Line= 2
355551.9021897725903380.25918935355298.2267538125900237.71443768
#Sta/Elev= 30
  799.44   77.12  894.37   41.78  944.34   31.26  959.33   27.58  987.68    5.45
 1163.41  -20.66 1255.24  -26.53 1316.83  -40.51 1498.23  -43.63 1759.43   -61.5
 1891.64  -51.38 1971.99  -36.56 2043.03  -37.54 2063.54   -33.4 2114.18   -4.76
  2287.7    -.57 2347.85   -6.43 2643.14   13.14 2665.47    3.97 2778.97   -9.71
 2799.18  -28.64 2819.15  -36.23 2859.64  -40.28 3225.62  -23.48 3376.96   -8.27
 3536.99   -4.99 3597.47   14.55 3822.32   18.21 3902.26   37.05 3952.23   57.74
#Mann= 3 , 0 , 0
  799.44    .055       0  944.34   .0325       0 3597.47    .055       0
Bank Sta=944.34,3597.47
XS Rating Curve= 0 ,0
Exp/Cntr(USF)=0.3,0.1
Exp/Cntr=0.5,0.3

Type RM Length L Ch R = 1 ,40242.1 ,968.29,1018.41,1034.79
XS GIS Cut Line= 2
356665.7540205175903155.76013423356014.6894317675899481.03599879
#Sta/Elev= 30
  754.38    71.6  834.32   49.67  899.26    49.4  954.22   38.18 1024.16    4.08
 1141.25    -9.6 1294.67   -4.81 1486.99  -13.71 2013.92   -13.7 2146.03   -6.46
 2400.71  -18.19 2441.37     .51 2521.35   -2.87 2551.03  -16.26 2659.73  -14.14
 2843.13   -25.1 3191.64  -15.62 3230.76    -.37 3291.56    3.64 3332.28   22.39
 3632.03   10.44 3706.96   11.61 3731.94   23.69 3796.89   19.33 3861.84   28.68
 3921.79   15.16 4321.47   11.22 4366.43   16.51 4396.41   36.61 4486.34   57.23
#Mann= 3 , 0 , 0
  754.38    .055       0  954.22   .0325       0 3332.28    .055       0
#XS Ineff= 2 , 0
                         3331.54           22.41
Permanent Ineff=
       F       F
Bank Sta=954.22,3332.28
XS Rating Curve= 0 ,0
Exp/Cntr(USF)=0.3,0.1
Exp/Cntr=0.5,0.3

Type RM Length L Ch R = 1 ,39223.7 ,827.11,1029.24,1183.39
XS GIS Cut Line= 2
357644.9400931885903272.44553403357118.595832677 5899880.4101248
#Sta/Elev= 30
  339.76   70.56  354.75   62.12  364.75   60.49  409.72   59.75  424.71    64.1
  469.67   58.06  529.63   55.86  544.62   47.85  564.61   52.49  649.55   34.25
  754.48    31.8  904.37   18.63 1099.24   17.08 1169.19    8.69 1189.18   16.33
 1458.99   13.18 1476.97    4.23 1516.63   -1.34 1521.24   -5.62 1632.11   -2.49
 1832.97   -7.39 1873.58   -3.88 2194.44   -5.86 2712.49    1.79 2966.16   -2.13
 3400.49     .17  3425.8    3.91 3442.62   15.08 3597.51   16.84 3772.39   55.88
#Mann= 3 , 0 , 0
  339.76    .055       0 1458.99   .0325       0 3442.62    .055       0
#XS Ineff= 2 , 0
         1452.07   13.17
Permanent Ineff=
       F       F
Bank Sta=1458.99,3442.62
XS Rating Curve= 0 ,0
Exp/Cntr(USF)=0.3,0.1
Exp/Cntr=0.5,0.3

Type RM Length L Ch R = 1 ,38194.45,590.64,1004.79,1303.96
XS GIS Cut Line= 2
358373.0744874665902065.84526603358256.6761285735899895.87627662
#Sta/Elev= 30
  1243.9   51.94 1268.88   43.99 1293.86   41.49 1333.82   32.76 1418.75   19.29
 1573.61   13.43 1603.59   15.69 1638.56   10.39 1753.46   10.25 1765.02     3.6
 1778.18    2.58 1800.95   -5.21 1871.59   -7.85 2025.46   -6.39 2157.97     .25
 2239.49    1.13 2584.52    -.19 2675.39     .83 2684.79     2.9 2794.67     2.9
 3037.14     .37 3067.92    4.13 3087.28   12.07 3197.18   19.87 3267.12   29.65
 3302.09   37.53 3322.07   45.08 3337.06   46.12 3347.05   50.95 3416.99   71.27
#Mann= 3 , 0 , 0
  1243.9    .055       0 1753.46   .0325       0 3087.28    .055       0
Bank Sta=1753.46,3087.28
XS Rating Curve= 0 ,0
Exp/Cntr(USF)=0.3,0.1
Exp/Cntr=0.5,0.3

Type RM Length L Ch R = 1 ,37189.66,843.23,1008.41,1150.62
XS GIS Cut Line= 2
359167.6922901485901824.18651839359446.9824786115900183.87996252
#Sta/Elev= 30
 1369.11   43.82  1384.1   42.65 1399.09    35.3 1414.08   31.25 1434.07   20.65
 1454.06   14.57 1494.03   10.35 1593.97    7.98 1657.18    8.64 1664.93    4.22
 1676.74     2.6 1688.12   -2.51 2023.22     .29 2154.63   -2.84 2265.79   -2.85
 2285.66     .75 2326.42   -2.71 2366.79   -2.65 2498.76     .78 2641.36    -.16
 2680.87   -3.21 2705.79    1.19 2742.16    3.66 2758.04   10.94 2873.14   24.38
 2898.12   30.91 2908.12   30.69 2943.09   36.78 2973.07   38.93 3033.03      47
#Mann= 3 , 0 , 0
 1369.11    .055       0 1657.18   .0325       0 2758.04    .055       0
Bank Sta=1657.18,2758.04
XS Rating Curve= 0 ,0
Exp/Cntr(USF)=0.3,0.1
Exp/Cntr=0.5,0.3

Type RM Length L Ch R = 1 ,36181.25,885.13,1008.13,1123.83
XS GIS Cut Line= 2
360095.6836881055901918.51135192360503.7541469965900491.71876408
#Sta/Elev= 30
 1259.15   39.75 1269.14   38.05 1294.12   19.38 1309.11   10.01 1314.11     8.4
 1389.06    8.68 1429.03    7.07 1564.42    6.52 1570.89    3.89 1586.82       1
 1946.64    1.42 2016.94   -4.94 2026.95   -3.19 2257.19   -7.18 2270.07   -6.75
  2318.3     .68 2351.23    3.58 2354.05    5.73 2358.72    7.05  2368.4     7.2
 2383.39    10.4 2423.36   12.87 2478.32   20.14 2563.26   24.22 2593.24   30.46
 2688.18   29.26 2713.16   32.24 2723.15   34.64 2738.14   41.89 2743.14   42.53
#Mann= 3 , 0 , 0
 1259.15    .055       0 1564.42   .0325       0 2358.72    .055       0
Bank Sta=1564.42,2358.72
XS Rating Curve= 0 ,0
Exp/Cntr(USF)=0.3,0.1
Exp/Cntr=0.5,0.3

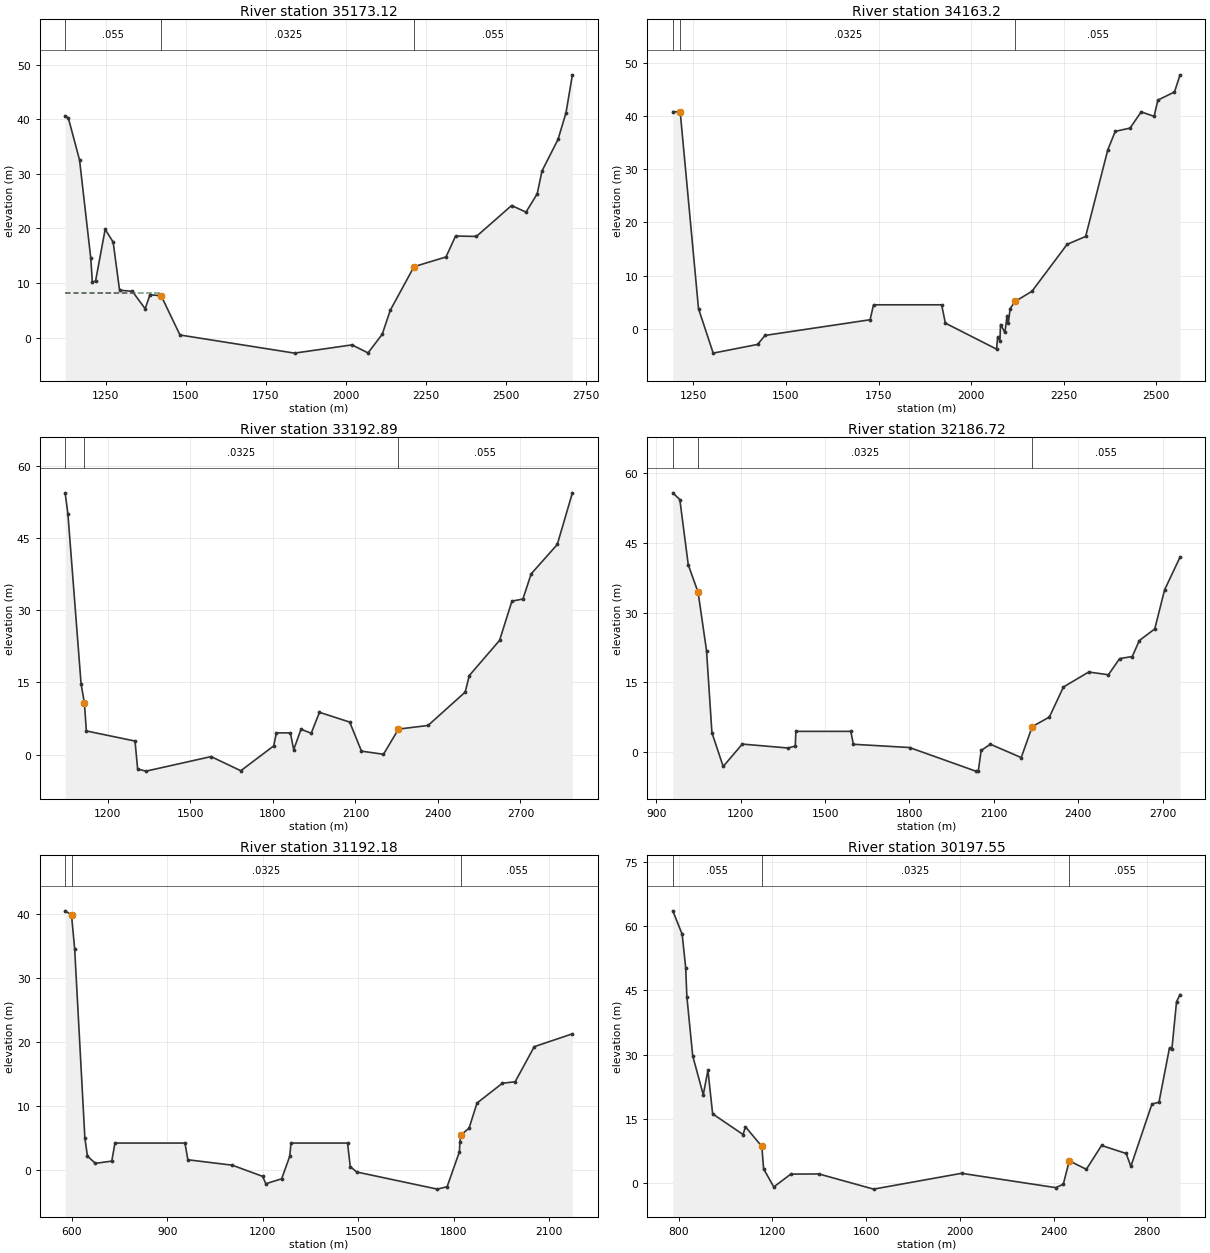
Type RM Length L Ch R = 1 ,35173.12,734.97,1009.92,1301.42
XS GIS Cut Line= 2
360970.3608625635902298.87858823 361529.021321395900817.96409063
#Sta/Elev= 30
 1123.44   40.61 1133.43    40.2 1168.38   32.51 1203.33   14.56 1208.32   10.16
 1218.31   10.34 1248.27   19.81 1273.23   17.49  1293.2    8.67 1333.15    8.47
 1373.09    5.28 1388.07    7.84 1423.02    7.66 1481.72     .47 1839.27   -2.85
 2018.55   -1.34 2068.51   -2.81 2112.77      .6 2137.88    4.99 2211.93   12.98
 2311.79   14.76 2341.75   18.59 2406.66   18.52 2516.51   24.18 2561.45   22.97
  2596.4   26.32 2611.38   30.51 2661.31   36.27 2686.28   41.16 2706.25   48.11
#Mann= 3 , 0 , 0
 1123.44    .055       0 1423.02   .0325       0 2211.93    .055       0
#XS Ineff= 2 , 0
          1418.6    8.09
Permanent Ineff=
       F       F
Bank Sta=1423.02,2211.93
XS Rating Curve= 0 ,0
Exp/Cntr(USF)=0.3,0.1
Exp/Cntr=0.5,0.3

Type RM Length L Ch R = 1 ,34163.2 ,971.99,970.31,998.23
XS GIS Cut Line= 2
361817.0489163785902605.56069662362535.0387920345901439.35483532
#Sta/Elev= 30
 1194.58   40.84 1214.57   40.77 1263.95    3.78 1303.62   -4.59 1423.55   -2.95
  1443.5   -1.26 1727.24    1.69 1736.52     4.5 1920.35     4.5 1930.51    1.05
 2068.78   -3.84  2071.5   -1.62 2077.66   -2.23 2079.42     .78 2091.27     -.7
 2096.72    2.32 2100.31     .99 2105.39     3.8 2119.25    5.15 2164.23    7.04
  2259.2   15.87 2309.19   17.36 2369.16   33.69 2389.16   37.13 2429.14   37.74
 2459.13   40.79 2494.12   39.95 2504.12      43  2549.1   44.54  2564.1   47.76
#Mann= 3 , 0 , 0
 1194.58    .055       0 1214.57   .0325       0 2119.25    .055       0
Bank Sta=1214.57,2119.25
XS Rating Curve= 0 ,0
Exp/Cntr(USF)=0.3,0.1
Exp/Cntr=0.5,0.3

Type RM Length L Ch R = 1 ,33192.89,1234.76,1006.17,727.63
XS GIS Cut Line= 2
362601.8736214855903179.97413019363568.7352490045901609.53455864
#Sta/Elev= 30
 1044.55   54.33 1054.55   49.98 1102.38   14.74 1114.71   10.63 1121.57     4.9
 1298.54     2.8 1308.13   -3.03 1338.96   -3.45 1575.04    -.43 1683.15   -3.37
 1802.73    1.79 1812.54     4.5 1863.37     4.5 1875.41       1 1902.07    5.25
 1939.17    4.42 1969.15    8.77  2079.1    6.74 2121.95      .7 2201.93     .05
 2256.35    5.28 2363.98    6.04 2498.92   12.97 2513.92   16.41 2623.87   23.71
 2668.85   31.86 2708.83   32.31 2738.82   37.53 2833.78   43.64 2888.75   54.37
#Mann= 3 , 0 , 0
 1044.55    .055       0 1114.71   .0325       0 2256.35    .055       0
Bank Sta=1114.71,2256.35
XS Rating Curve= 0 ,0
Exp/Cntr(USF)=0.3,0.1
Exp/Cntr=0.5,0.3

Type RM Length L Ch R = 1 ,32186.72,1219.67,994.54,671.77
XS GIS Cut Line= 2
363585.524373777 5903689.3092772364280.2721808325902025.70106655
#Sta/Elev= 30
  958.86   55.74  983.83   54.29 1013.79   40.28 1048.75   34.37 1078.71   21.85
 1097.93    4.21 1137.88   -3.04 1205.86    1.77 1367.96     .93 1394.13    1.34
 1396.22     4.5 1591.57     4.5 1600.56    1.73 1800.13    1.03 2035.51   -4.04
 2044.77   -3.94  2054.8      .4 2087.54    1.74 2197.18   -1.13 2236.26    5.52
 2297.26    7.58  2347.2   14.03 2437.09   17.25 2507.01   16.66 2546.96   20.13
 2591.91   20.58 2616.88   24.01 2671.81   26.51 2706.77    34.9  2761.7   41.94
#Mann= 3 , 0 , 0
  958.86    .055       0 1048.75   .0325       0 2236.26    .055       0
Bank Sta=1048.75,2236.26
XS Rating Curve= 0 ,0
Exp/Cntr(USF)=0.3,0.1
Exp/Cntr=0.5,0.3

Type RM Length L Ch R = 1 ,31192.18,1034.11,994.63,993.08
XS GIS Cut Line= 2
364649.3241861275904008.64111034364995.5919739045902453.27202352
#Sta/Elev= 30
  579.43   40.49  599.41   39.85   609.4   34.48  641.34    5.01   649.4    2.16
  674.61    1.03  725.89    1.38  735.88     4.2  955.84     4.2  964.84    1.59
 1104.56     .74 1199.53      -1 1209.85   -2.16  1259.6   -1.38 1285.02    2.15
 1288.82     4.2 1466.49     4.2 1475.03     .53 1495.17    -.32 1748.66      -3
 1779.35   -2.62  1818.1    2.85 1819.33    4.38 1823.45    5.51 1848.19    6.51
 1873.17   10.45 1953.09   13.55 1993.05   13.78 2052.99   19.26 2172.88   21.27
#Mann= 3 , 0 , 0
  579.43    .055       0  599.41   .0325       0 1823.45    .055       0
Bank Sta=599.41,1823.45
XS Rating Curve= 0 ,0
Exp/Cntr(USF)=0.3,0.1
Exp/Cntr=0.5,0.3

Type RM Length L Ch R = 1 ,30197.55,1025.02,1021.21,1018.34
XS GIS Cut Line= 2
365551.1467196745904527.67976934366021.5640176275902414.65468567
#Sta/Elev= 30
  774.91    63.5  814.91   58.03  829.91    50.2   834.9   43.49   859.9   29.68
   904.9   20.61  924.89   26.32  944.89   16.16 1074.88   11.34 1084.88   13.15
 1154.87    8.57 1162.47    3.34 1205.81    -.88 1278.44    2.11 1398.24    2.15
 1631.86   -1.39 2007.11     2.3 2409.88   -1.05 2441.47    -.22 2466.92    5.21
 2539.71    3.23  2604.7    8.79 2709.69    6.92 2729.69    3.91 2819.68   18.45
 2849.67   18.87 2894.67   31.57 2904.67   31.18 2924.66   42.31 2939.66   43.98
#Mann= 3 , 0 , 0
  774.91    .055       0 1154.87   .0325       0 2466.92    .055       0
Bank Sta=1154.87,2466.92
XS Rating Curve= 0 ,0
Exp/Cntr(USF)=0.3,0.1
Exp/Cntr=0.5,0.3

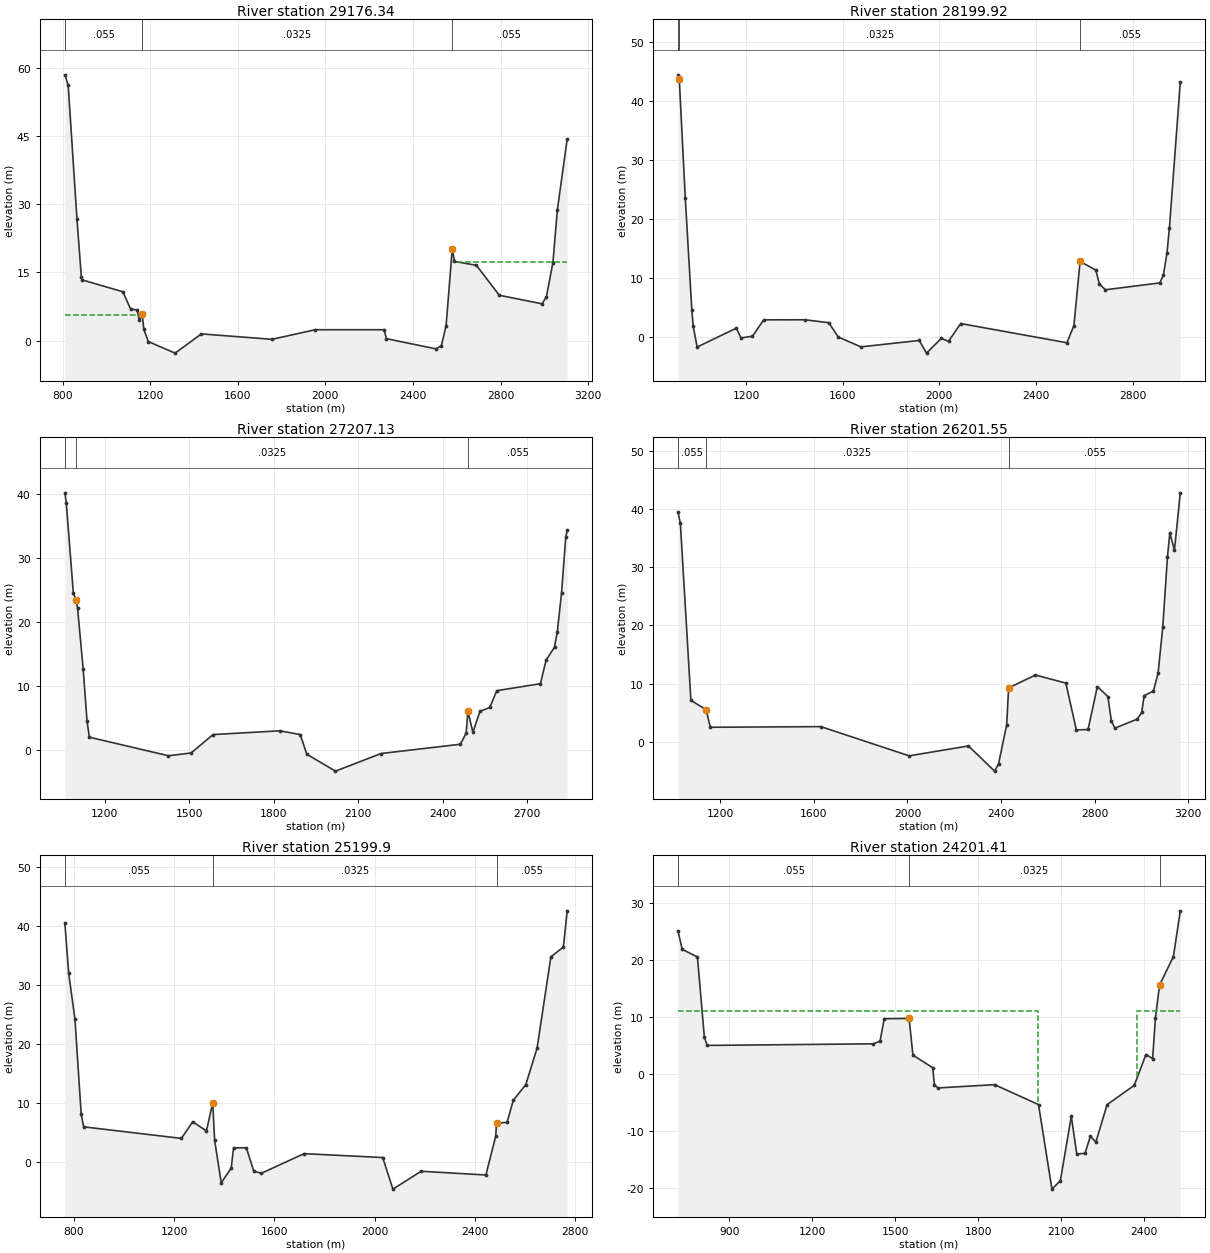
Type RM Length L Ch R = 1 ,29176.34,1138.34,976.42,790.73
XS GIS Cut Line= 2
366560.9276692795904678.03350944367059.5760711035902438.19974385
#Sta/Elev= 30
  809.88   58.48  824.88   56.17  864.87   26.84  884.87    14.1  889.87   13.34
 1074.84   10.75 1109.84    6.95 1139.83    6.74 1149.83    4.47 1162.71    5.88
 1170.58    2.46 1190.71     -.2 1313.32   -2.75 1433.44    1.48 1756.23     .29
 1953.58     2.4 2268.33     2.4 2278.55     .43 2506.13   -1.82 2529.83   -1.11
 2551.38    3.26 2579.62   20.19 2589.62   17.42 2689.61   16.58 2794.59    9.98
 2989.56     8.1 3009.56     9.6 3039.55   17.18 3059.55   28.68 3104.55   44.32
#Mann= 3 , 0 , 0
  809.88    .055       0 1162.71   .0325       0 2579.62    .055       0
#XS Ineff= 2 ,-1
  809.88 1146.63    5.57 2601.53 3104.55   17.35
Permanent Ineff=
       F       F
Bank Sta=1162.71,2579.62
XS Rating Curve= 0 ,0
Exp/Cntr(USF)=0.3,0.1
Exp/Cntr=0.5,0.3

Type RM Length L Ch R = 1 ,28199.92,995.41,992.79,993.66
XS GIS Cut Line= 2
367651.6502519545904722.52372833 367873.887254415902656.81752187
#Sta/Elev= 30
  918.94   44.49  923.94   43.81  948.91    23.6  975.96    4.58  981.63    1.86
  997.91   -1.69 1160.16    1.52 1179.25    -.14 1226.81     .15 1273.38    2.93
 1443.34    2.94 1542.65    2.44 1581.58     .02 1675.29   -1.66 1916.58    -.57
 1946.78   -2.72 2007.94    -.21 2037.83    -.72 2088.11     2.3 2527.66    -.96
 2556.52    1.96 2582.03   12.83 2646.95   11.37 2661.93    8.99  2686.9    8.03
 2911.64    9.19 2926.62   10.52  2941.6   14.34 2951.59   18.56 2996.54   43.29
#Mann= 3 , 0 , 0
  918.94    .055       0  923.94   .0325       0 2582.03    .055       0
#XS Ineff= 2 , 0
                         2636.98           11.56
Permanent Ineff=
       F       F
Bank Sta=923.94,2582.03
XS Rating Curve= 0 ,0
Exp/Cntr(USF)=0.3,0.1
Exp/Cntr=0.5,0.3

Type RM Length L Ch R = 1 ,27207.13,1086.67,1005.59,915.85
XS GIS Cut Line= 2
368653.9797961015904684.76221193368844.699946377  5902912.006482
#Sta/Elev= 30
  1058.8   40.17  1063.8   38.51 1088.77   24.51 1098.76   23.39 1103.75   22.16
  1123.8   12.59 1137.41    4.46 1145.74    1.99 1426.43    -.91 1506.89    -.47
  1584.6     2.4  1821.6    2.99 1894.43     2.4 1917.42    -.67 2019.36   -3.31
 2181.25    -.56 2462.69     .89  2483.4    2.64 2489.38    6.04 2507.16    2.76
 2532.14    6.02  2567.1    6.64 2592.07    9.26 2746.89   10.35 2766.87   14.02
 2796.84   16.06 2806.83   18.46 2821.81   24.51 2836.79   33.24 2841.79   34.31
#Mann= 3 , 0 , 0
  1058.8    .055       0 1098.76   .0325       0 2489.38    .055       0
Bank Sta=1098.76,2489.38
XS Rating Curve= 0 ,0
Exp/Cntr(USF)=0.3,0.1
Exp/Cntr=0.5,0.3

Type RM Length L Ch R = 1 ,26201.55,1068.28,1001.65,945.48
XS GIS Cut Line= 2
369691.8209327125904835.26165984369802.4220721925902690.43859519
#Sta/Elev= 30
 1018.89   39.42 1028.88   37.54 1073.83    7.11 1138.76    5.53 1156.73    2.49
 1629.49     2.6 2007.26   -2.42 2260.72    -.72 2372.44   -5.05 2389.44   -3.79
 2424.26    2.91 2432.36    9.26 2547.24   11.47  2677.1   10.08 2722.05    2.03
 2771.99    2.11 2811.95    9.48  2856.9    7.76 2871.89    3.53 2886.87    2.34
 2981.77    3.88 3001.75    5.03 3011.74    7.91 3051.69    8.73 3071.67   11.82
 3091.65   19.75 3111.63   31.78 3121.62   35.87  3141.6   32.98 3166.57   42.79
#Mann= 3 , 0 , 0
 1018.89    .055       0 1138.76   .0325       0 2432.36    .055       0
#XS Ineff= 2 , 0
                         2456.32            9.52
Permanent Ineff=
       F       F
Bank Sta=1138.76,2432.36
XS Rating Curve= 0 ,0
Exp/Cntr(USF)=0.3,0.1
Exp/Cntr=0.5,0.3

Type RM Length L Ch R = 1 ,25199.9 ,1065.31,998.49,975.09
XS GIS Cut Line= 2
370718.3077095245905191.75483746370741.7553093775903188.30404968
#Sta/Elev= 30
  764.45   40.49  779.44   32.04  804.43   24.29  829.41    8.13   839.4    5.96
 1229.12       4 1274.09    6.82 1329.05    5.26 1354.04   10.06 1361.74    3.67
 1388.08   -3.53 1427.87   -1.04 1437.24     2.4 1488.35     2.4 1517.74   -1.56
  1548.3   -1.92 1718.39    1.41 2032.18     .75 2072.87   -4.61 2185.69   -1.58
 2443.79   -2.21 2482.95    4.36 2486.28    6.59  2528.2    6.71 2553.18   10.47
 2603.14   13.14 2648.11   19.33 2703.07   34.81 2753.03   36.48 2768.02   42.62
#Mann= 3 , 0 , 0
  764.45    .055       0 1354.04   .0325       0 2486.28    .055       0
Bank Sta=1354.04,2486.28
XS Rating Curve= 0 ,0
Exp/Cntr(USF)=0.3,0.1
Exp/Cntr=0.5,0.3

Type RM Length L Ch R = 1 ,24201.41,139.37,137.37,138.3
XS GIS Cut Line= 2
371756.7121453255905380.33097292371720.4204786075903565.74943093
#Sta/Elev= 30
  714.98   25.08  729.98   21.87  784.98   20.55  809.97    6.52  819.97       5
 1419.95    5.28 1444.95    5.74 1459.95    9.69 1549.95    9.74 1563.74    3.29
 1635.23    1.09 1641.31   -1.91 1653.94   -2.47  1858.7   -1.89 2017.59   -5.39
 2066.03  -20.24 2096.55  -18.76 2136.02   -7.43 2155.63  -14.06 2185.55  -13.96
 2204.82  -10.97 2224.98  -11.95 2265.34    -5.4 2363.69   -2.01 2405.55    3.39
 2429.92     2.7 2439.92    9.75 2454.92    15.6 2504.92    20.6 2529.92   28.64
#Mann= 3 , 0 , 0
  714.98    .055       0 1549.95   .0325       0 2454.92    .055       0
#XS Ineff= 2 , 0
            2015      11    2375              11
Permanent Ineff=
       F       F
Bank Sta=1549.95,2454.92
XS Rating Curve= 0 ,0
Exp/Cntr(USF)=0.3,0.1
Exp/Cntr=0.5,0.3