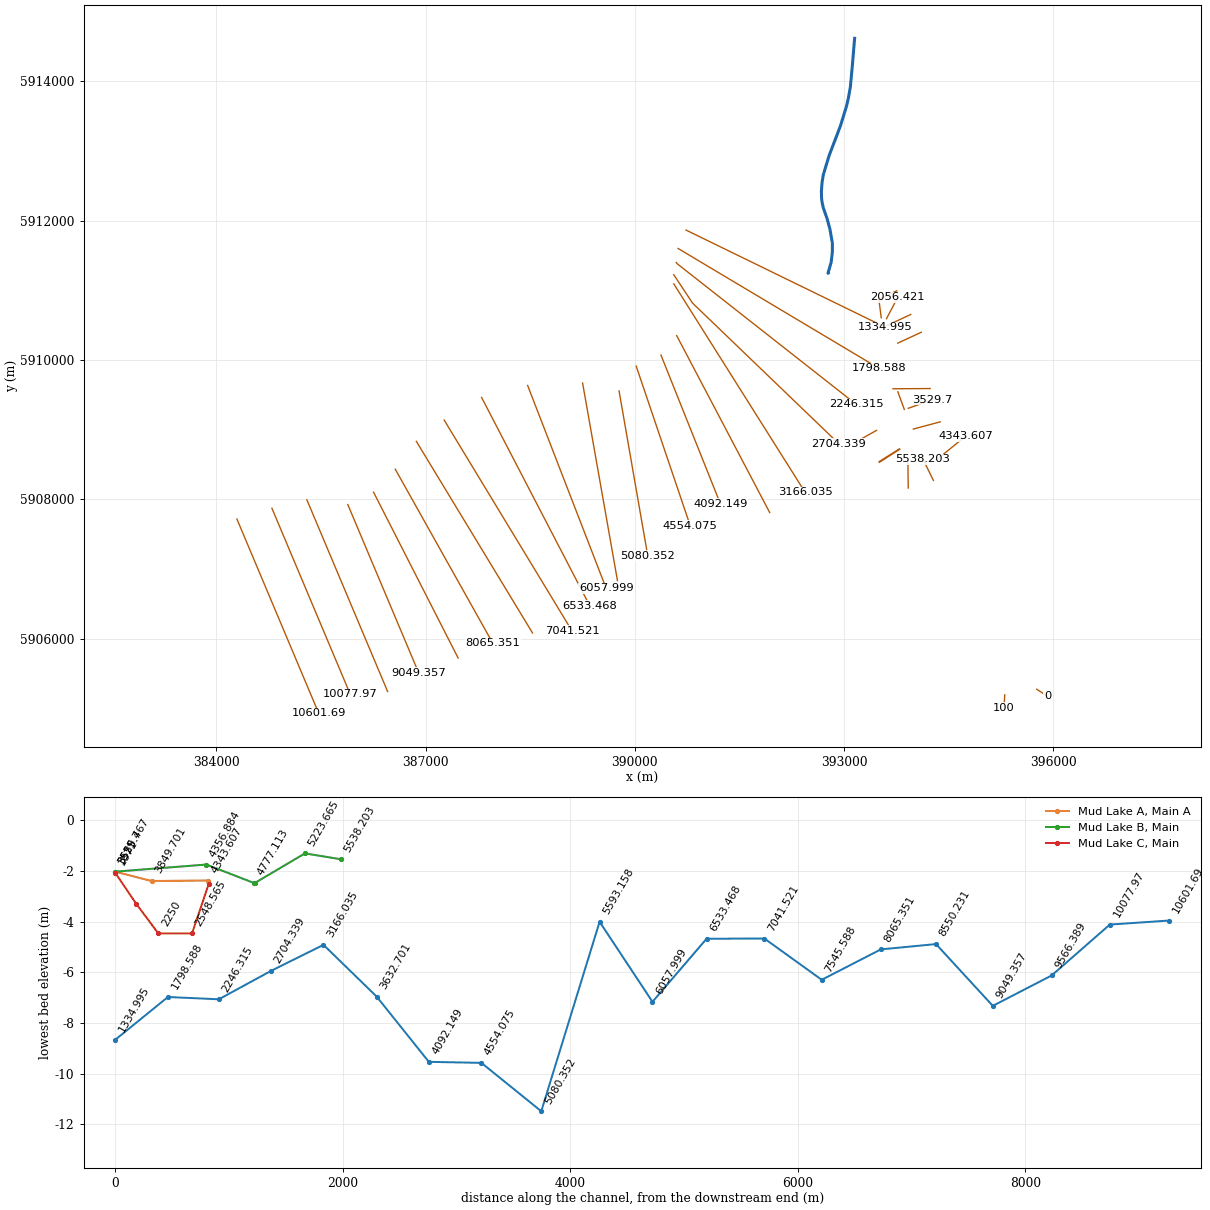
HEC-RAS study Churchill_Mapping.prj: Churchill River Flood Risk Mapping

--- Churchill_Mapping.g19 (geometry) --- (continued)

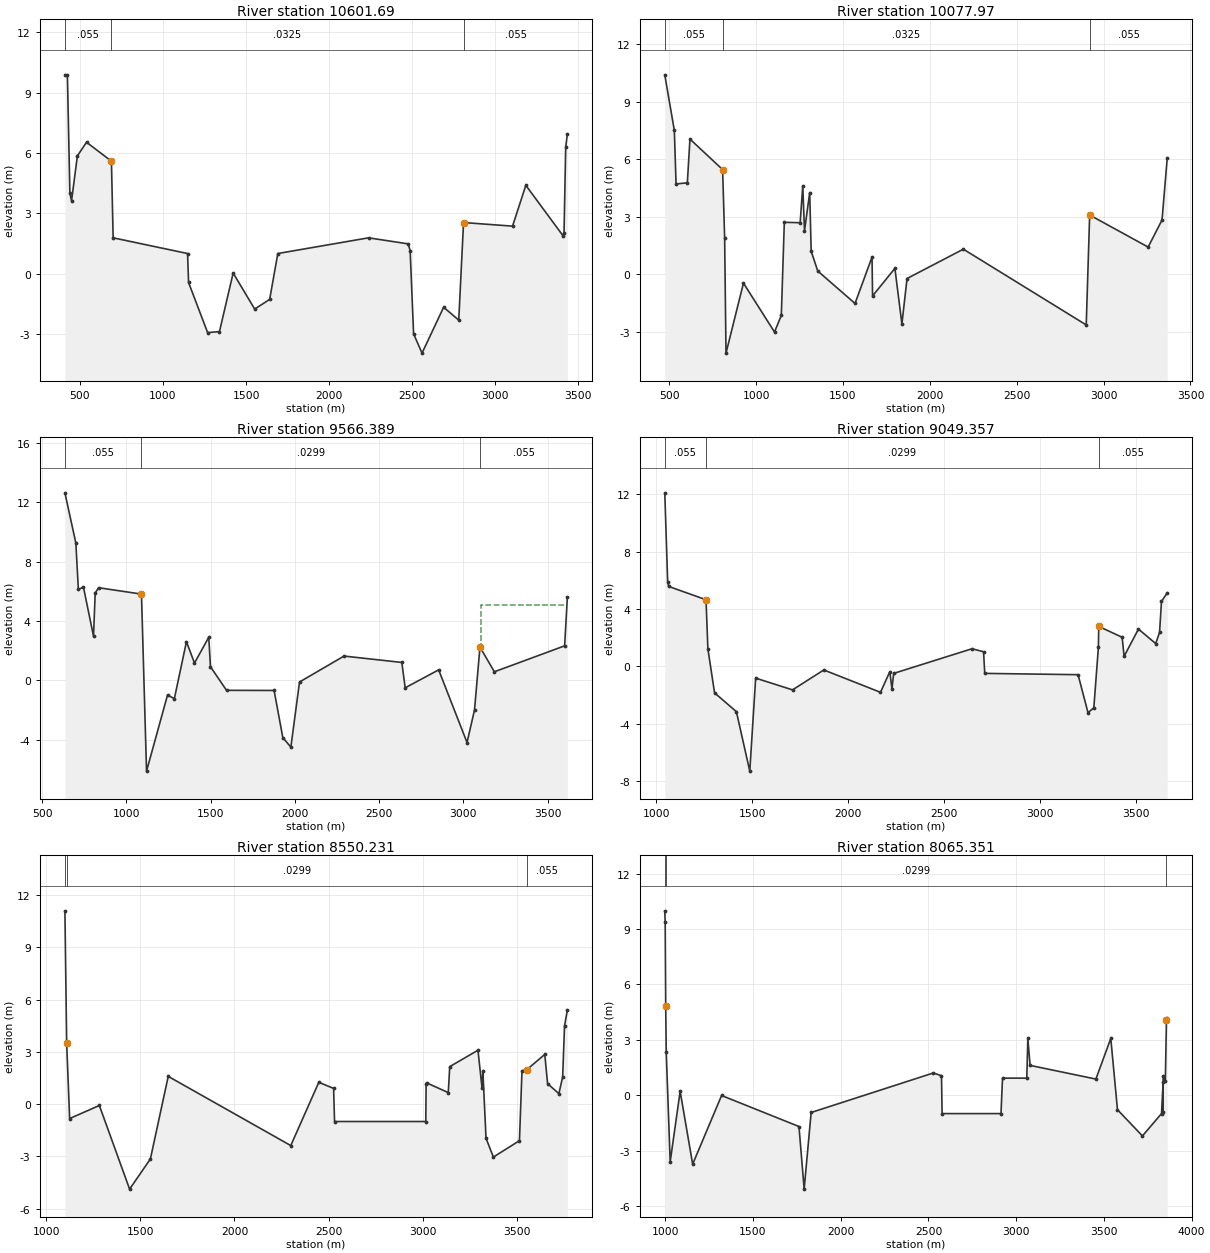
Type RM Length L Ch R = 1 ,10601.69,526.02,523.72,530.89
XS GIS Cut Line= 2
384293.2460566355907719.28759255385467.0402656825904932.46954074
#Sta/Elev= 30
  409.86    9.88  424.85    9.85  439.84    3.99  449.84    3.62  484.83    5.85
  539.81    6.53  689.76    5.59  700.17    1.78 1148.02       1 1154.09    -.44
  1268.7   -2.93    1340   -2.88 1422.37     .03 1552.05   -1.76 1642.12   -1.28
 1691.26       1 2237.27    1.78 2475.53    1.48 2487.58    1.15  2508.4   -2.99
 2559.13   -3.95  2689.2   -1.67 2780.12   -2.31 2809.01    2.54 3103.91    2.36
 3183.88    4.39  3408.8    1.87  3413.8    2.04  3423.8    6.28  3433.8    6.94
#Mann= 3 , 0 , 0
  409.86    .055       0  689.76   .0325       0 2809.01    .055       0
Bank Sta=689.76,2809.01
XS Rating Curve= 0 ,0
Exp/Cntr(USF)=0.5,0.3
Exp/Cntr=0.5,0.3

Type RM Length L Ch R = 1 ,10077.97,521.17,511.58,513.31
XS GIS Cut Line= 2
384795.2810404965907873.63267348 385917.752832965905208.66400365
#Sta/Elev= 30
  474.46    10.4   529.4     7.5  539.39    4.71  604.31    4.77   619.3    7.05
  807.31    5.46  818.93     1.9  826.78   -4.11  927.22    -.46 1105.96   -3.01
 1145.18   -2.14 1162.38    2.71 1253.58    2.69 1268.56    4.61 1278.55    2.27
 1308.51    4.26 1317.02     1.2 1354.91     .17 1569.39   -1.52 1667.29      .9
 1670.29   -1.13 1798.86     .31 1839.09   -2.59 1868.77    -.22 2192.76    1.31
 2900.01   -2.64 2919.77    3.09 3256.31    1.42 3336.22    2.83 3366.18    6.06
#Mann= 3 , 0 , 0
  474.46    .055       0  807.31   .0325       0 2919.77    .055       0
Bank Sta=807.31,2919.77
XS Rating Curve= 0 ,0
Exp/Cntr(USF)=0.5,0.3
Exp/Cntr=0.5,0.3

Type RM Length L Ch R = 1 ,9566.389,526.44,517.03,518.5
XS GIS Cut Line= 2
 385296.612877025907995.23420049386454.6404151235905245.84921144
#Sta/Elev= 30
  634.42   12.65  699.36    9.26  714.35    6.13  744.32     6.3  804.26    2.98
  814.25    5.89  834.24    6.25    1089    5.82 1119.08   -6.12 1243.67    -.99
 1284.32   -1.23 1356.07    2.61 1403.71    1.17 1488.64    2.91 1498.63     .92
 1594.13    -.67 1876.51    -.68 1928.28   -3.86 1976.05    -4.5 2027.41    -.11
 2291.75    1.64 2634.89    1.21 2654.81     -.5  2853.6     .71 3022.05   -4.19
 3066.55   -1.99 3098.76    2.25  3184.3     .58 3601.54    2.33 3617.74    5.61
#Mann= 3 , 0 , 0
  634.42    .055       0    1089   .0299       0 3098.76    .055       0
#XS Ineff= 2 , 0
                         3104.65            5.08
Permanent Ineff=
       F       F
Bank Sta=1089,3098.76
XS Rating Curve= 0 ,0
Exp/Cntr(USF)=0.5,0.3
Exp/Cntr=0.5,0.3

Type RM Length L Ch R = 1 ,9049.357,354.9,499.13,661.51
XS GIS Cut Line= 2
385883.6950816455907926.49353693386899.7105420385905514.27323009
#Sta/Elev= 30
 1043.99    12.1 1058.97    5.91 1063.97    5.57 1258.78    4.64 1268.55    1.21
 1303.36   -1.86 1416.97   -3.17 1486.76   -7.32 1517.45    -.83 1709.48   -1.65
  1872.4    -.26 2167.67   -1.82 2216.36    -.38 2227.44   -1.59 2236.34     -.5
 2644.43    1.22 2704.67    1.01 2710.79     -.5 3196.95    -.59 3248.71   -3.24
 3279.04    -2.9  3302.9    1.33 3304.57    2.78 3426.67    2.02 3436.66     .69
 3511.59    2.59  3601.5    1.58 3621.48    2.36 3631.47    4.52 3661.44    5.12
#Mann= 3 , 0 , 0
 1043.99    .055       0 1258.78   .0299       0 3304.57    .055       0
Bank Sta=1258.78,3304.57
XS Rating Curve= 0 ,0
Exp/Cntr(USF)=0.5,0.3
Exp/Cntr=0.5,0.3

Type RM Length L Ch R = 1 ,8550.231,401.22,484.88,570.88
XS GIS Cut Line= 2
386252.8336119025908104.28574356387465.3059809445905726.79048895
#Sta/Elev= 30
  1099.5   11.09 1108.77     3.5 1124.65    -.83 1282.46    -.08 1443.08   -4.88
 1553.51   -3.15 1648.26    1.59 2299.18   -2.38 2448.08    1.25 2526.77      .9
 2531.65      -1 3016.34      -1 3018.12    1.14 3020.37    1.22 3135.74     .66
 3143.58    2.15 3293.51    3.09 3315.13     .92 3319.51     1.9 3336.26   -1.96
 3375.21   -3.04 3513.83    -2.1  3527.3    1.91 3553.39    1.98 3648.35    2.85
 3663.35    1.17 3723.32      .6 3743.31    1.56 3753.31    4.49  3768.3    5.39
#Mann= 3 , 0 , 0
  1099.5    .055       0 1108.77   .0299       0 3553.39    .055       0
Bank Sta=1108.77,3553.39
XS Rating Curve= 0 ,0
Exp/Cntr(USF)=0.5,0.3
Exp/Cntr=0.5,0.3

Type RM Length L Ch R = 1 ,8065.351,440.96,519.76,595.84
XS GIS Cut Line= 2
386564.0103795195908433.80417394387964.1980761895905936.22034573
#Sta/Elev= 30
  997.45    9.98  999.76    9.35 1002.73    4.85 1005.73    2.32 1028.28   -3.61
 1084.99     .21 1156.31   -3.74 1321.15    -.02 1762.15    -1.7 1791.68   -5.09
 1831.54    -.94 2528.16     1.2 2574.33    1.05 2577.82      -1 2913.43      -1
 2922.13     .92 3060.44     .92 3066.35    3.08 3079.25    1.61 3454.16     .87
 3539.14    3.07 3577.24    -.79 3719.38   -2.21 3828.24      -1 3837.38     .71
 3837.43    -.92 3837.63    1.05 3849.92     .74 3856.35    4.07 3860.76    4.16
#Mann= 3 , 0 , 0
  997.45    .055       0 1002.73   .0299       0 3856.35    .055       0
Bank Sta=1002.73,3856.35
XS Rating Curve= 0 ,0
Exp/Cntr(USF)=0.5,0.3
Exp/Cntr=0.5,0.3

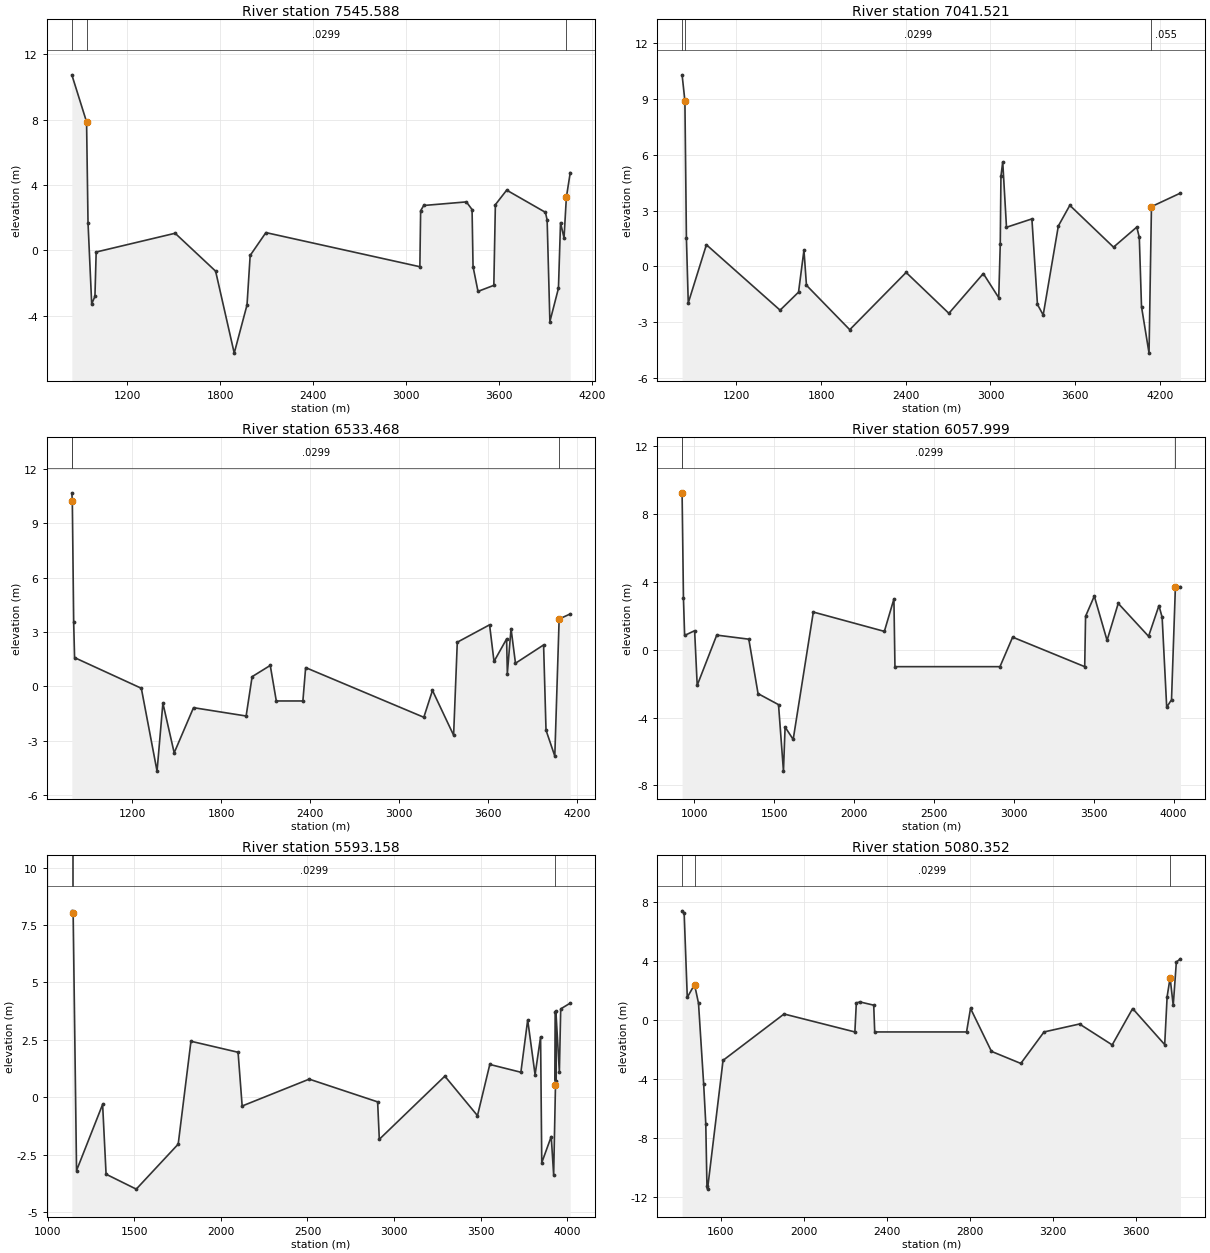
Type RM Length L Ch R = 1 ,7545.588,500.9,504.07,503.17
XS GIS Cut Line= 2
386866.6511305035908832.91344225388532.2559101445906085.77140968
#Sta/Elev= 30
  844.38   10.75  939.31    7.87  948.71    1.69  972.39   -3.28  993.36   -2.81
 1001.24     -.1 1510.21    1.05 1771.09   -1.27 1891.15   -6.29 1973.58   -3.34
 1993.86    -.31 2095.24    1.09 3087.73      -1 3092.73    2.43 3112.71    2.75
 3387.51    2.97 3424.23     2.5 3430.48    -.99 3462.45   -2.51 3564.48   -2.14
 3574.46     2.8 3647.32    3.69 3897.14    2.33 3908.05    1.86 3925.84   -4.36
 3980.98   -2.32 3994.44     1.7 4017.05     .76 4032.04    3.25 4057.02    4.76
#Mann= 3 , 0 , 0
  844.38    .055       0  939.31   .0299       0 4032.04    .055       0
Bank Sta=939.31,4032.04
XS Rating Curve= 0 ,0
Exp/Cntr(USF)=0.5,0.3
Exp/Cntr=0.5,0.3

Type RM Length L Ch R = 1 ,7041.521,669.66,508.05,362.61
XS GIS Cut Line= 2
387265.559942192 5909138.2833785389096.9538313865906117.69941799
#Sta/Elev= 30
  814.41   10.31  834.39    8.91  845.04    1.53  858.12   -1.96  986.71    1.17
 1508.96   -2.35  1639.7   -1.38 1678.14     .88 1695.87   -1.01 2002.68    -3.4
 2402.29    -.32 2705.27   -2.52 2949.29    -.38 3058.58   -1.68 3069.44    1.21
  3074.3    4.85  3086.9    5.63 3113.59    2.11 3293.65    2.56 3333.07   -2.04
 3373.68   -2.61 3481.07    2.18  3562.4    3.29 3872.18    1.04 4037.06    2.12
 4054.85    1.57 4070.49   -2.16  4123.9   -4.66    4141    3.22 4346.84    3.95
#Mann= 3 , 0 , 0
  814.41    .055       0  834.39   .0299       0    4141    .055       0
Bank Sta=834.39,4141
XS Rating Curve= 0 ,0
Exp/Cntr(USF)=0.5,0.3
Exp/Cntr=0.5,0.3

Type RM Length L Ch R = 1 ,6533.468,735.32,475.47,238.27
XS GIS Cut Line= 2
387802.332174415 5909462.6890631389352.7527952525906476.72862697
#Sta/Elev= 30
  791.92   10.68  795.15   10.24  804.32    3.55  810.44    1.59 1261.04     -.1
 1367.12   -4.67 1406.59    -.92 1482.83   -3.66 1613.31   -1.17 1968.46   -1.63
  2008.9     .54 2131.35    1.16  2172.2     -.8 2351.64     -.8 2370.26    1.04
 3167.99    -1.7 3226.33    -.22 3369.07   -2.69  3393.9    2.44 3611.86     3.4
 3641.83    1.38 3726.76    2.62 3731.76     .71 3756.73    3.19 3786.71    1.28
 3976.54    2.29 3992.85   -2.41 4052.16   -3.84 4081.45    3.72 4156.39       4
#Mann= 3 , 0 , 0
  791.92    .055       0  795.15   .0299       0 4081.45    .055       0
Bank Sta=795.15,4081.45
XS Rating Curve= 0 ,0
Exp/Cntr(USF)=0.5,0.3
Exp/Cntr=0.5,0.3

Type RM Length L Ch R = 1 ,6057.999,902.53,464.84,160.09
XS GIS Cut Line= 2
388462.3290095775909635.13959393389588.5124833875906724.74443417
#Sta/Elev= 30
  922.51    9.25  931.05    3.04  938.39     .84 1000.96    1.12 1017.16    -2.1
 1139.42     .86 1340.29     .62 1398.07   -2.59 1526.29   -3.24 1557.22   -7.16
  1567.4   -4.56 1618.16   -5.29 1744.21    2.22 2189.01    1.08 2248.81    2.99
 2255.27      -1 2912.86      -1 2992.15     .74 3443.44      -1 3448.83    1.97
 3503.41    3.16 3583.38     .55 3653.34    2.73 3843.26     .79 3908.23     2.6
 3928.22    1.91 3956.81   -3.39 3986.95   -2.95 4011.13    3.67 4043.17    3.72
#Mann= 3 , 0 , 0
  922.51    .055       0  922.51   .0299       0 4011.13    .055       0
Bank Sta=922.51,4011.13
XS Rating Curve= 0 ,0
Exp/Cntr(USF)=0.5,0.3
Exp/Cntr=0.5,0.3

Type RM Length L Ch R = 1 ,5593.158,526.82,512.81,384.54
XS GIS Cut Line= 2
389250.3512986065909670.34968124389750.5710676985906837.16219239
#Sta/Elev= 30
 1139.86    8.12  1147.4    8.04 1167.07   -3.19 1317.54    -.31 1337.52   -3.35
 1511.71      -4 1753.84   -2.04 1827.49    2.44 2099.46    1.96 2123.04    -.38
 2510.07     .79    2905     -.2 2914.76   -1.83 3292.98     .92  3481.4     -.8
 3552.53    1.43 3731.94    1.09 3771.26    3.37 3813.94     .98 3845.64    2.63
 3852.48   -2.85 3907.15   -1.71 3921.11   -3.38 3931.72     .54 3931.72    3.73
 3931.82     .72 3933.94    3.76  3954.1     1.1 3961.88    3.85 4016.86     4.1
#Mann= 3 , 0 , 0
 1139.86    .055       0  1147.4   .0299       0 3931.72    .055       0
Bank Sta=1147.4,3931.72
XS Rating Curve= 0 ,0
Exp/Cntr(USF)=0.5,0.3
Exp/Cntr=0.5,0.3

Type RM Length L Ch R = 1 ,5080.352,171.62,526.28,896.9
XS GIS Cut Line= 2
389773.3241114275909556.74655967390184.7916802075907193.84023367
#Sta/Elev= 30
 1414.09    7.43 1424.08    7.26 1439.07    1.55 1474.05    2.42 1493.08    1.15
 1517.98   -4.36 1528.07   -7.04 1533.68  -11.25 1536.54  -11.48 1611.25   -2.73
 1904.73     .42  2245.6     -.8 2252.56    1.17 2269.78    1.24 2336.26    1.02
 2341.04     -.8    2783     -.8  2802.1      .8 2902.76   -2.12 3044.15   -2.94
 3155.87     -.8 3326.62    -.26 3483.85   -1.68 3582.21     .79 3736.51   -1.66
 3748.19     1.6 3762.56    2.88 3777.56       1 3792.55    3.95 3812.53    4.17
#Mann= 3 , 0 , 0
 1414.09    .055       0 1474.05   .0299       0 3762.56    .055       0
Bank Sta=1474.05,3762.56
XS Rating Curve= 0 ,0
Exp/Cntr(USF)=0.5,0.3
Exp/Cntr=0.5,0.3

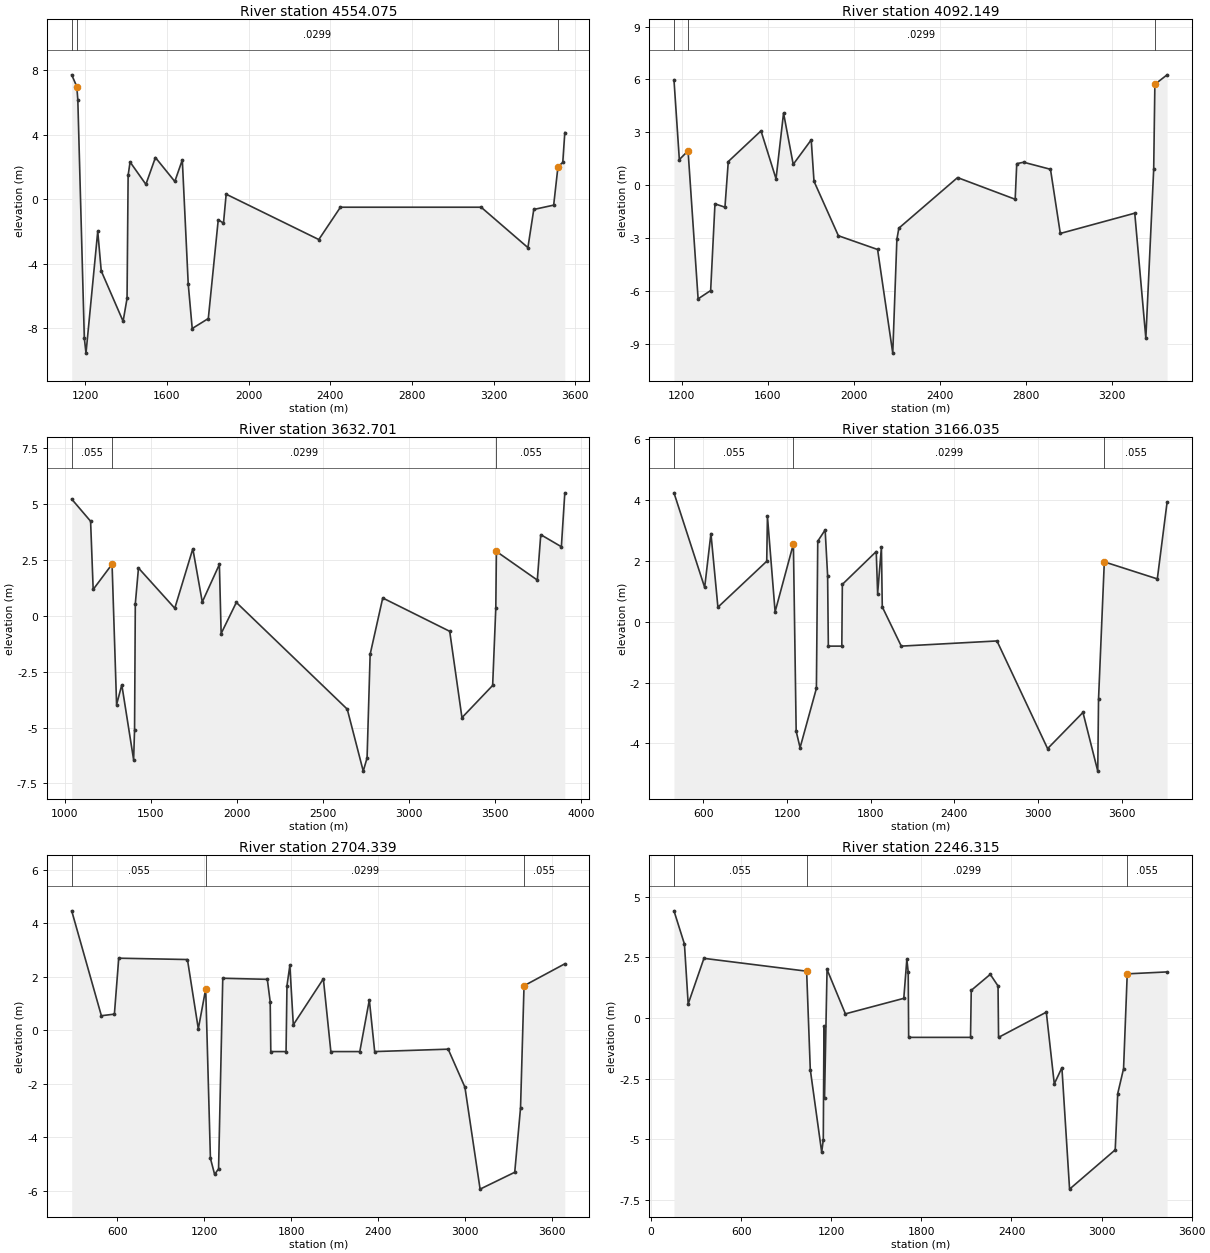
Type RM Length L Ch R = 1 ,4554.075,342.12,461.93,591.45
XS GIS Cut Line= 2
390019.2497682395909912.20180452390793.2241185295907625.73349269
#Sta/Elev= 30
 1134.49    7.73 1159.47       7 1164.47    6.17  1196.3   -8.64 1204.46   -9.57
    1262      -2 1279.09   -4.46 1386.11   -7.59 1405.44   -6.17 1410.73    1.48
 1420.27    2.31 1497.75     .92  1544.3    2.59 1639.26     1.1 1675.95    2.44
 1704.87   -5.26 1724.43   -8.04 1803.21   -7.42 1851.89   -1.28 1877.56   -1.49
 1890.64     .31 2344.17   -2.51    2450     -.5 3138.88     -.5 3367.75   -3.01
 3396.49    -.64 3493.88    -.37 3515.03    2.03  3538.4    2.28 3548.39    4.14
#Mann= 3 , 0 , 0
 1134.49    .055       0 1159.47   .0299       0 3515.03    .055       0
Bank Sta=1159.47,3515.03
XS Rating Curve= 0 ,0
Exp/Cntr(USF)=0.5,0.3
Exp/Cntr=0.5,0.3

Type RM Length L Ch R = 1 ,4092.149,230.75,459.45,666.47
XS GIS Cut Line= 2
390374.3913335285910070.69286523391225.2543586975907941.08811592
#Sta/Elev= 30
 1164.13    5.98 1189.11    1.45 1229.65    1.95 1276.37   -6.45 1334.73   -5.98
 1354.81   -1.06 1401.23   -1.25 1416.68    1.34 1568.82    3.08 1638.77     .36
 1673.75    4.09 1718.71    1.18 1802.43    2.57 1815.37     .22 1928.77   -2.87
 2111.08   -3.65 2181.66   -9.53 2200.76   -3.08 2209.94   -2.44    2483     .43
 2750.97     -.8 2758.24    1.22 2790.37     1.3 2915.17      .9 2960.81   -2.74
 3307.09   -1.59 3358.62   -8.68 3395.18     .91 3400.62    5.72 3457.41    6.26
#Mann= 3 , 0 , 0
 1164.13    .055       0 1229.65   .0299       0 3400.62    .055       0
Bank Sta=1229.65,3400.62
XS Rating Curve= 0 ,0
Exp/Cntr(USF)=0.5,0.3
Exp/Cntr=0.5,0.3

Type RM Length L Ch R = 1 ,3632.701,300.31,466.67,610.79
XS GIS Cut Line= 2
390599.5966915445910350.16917659391933.7067771495907812.47081517
#Sta/Elev= 30
 1038.91    5.21  1148.8    4.22 1163.78    1.17 1273.62     2.3 1299.91   -3.98
  1330.2   -3.09 1398.96   -6.44 1404.43   -5.09 1408.77     .53 1427.19    2.13
 1638.28     .33 1743.17    2.99 1798.12     .61 1897.54    2.29 1907.79     -.8
  1996.1     .59    2641   -4.18 2733.99   -6.95 2756.27   -6.36 2774.08   -1.73
 2847.29     .79 3236.67     -.7  3307.9   -4.56 3486.37   -3.12 3504.78     .36
 3508.17    2.87 3746.08    1.59 3766.05    3.62 3885.93    3.08 3905.91    5.49
#Mann= 3 , 0 , 0
 1038.91    .055       0 1273.62   .0299       0 3508.17    .055       0
Bank Sta=1273.62,3508.17
XS Rating Curve= 0 ,0
Exp/Cntr(USF)=0.5,0.3
Exp/Cntr=0.5,0.3

Type RM Length L Ch R = 1 ,3166.035,68.41,461.7,992
XS GIS Cut Line= 2
 390558.187221075911092.08614936392442.0912198995908101.93129383
#Sta/Elev= 30
  389.91    4.24  609.85    1.13  654.84     2.9  704.83     .48 1054.74    1.99
 1059.74    3.47 1114.73     .33 1245.82    2.56 1265.75    -3.6 1293.72   -4.14
 1410.68   -2.19 1420.43    2.65 1473.37    3.02 1491.07    1.52  1496.3     -.8
 1592.88     -.8 1596.63    1.23 1839.55    2.31 1849.55     .93 1876.68    2.46
 1882.83     .49 2019.01     -.8 2704.89    -.63 3067.76   -4.17 3321.18   -2.98
 3427.21   -4.91 3432.73   -2.55 3474.16    1.97 3854.07    1.41 3924.05    3.93
#Mann= 3 , 0 , 0
  389.91    .055       0 1245.82   .0299       0 3474.16    .055       0
Bank Sta=1245.82,3474.16
XS Rating Curve= 0 ,0
Exp/Cntr(USF)=0.5,0.3
Exp/Cntr=0.5,0.3

Type RM Length L Ch R = 1 ,2704.339,128.41,458.02,614.94
XS GIS Cut Line= 5
390557.5089563065911223.56462229      390827.651     5910815.629
     391054.1582    5910597.9076     392772.7882    5908945.9397
     392927.3156    5908797.4061
#Sta/Elev= 30
  284.58    4.46  489.28     .54  579.14      .6   609.1    2.69 1083.05    2.64
    1158     .05 1209.06    1.54 1241.56   -4.79 1270.54   -5.39 1297.72   -5.18
 1326.74    1.94 1634.07     1.9 1653.89    1.06    1658     -.8  1763.3     -.8
 1769.59    1.66 1789.49    2.42 1813.31      .2 2020.62    1.92 2072.28     -.8
    2272     -.8 2337.72    1.13 2374.67     -.8 2881.73    -.71 2997.17   -2.13
  3101.8   -5.94 3340.77   -5.31 3380.81    -2.9 3404.89    1.66 3686.21    2.48
#Mann= 3 , 0 , 0
  284.58    .055       0 1209.06   .0299       0 3404.89    .055       0
Bank Sta=1209.06,3404.89
XS Rating Curve= 0 ,0
Exp/Cntr(USF)=0.5,0.3
Exp/Cntr=0.5,0.3

Type RM Length L Ch R = 1 ,2246.315,201.07,447.73,605.77
XS GIS Cut Line= 5
390594.0541738285911398.76487304     390604.7077    5911382.2168
     391119.4203    5910977.8704     393002.1305    5909498.8561
       393171.52    5909365.7876
#Sta/Elev= 30
  152.49    4.42  222.14    3.05  247.12     .58  352.04    2.46 1035.91    1.93
 1060.28   -2.13  1136.3   -5.54 1146.87   -5.02 1151.37    -.35 1155.11   -3.31
 1171.88       2 1294.11     .17 1682.95     .81 1703.29    2.42 1712.37    1.89
 1715.38     -.8 2127.38     -.8 2132.15    1.14 2258.94     1.8 2310.52    1.32
 2314.03     -.8 2632.03     .24 2685.18   -2.72 2735.84   -2.05 2786.97   -7.06
 3090.88   -5.44  3107.6   -3.12 3146.49   -2.09 3170.91    1.82  3436.3     1.9
#Mann= 3 , 0 , 0
  152.49    .055       0 1035.91   .0299       0 3170.91    .055       0
Bank Sta=1035.91,3170.91
XS Rating Curve= 0 ,0
Exp/Cntr(USF)=0.5,0.3
Exp/Cntr=0.5,0.3

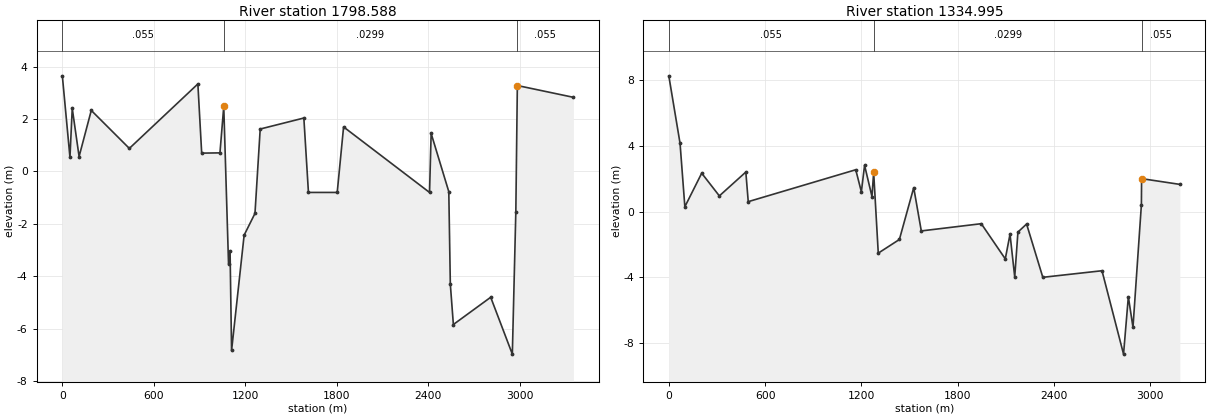
Type RM Length L Ch R = 1 ,1798.588,304.53,463.59,591.06
XS GIS Cut Line= 2
     390619.9044    5911599.3556     393499.5249     5909881.113
#Sta/Elev= 30
       0    3.65   49.96     .54   64.95    2.41  109.91     .57  189.85    2.33
  439.64     .88  889.28    3.34  914.26      .7 1034.16     .71 1059.14    2.48
 1090.51   -3.53 1100.51   -3.04 1110.43   -6.83 1192.81   -2.43 1263.96    -1.6
 1298.26    1.62 1584.67    2.04  1614.8     -.8 1803.58     -.8 1845.37     1.7
 2409.38     -.8 2419.93    1.45 2535.72    -.77 2545.77    -4.3 2565.72   -5.84
 2810.65    -4.8 2952.61   -6.97  2975.6   -1.53 2985.54    3.28 3353.29    2.83
#Mann= 3 , 0 , 0
       0    .055       0 1059.14   .0299       0 2985.54    .055       0
Bank Sta=1059.14,2985.54
XS Rating Curve= 0 ,0
Exp/Cntr(USF)=0.5,0.3
Exp/Cntr=0.5,0.3

Type RM Length L Ch R = 1 ,1334.995,253.1,460.22,569.19
XS GIS Cut Line= 2
     390733.8232    5911863.2676     393595.2788    5910467.9192
#Sta/Elev= 30
       0    8.26   69.97    4.16   99.96      .3  204.91    2.34  314.86     .96
  479.79    2.41  494.79     .61  1164.5    2.55 1199.48    1.21 1219.47    2.82
  1265.6     .92 1276.04     2.4 1304.79   -2.52 1436.39   -1.69 1525.65    1.46
 1572.79   -1.17 1946.52    -.73 2096.06   -2.87 2125.52   -1.37 2154.84   -3.97
 2174.77   -1.24 2228.71    -.75 2329.86   -3.99 2698.49   -3.59  2832.7   -8.66
 2862.63   -5.17 2891.47   -7.03 2943.95     .43 2945.11    2.01 3183.54    1.66
#Mann= 3 , 0 , 0
       0    .055       0 1276.04   .0299       0 2945.11    .055       0
Bank Sta=1276.04,2945.11
XS Rating Curve= 0 ,0
Exp/Cntr(USF)=0.5,0.3
Exp/Cntr=0.5,0.3

River Reach=Mud Lake A      ,Main A

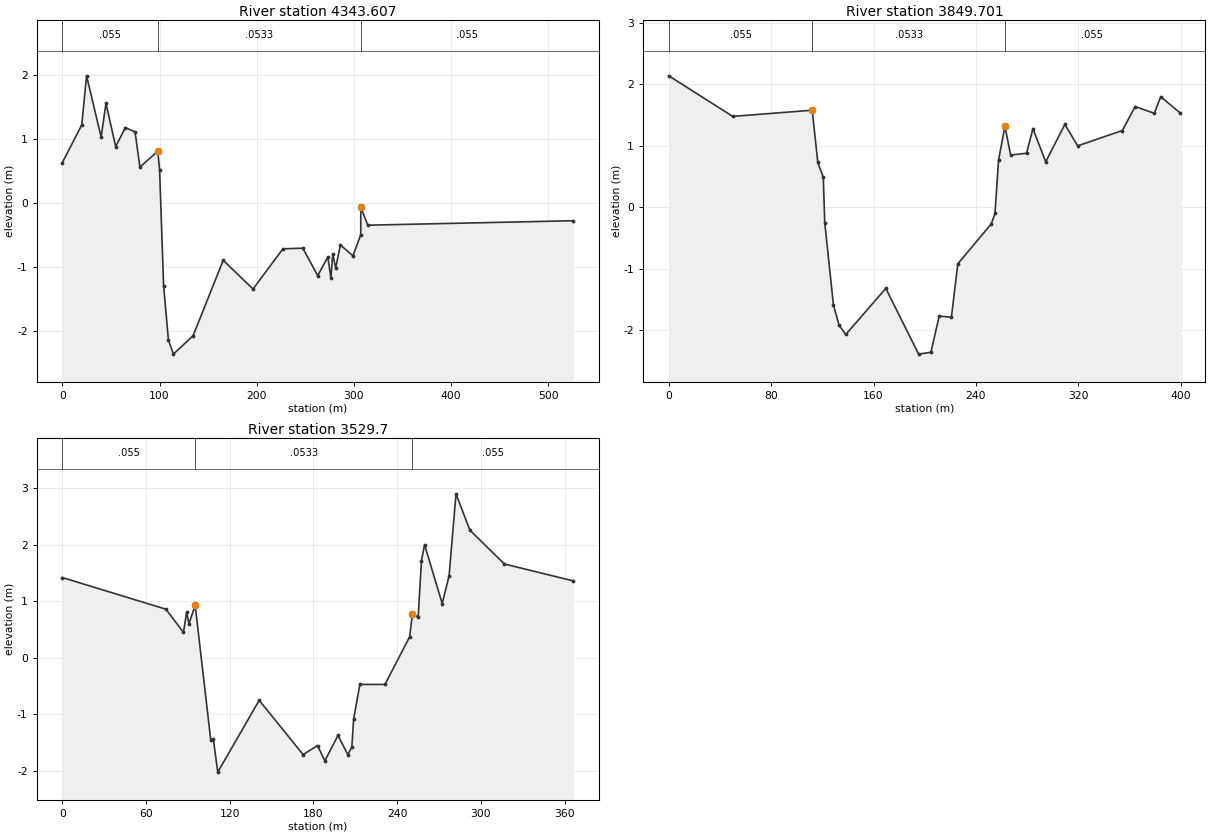
Type RM Length L Ch R = 1 ,4343.607,604.59,493.91,447.83
XS GIS Cut Line= 2
     394337.0618    5908577.9606     394745.8439    5908908.6904
#Sta/Elev= 30
       0     .63   19.95    1.22   24.94    1.99   39.91    1.03    44.9    1.56
   54.88     .88   64.85    1.18   74.83    1.11   79.82     .56   98.19     .81
  100.05     .52  104.19    -1.3  109.16   -2.15  114.27   -2.37  134.59   -2.08
  165.51     -.9  196.18   -1.35  226.94    -.72  247.42    -.71  262.73   -1.14
  273.14    -.85  276.36   -1.18  278.19     -.8  281.24   -1.02   286.1    -.66
  299.02    -.83     307     -.5  307.07    -.07  314.29    -.35  525.82    -.28
#Mann= 3 , 0 , 0
       0    .055       0   98.19   .0533       0  307.07    .055       0
Bank Sta=98.19,307.07
XS Rating Curve= 0 ,0
Exp/Cntr=0.3,0.1

Type RM Length L Ch R = 1 ,3849.701,313.52,320,334.19
XS GIS Cut Line= 2
     393993.4467    5909009.8673       394379.21     5909113.055
#Sta/Elev= 30
       0    2.14   49.92    1.48  112.07    1.58  116.41     .73   120.7     .49
  121.84    -.25  128.64   -1.59  133.03   -1.92   138.3   -2.07  169.56   -1.32
  195.19   -2.39   204.8   -2.36   211.3   -1.77  220.82   -1.79  225.81    -.92
     252    -.27  254.86     -.1  257.67     .77  262.64    1.32   267.1     .85
  279.53     .88  284.52    1.28   294.5     .74  309.48    1.35  319.46       1
   354.4    1.25  364.38    1.64  379.36    1.53  384.35     1.8  399.33    1.54
#Mann= 3 , 0 , 0
       0    .055       0  112.07   .0533       0  262.64    .055       0
Bank Sta=112.07,262.64
XS Rating Curve= 0 ,0
Exp/Cntr=0.3,0.1

Type RM Length L Ch R = 1 ,3529.7  ,263.47,232.95,176.47
XS GIS Cut Line= 2
     393920.4216    5909307.5241     394265.7035    5909429.7619
#Sta/Elev= 30
       0    1.42   74.25     .86   86.81     .45    89.1     .81   90.72      .6
   95.21     .93  106.35   -1.45  108.19   -1.43   111.4   -2.02  141.09    -.75
  172.56   -1.71  182.91   -1.55  188.15   -1.82  197.57   -1.37  204.58   -1.71
  207.46   -1.58  208.79   -1.08  213.23    -.47  231.22    -.47  248.87     .37
  250.94     .78  255.02     .72  257.39    1.72  259.62       2  272.24     .96
  277.19    1.45  282.14     2.9  292.03    2.26  316.78    1.66  366.28    1.36
#Mann= 3 , 0 , 0
       0    .055       0   95.21   .0533       0  250.94    .055       0
Bank Sta=95.21,250.94
XS Rating Curve= 0 ,0
Exp/Cntr=0.3,0.1

River Reach=Mud Lake B      ,Main

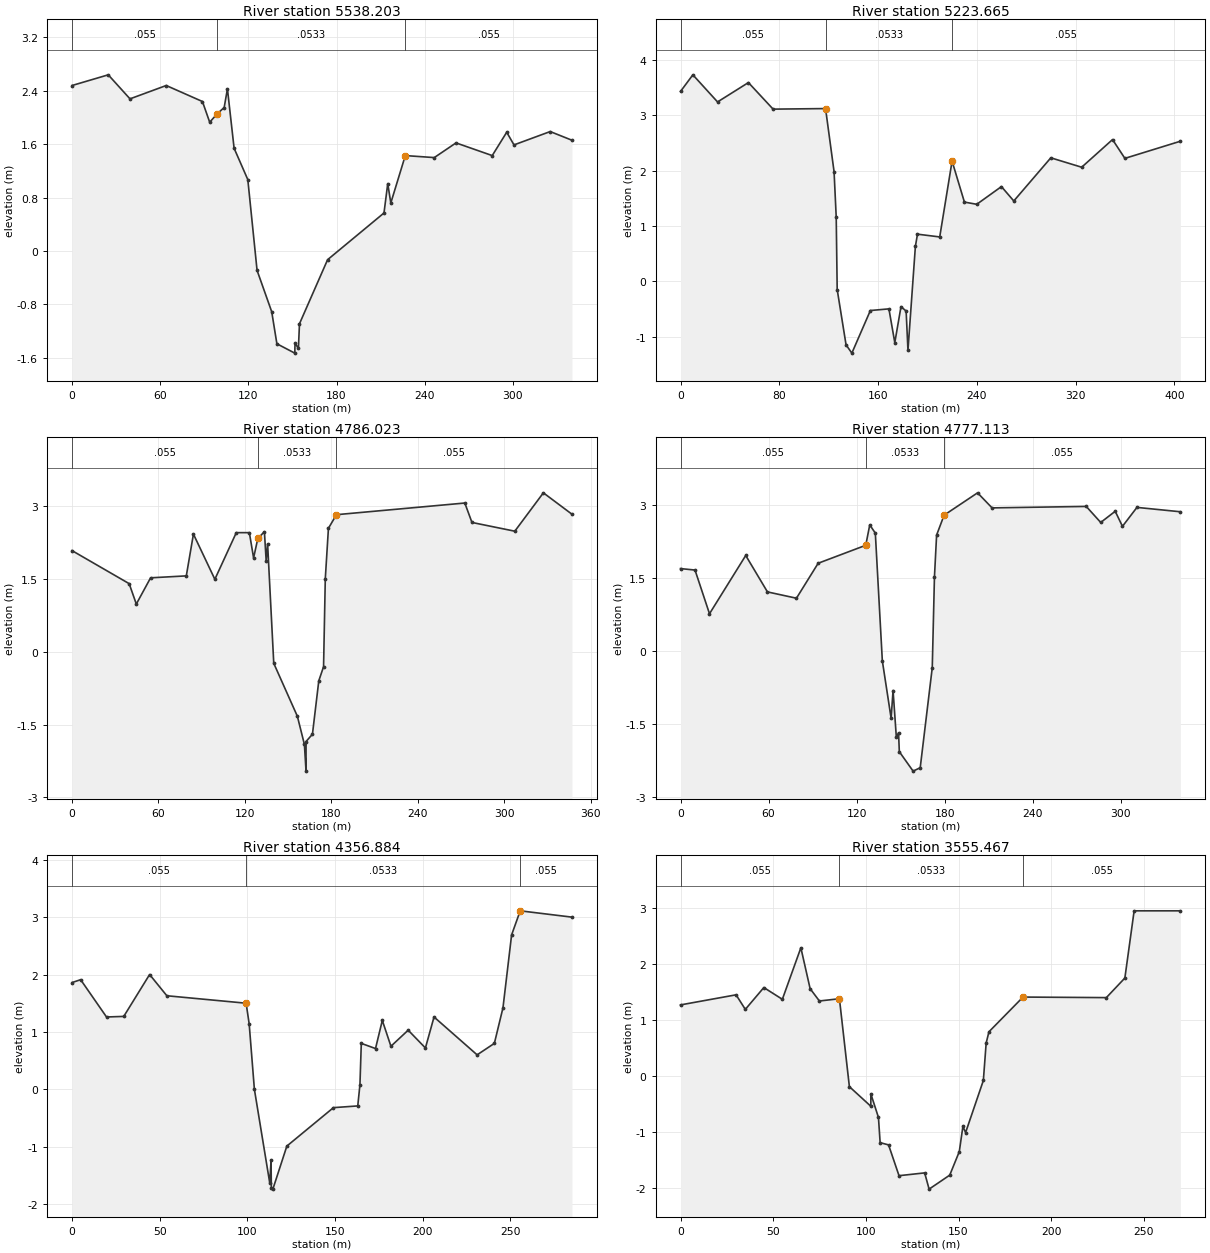
Type RM Length L Ch R = 1 ,5538.203,369.68,314.54,237.82
XS GIS Cut Line= 2
     394281.4992    5908272.3662     394132.0093    5908577.9606
#Sta/Elev= 30
       0    2.48   24.65    2.64   39.44    2.28    64.1    2.48   88.75    2.24
   93.68    1.93   98.97    2.06  103.54    2.15  105.75    2.43  110.29    1.54
  119.62    1.07  125.92    -.29  135.89    -.91  139.41   -1.39  151.59   -1.53
  151.76   -1.38  154.05   -1.46  154.79   -1.09  173.92    -.13   212.3     .57
  214.85    1.01  216.94     .72   226.8    1.43  246.52     1.4  261.31    1.62
  285.96    1.43  295.82    1.78  300.76    1.59  325.41    1.79   340.2    1.66
#Mann= 3 , 0 , 0
       0    .055       0   98.97   .0533       0   226.8    .055       0
Bank Sta=98.97,226.8
XS Rating Curve= 0 ,0
Exp/Cntr=0.3,0.1

Type RM Length L Ch R = 1 ,5223.665,548.39,437.64,252.47
XS GIS Cut Line= 2
     393920.3422    5908163.8868     393915.0506    5908568.7001
#Sta/Elev= 30
       0    3.43      10    3.73   29.99    3.24   54.98    3.59   74.97    3.11
  117.46    3.12  124.35    1.98  126.09    1.16  126.88    -.15  134.06   -1.15
  138.76    -1.3  153.75    -.53  168.77     -.5  173.53   -1.11  178.56    -.46
  182.71    -.54   184.2   -1.25  190.21     .63  191.91     .85  209.92      .8
  219.92    2.17  229.91    1.43  239.91    1.39   259.9    1.71   269.9    1.45
  299.89    2.23  324.88    2.06  349.87    2.56  359.87    2.22  404.85    2.53
#Mann= 3 , 0 , 0
       0    .055       0  117.46   .0533       0  219.92    .055       0
Bank Sta=117.46,219.92
XS Rating Curve= 0 ,0
Exp/Cntr=0.3,0.1

Type RM Length L Ch R = 1 ,4786.023,9.95,8.91,8.18
XS GIS Cut Line= 2
     393506.7977    5908532.9813     393798.8982    5908720.3067
#Sta/Elev= 30
       0    2.08   39.66     1.4   44.62     .98   54.53    1.52   79.32    1.56
   84.27    2.42   99.14    1.49  114.02    2.45  123.09    2.45  126.03    1.93
  128.97    2.33  133.54    2.47  134.76    1.87  135.76    2.22  140.03    -.24
  156.41   -1.33   161.3   -1.91  162.43   -2.46  162.45   -1.85  166.88    -1.7
  171.29     -.6   174.6    -.31   175.8     1.5  177.98    2.54  183.54    2.82
  272.65    3.06  277.61    2.66  307.35    2.48  327.18    3.27  347.01    2.83
#Mann= 3 , 0 , 0
       0    .055       0  128.97   .0533       0  183.54    .055       0
Bank Sta=128.97,183.54
XS Rating Curve= 0 ,0
Exp/Cntr=0.3,0.1

Type RM Length L Ch R = 1 ,4777.113,421.87,420.23,413.55
XS GIS Cut Line= 2
     393503.4815    5908542.9649     393791.8779    5908724.4695
#Sta/Elev= 30
       0     1.7    9.88    1.67   19.75     .77   44.45    1.97   59.26    1.22
   79.02    1.09   93.83    1.81  126.27    2.18  128.99     2.6  132.79    2.43
  137.57     -.2  143.55   -1.38  144.88    -.81  147.11   -1.77  148.62   -1.68
  149.15   -2.07  158.55   -2.47  163.39    -2.4   171.6    -.34   173.1    1.53
  174.56    2.39  179.68     2.8  202.48    3.26  212.36    2.95  276.56    2.98
  286.43    2.65  296.31    2.88  301.25    2.57  311.13    2.96  340.76    2.87
#Mann= 3 , 0 , 0
       0    .055       0  126.27   .0533       0  179.68    .055       0
Bank Sta=126.27,179.68
XS Rating Curve= 0 ,0
Exp/Cntr=0.3,0.1

Type RM Length L Ch R = 1 ,4356.884,981.54,801.42,578.46
XS GIS Cut Line= 2
     393217.1577    5908851.1169     393465.6019    5908990.8172
#Sta/Elev= 30
       0    1.86    4.91    1.91   19.66    1.26   29.49    1.27   44.23       2
   54.06    1.63   99.26     1.5     101    1.14  103.97       0  112.72   -1.63
  113.47   -1.24  113.65   -1.72  114.51   -1.74  122.48    -.99  149.05    -.32
  162.91    -.29  164.16     .08  164.93      .8  173.04     .71  176.91     1.2
  181.83     .75  191.66    1.03  201.49     .72   206.4    1.26  230.97      .6
   240.8      .8  245.71    1.42  250.63    2.69  255.54    3.11  285.03       3
#Mann= 3 , 0 , 0
       0    .055       0   99.26   .0533       0  255.54    .055       0
Bank Sta=99.26,255.54
XS Rating Curve= 0 ,0
Exp/Cntr=0.3,0.1

Type RM Length L Ch R = 1 ,3555.467,174.93,406.42,96.08
XS GIS Cut Line= 2
     393771.1963    5909544.0621     393864.0652    5909290.8553
#Sta/Elev= 30
       0    1.27   29.97    1.45   34.96    1.19   44.95    1.58   54.94    1.37
   64.93    2.29   69.92    1.56   74.92    1.34   85.73    1.38    91.1    -.19
  102.67    -.54  102.69    -.32  106.79    -.74  107.69   -1.19  112.24   -1.23
  117.88   -1.78  131.72   -1.73  134.11   -2.02  145.25   -1.77   150.4   -1.35
  152.35     -.9   153.8   -1.01  163.38    -.08   164.9     .59   166.4     .79
  184.79    1.41  229.74     1.4  239.73    1.75  244.73    2.95   269.7    2.95
#Mann= 3 , 0 , 0
       0    .055       0   85.73   .0533       0  184.79    .055       0
Bank Sta=85.73,184.79
XS Rating Curve= 0 ,0
Exp/Cntr=0.3,0.1

River Reach=Mud Lake C      ,Main

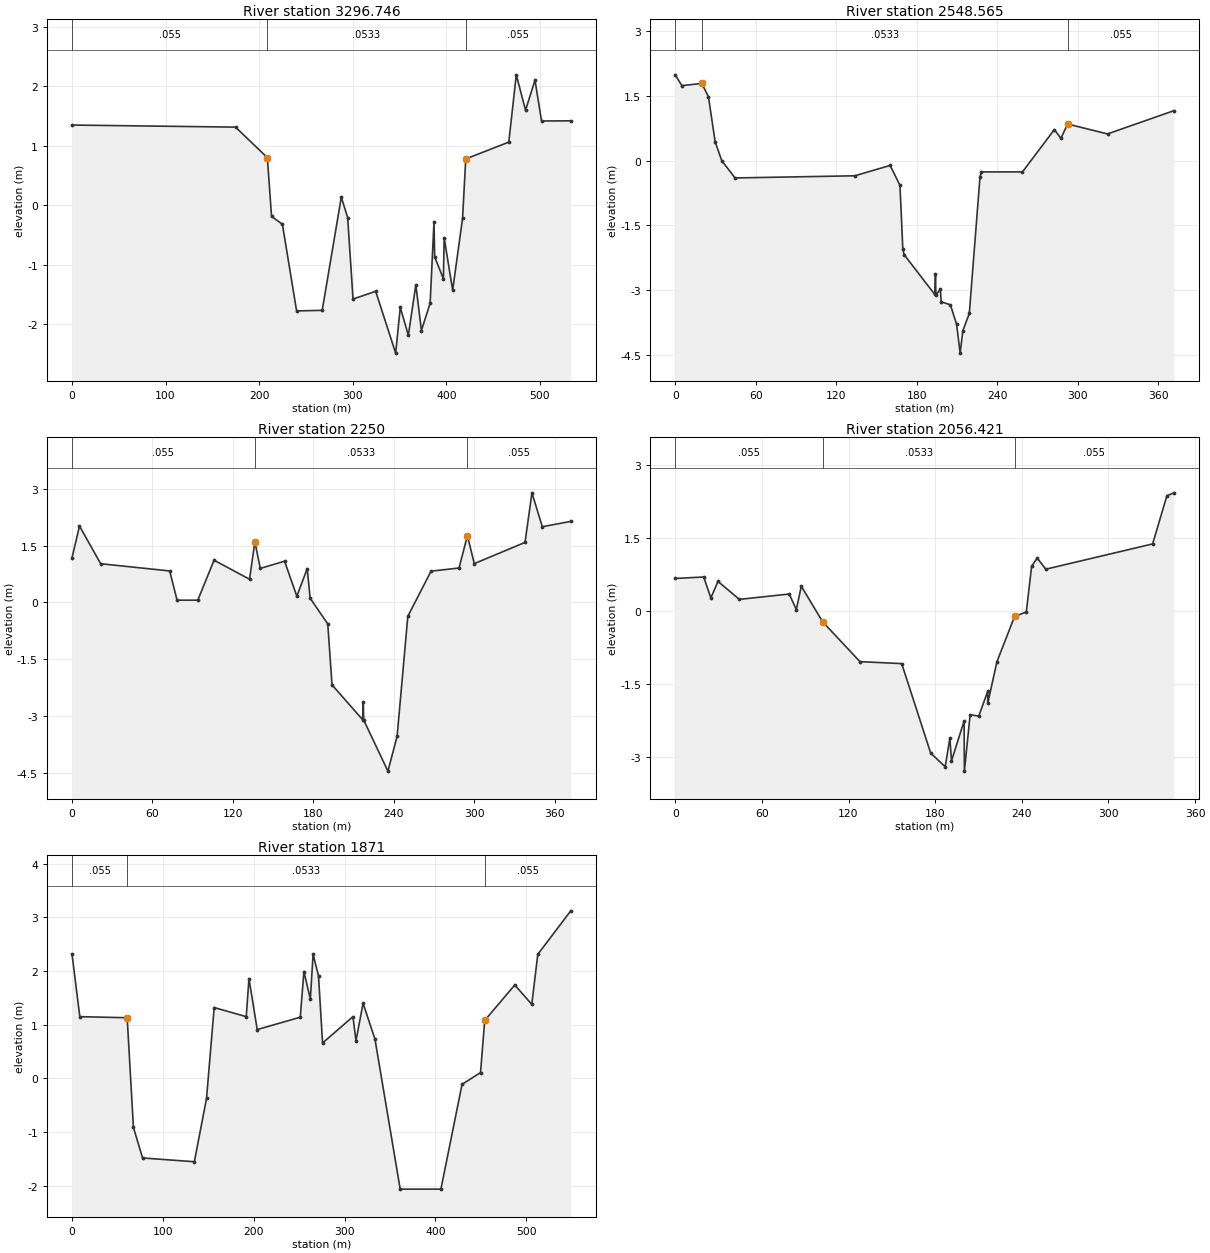
Type RM Length L Ch R = 1 ,3296.746,12.53,147.7,58.22
XS GIS Cut Line= 2
393701.6900129385909587.60951648     394234.7472    5909590.8934
#Sta/Elev= 30
       0   1.348 174.813   1.313 208.814    .799 213.275    -.19 224.865    -.32
 240.055   -1.78 267.425   -1.77 287.816    .135  294.63    -.21  300.36   -1.58
  324.56   -1.45  345.91   -2.49  350.86   -1.72  359.47   -2.19  367.48   -1.34
  373.44   -2.11  382.76   -1.65  386.89    -.28  387.62    -.87  396.93   -1.24
  397.75    -.55  406.83   -1.43  417.42    -.22 420.818    .778 466.819   1.061
 474.819   2.193 484.724   1.598 494.819   2.104  501.82   1.416 533.067   1.419
#Mann= 3 , 0 , 0
       0    .055       0 208.814   .0533       0 420.818    .055       0
Bank Sta=208.814,420.818
XS Rating Curve= 0 ,0
Exp/Cntr=0.3,0.1

Type RM Length L Ch R = 1 ,2548.565,296.22,296.22,296.22
XS GIS Cut Line= 2
     393770.4026    5910241.7697      394107.747    5910398.1388
#Sta/Elev= 30
       0    1.99    4.96    1.74   19.83    1.79   24.79    1.48   29.75     .44
    34.7       0   44.62     -.4  133.86    -.35  160.18    -.11  167.53    -.57
  169.67   -2.05  170.69   -2.18  193.48    -3.1  194.01   -2.63   194.3   -3.11
  197.66   -2.98  198.24   -3.27  205.12   -3.34  209.75   -3.79  212.38   -4.46
  214.41   -3.94  219.23   -3.54  227.21    -.37   228.3    -.26  258.85    -.26
  282.59     .72  287.54     .52   292.5     .85  322.25     .62  371.82    1.16
#Mann= 3 , 0 , 0
       0    .055       0   19.83   .0533       0   292.5    .055       0
Bank Sta=19.83,292.5
XS Rating Curve= 0 ,0
Exp/Cntr=0.3,0.1

Type RM Length L Ch R = 1 ,2250    ,194.53,194.53,194.53
XS GIS Cut Line= 2
393618.4152793485910496.16980559393955.7596793485910652.53890559
#Sta/Elev= 30
       0   1.173   5.604   2.015    21.4   1.019  72.839    .828   78.35    .056
  93.781    .056 105.905   1.112 132.358    .609 136.323     1.6 140.392    .896
 158.467   1.086 167.629     .16 175.344     .89 177.549    .107  190.67    -.57
  193.83   -2.18  216.62    -3.1  217.15   -2.63  217.44   -3.11  235.52   -4.46
  242.37   -3.54  250.35    -.37 267.669    .823 288.506    .906 294.781   1.759
 299.894   1.022 337.708   1.582  342.88   2.892 350.595   1.997 371.823   2.137
#Mann= 3 , 0 , 0
       0    .055       0 136.323   .0533       0 294.781    .055       0
Bank Sta=136.323,294.781
XS Rating Curve= 0 ,0
Exp/Cntr=0.3,0.1

Type RM Length L Ch R = 1 ,2056.421,185,185,185
XS GIS Cut Line= 2
393607.8293380855910591.91434684393770.8354096455910900.42248424
#Sta/Elev= 30
       0     .67   19.74      .7   24.67     .27   29.61     .61   44.41     .24
   78.95     .35   83.88     .03    87.3     .51  102.08    -.22  127.93   -1.04
  156.83   -1.08  176.91   -2.92  186.96    -3.2   190.2   -2.61  191.31   -3.08
  200.04   -2.26  200.24   -3.29  204.23   -2.13  210.18   -2.16  216.39   -1.65
  216.46   -1.89  222.79   -1.04  235.01    -.11  243.11    -.02   246.8     .92
  250.68    1.09  256.58     .86  330.59    1.38  340.46    2.37   345.4    2.43
#Mann= 3 , 0 , 0
       0    .055       0  102.08   .0533       0  235.01    .055       0
Bank Sta=102.08,235.01
XS Rating Curve= 0 ,0
Exp/Cntr=0.3,0.1

Type RM Length L Ch R = 1 ,1871    ,0,0,0
XS GIS Cut Line= 3
393532.8903050245910607.23035359393498.9762897065910872.52547194
393754.4351270725910991.04652588
#Sta/Elev= 30
       0    2.32    8.64    1.15   60.76    1.13   67.63    -.91    77.7   -1.48
   134.7   -1.55  148.12    -.37  156.53    1.32  191.82    1.15  194.84    1.86
  203.92     .91   251.3    1.14  255.31    1.99  262.39    1.48  265.41    2.31
  271.38    1.91  275.84     .66  309.28    1.15  312.63      .7  320.43     1.4
  333.56     .73   361.3   -2.06  406.12   -2.06  429.39    -.11  449.73     .11
  454.34    1.08  487.41    1.74  506.15    1.38  512.77    2.31  549.08    3.12
#Mann= 3 , 0 , 0
       0    .055       0   60.76   .0533       0  454.34    .055       0
Bank Sta=60.76,454.34
XS Rating Curve= 0 ,0
Exp/Cntr=0.3,0.1

River Reach=Mud Lake In     ,In

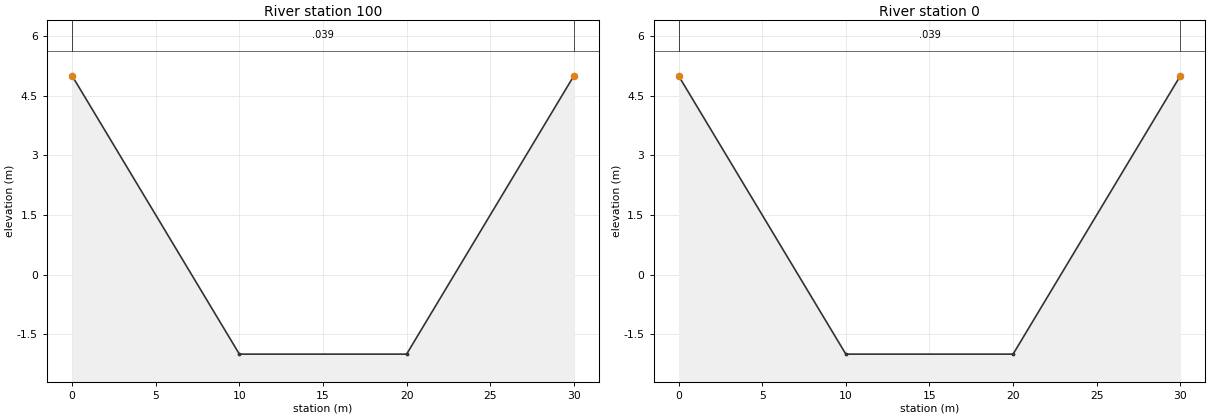
Type RM Length L Ch R = 1 ,100     ,100,100,100
XS GIS Cut Line= 5
395304.3067021795905197.93905802395304.3067021795905197.93905802
395299.2126349185905104.54782489395294.1185676575905011.15659176
395294.1185676575905011.15659176
#Sta/Elev= 4
       0       5      10      -2      20      -2      30       5
#Mann= 3 , 0 , 0
       0     .03       0       0    .039       0      30     .03       0
Bank Sta=0,30
XS Rating Curve= 0 ,0
Exp/Cntr=0.3,0.1

Type RM Length L Ch R = 1 ,0       ,0,0,0
XS GIS Cut Line= 5
 395762.093200675905278.70280939 395762.093200675905278.70280939
395840.9106316165905228.34722851395919.7280625625905177.99164763
395919.7280625625905177.99164763
#Sta/Elev= 4
       0       5      10      -2      20      -2      30       5
#Mann= 3 , 0 , 0
       0     .03       0       0    .039       0      30     .03       0
Bank Sta=0,30
XS Rating Curve= 0 ,0
Exp/Cntr=0.3,0.1

River Reach=Churchill River ,Main DS
Reach XY= 30
392769.8948848085911242.63821614392769.7238922575911242.46722359
     392772.3149     5911255.552     392814.3388    5911398.6122
      392832.745    5911550.1834     392832.5598    5911676.5487
     392796.5764    5911881.8658     392756.3596    5912027.9161
     392737.0326    5912083.6011     392727.0819    5912112.2715
      392720.153    5912132.2349     392707.4456    5912168.8477
392701.4818186035912185.34551994392697.9963241295912199.12185874
392695.8341739975912207.77045927     392695.2863    5912216.4103
      392688.594    5912242.6005     392681.5458     5912285.916
     392677.5666    5912326.4725     392674.8356    5912415.4487
     392684.1423    5912543.1765392703.5789864885912660.37382837
     392733.0904    5912758.8124     392786.0071    5912932.1148
     392949.1619    5913359.9371     393036.3696    5913645.8298
     393062.4973    5913758.3882     393090.6093    5913917.0282
     393119.7135     5914233.206     393151.7357    5914612.8969