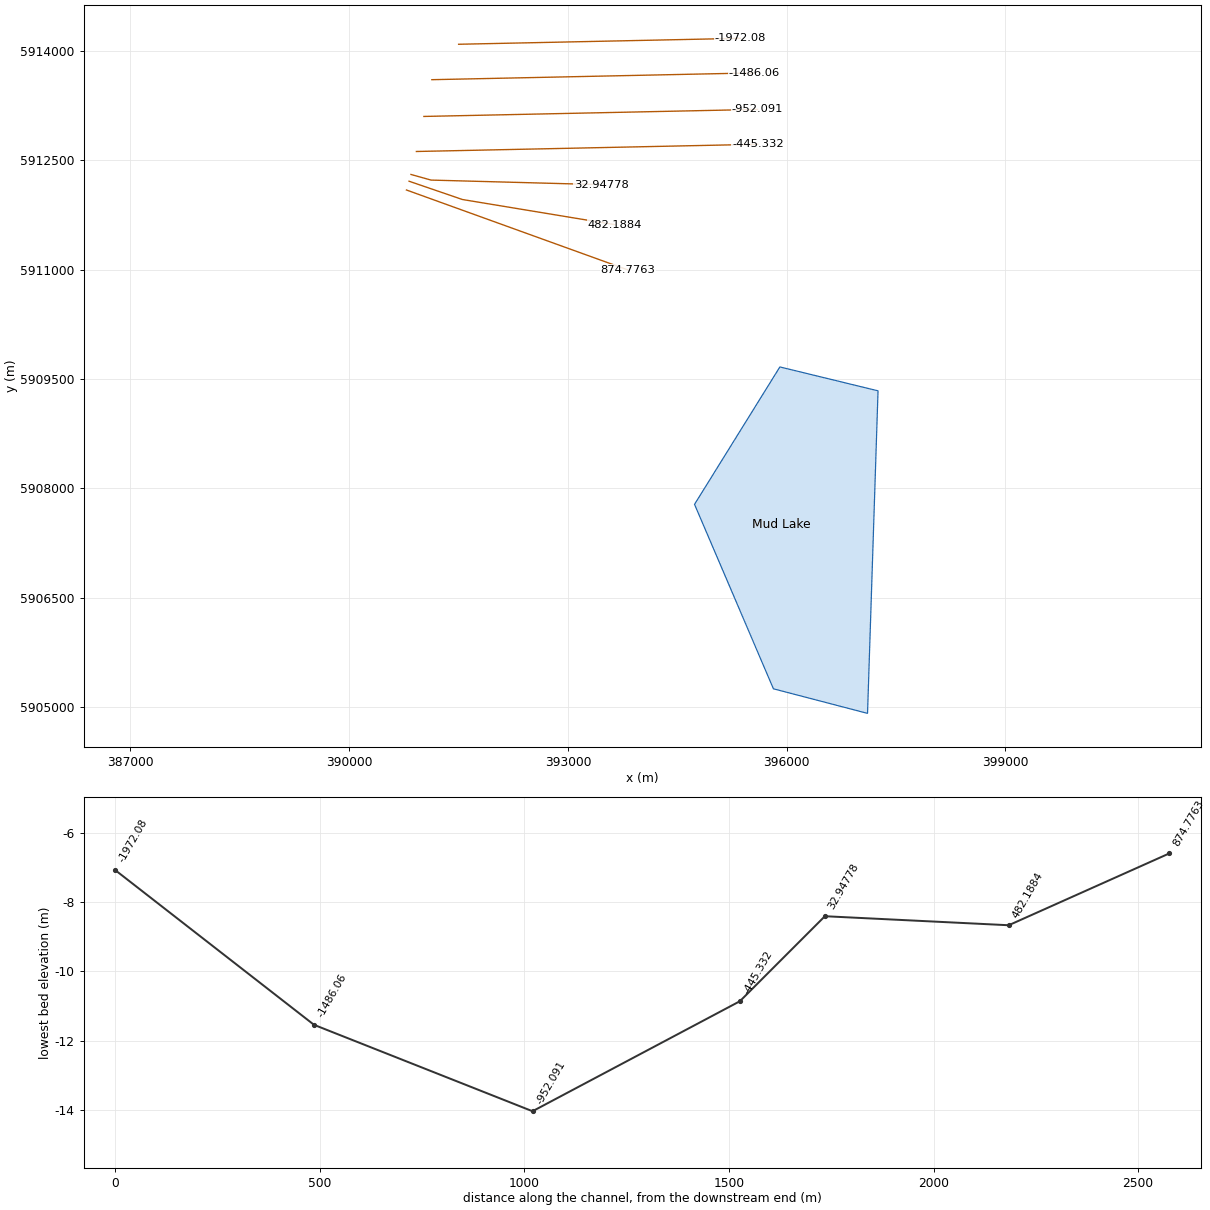
HEC-RAS study Churchill_Mapping.prj: Churchill River Flood Risk Mapping

--- Churchill_Mapping.g19 (geometry) --- (continued)

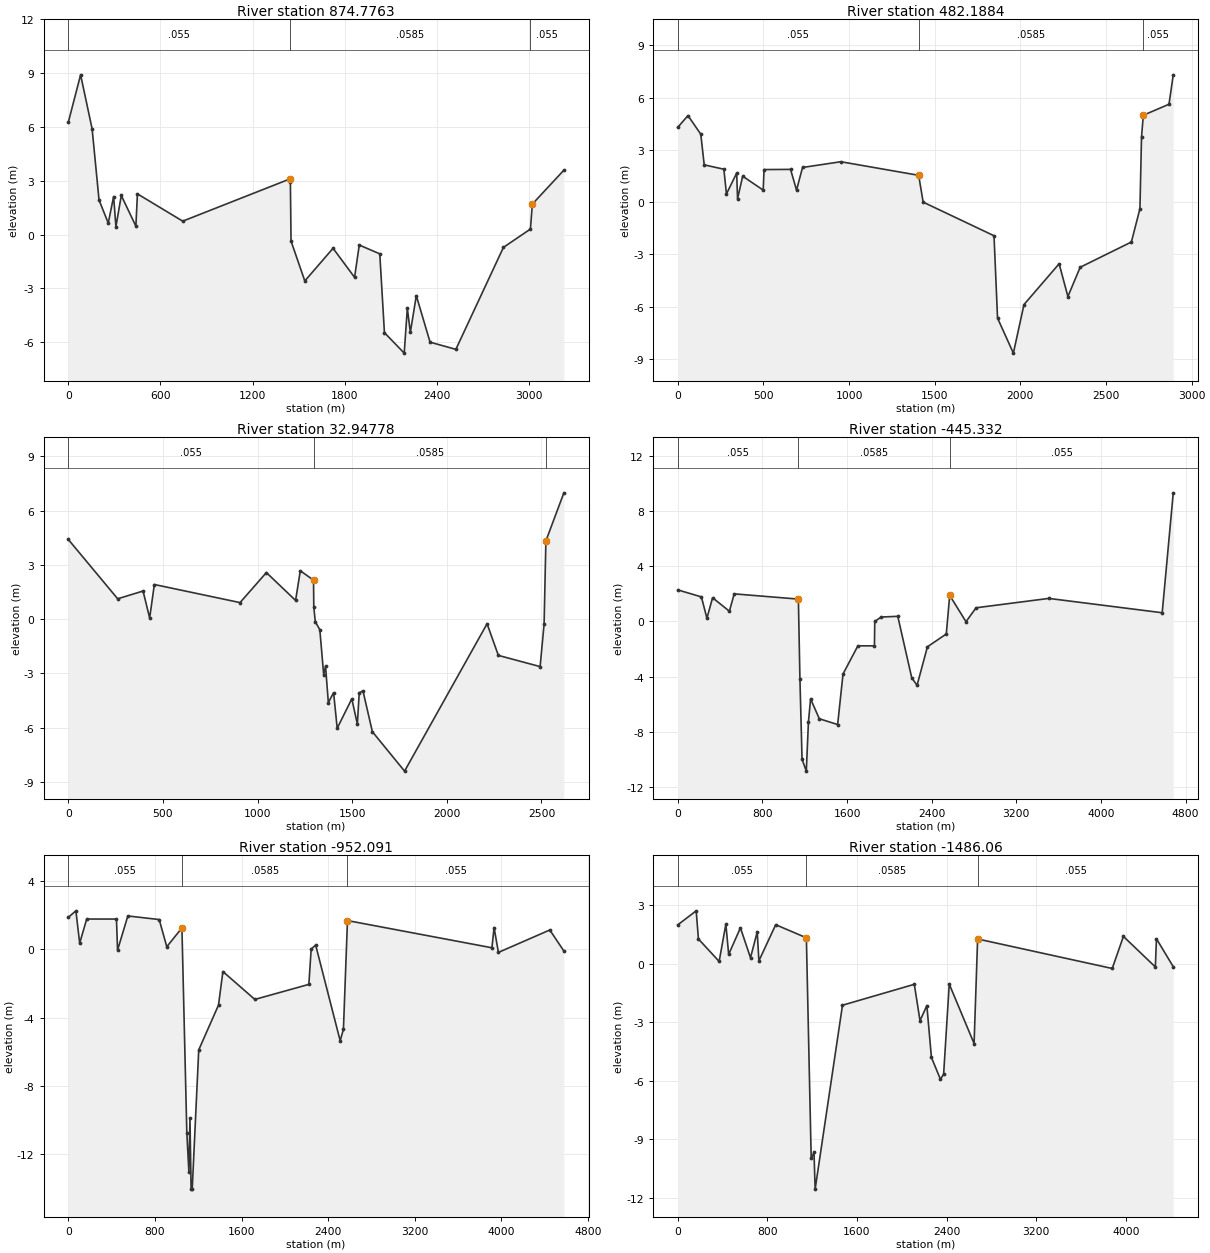
Type RM Length L Ch R = 1 ,874.7763,130.1,392.59,1051.87
XS GIS Cut Line= 2
     390785.9067    5912091.0588     393820.2728      5910995.65
#Sta/Elev= 30
       0    6.26   79.98     8.9  154.96    5.89  199.95    1.93  259.94     .64
  294.93    2.12  309.93     .44  344.92    2.18   439.9     .47   449.9    2.27
  744.83     .75 1444.97    3.11 1445.63    2.91  1449.9    -.36 1539.55   -2.58
 1723.42    -.76  1863.6   -2.38 1894.03    -.58 2027.62   -1.07 2057.93   -5.46
 2186.72    -6.6 2206.94   -4.11 2226.61   -5.44 2265.44    -3.4 2355.05   -5.99
 2522.92   -6.39 2832.65    -.71 3008.39     .31 3020.78     1.7 3226.03    3.59
#Mann= 3 ,-1 , 0
       0    .055       0 1445.63   .0585       0 3008.39    .055       0
Bank Sta=1444.97,3020.78
XS Rating Curve= 0 ,0
Exp/Cntr(USF)=0.5,0.3
Exp/Cntr=0.5,0.3

Type RM Length L Ch R = 1 ,482.1884,112.67,449.24,807.63
XS GIS Cut Line= 5
     390821.6015    5912211.3718      391553.291    5911960.6071
     392048.4026     5911878.808     392049.5722    5911878.6148
393644.0986969595911615.17765598
#Sta/Elev= 30
       0    4.29   59.88    4.97  134.73     3.9  154.69    2.14  269.47    1.89
  284.44     .47  344.32    1.67  349.31     .19  379.25    1.49  499.01     .69
     504    1.87  658.69    1.88  693.63     .69  728.56    1.99  952.34    2.32
 1406.43    1.54 1432.73       0 1846.32   -1.93 1866.93   -6.66  1959.3   -8.67
 2021.33   -5.88 2226.43   -3.54 2277.58   -5.42 2349.14   -3.74 2648.16   -2.29
 2698.07    -.38 2707.39    3.75 2717.95    4.99 2867.68    5.62 2892.62    7.31
#Mann= 3 , 0 , 0
       0    .055       0 1406.43   .0585       0 2717.95    .055       0
Bank Sta=1406.43,2717.95
XS Rating Curve= 0 ,0
Exp/Cntr(USF)=0.5,0.3
Exp/Cntr=0.5,0.3

Type RM Length L Ch R = 1 ,32.94778,207.75,207.75,207.75
XS GIS Cut Line= 5
     390848.0599    5912303.9762     391122.9355    5912226.9858
     392022.9791    5912202.7855     393444.9376     5912164.552
393454.9701555535912164.28224541
#Sta/Elev= 30
       0     4.4  260.85    1.12  394.89    1.55  429.71     .06  454.58    1.91
  907.26     .91 1046.54    2.57  1200.8    1.03 1225.75    2.67 1295.63    2.15
 1296.99     .67 1304.89    -.15 1328.88    -.59 1349.33   -3.08 1359.13   -2.61
 1373.84   -4.62 1401.63   -4.07 1420.65   -6.04 1497.82   -4.41 1527.11   -5.81
 1537.09   -4.08 1556.75   -3.97 1606.47   -6.23 1776.63   -8.41 2212.53    -.26
 2272.25   -2.01 2492.79   -2.63 2513.79    -.28 2523.36    4.32  2618.3    6.98
#Mann= 3 , 0 , 0
       0    .055       0 1295.63   .0585       0 2523.36    .055       0
Bank Sta=1295.63,2523.36
XS Rating Curve= 0 ,0
Exp/Cntr(USF)=0.5,0.3
Exp/Cntr=0.5,0.3

Type RM Length L Ch R = 1 ,-445.332,503.69,506.76,490.08
XS GIS Cut Line= 2
     390922.1354    5912619.2117     395604.1073    5912717.8173
#Sta/Elev= 30
       0    2.29  223.91    1.78  276.06     .23   329.5    1.72  488.35     .74
   533.9       2  1140.3    1.62 1154.96   -4.16 1175.05     -10 1215.24  -10.86
 1235.39   -7.29 1255.77   -5.62 1338.17   -7.06 1511.34   -7.48 1562.29   -3.81
 1702.69   -1.77 1859.05   -1.77 1862.23       0 1922.54     .32 2079.76     .37
 2211.82    -4.1 2262.08   -4.63 2359.67   -1.84 2538.18    -.91 2570.34    1.89
 2724.33    -.02 2819.36     .99 3506.61    1.67 4578.46     .63 4683.01    9.33
#Mann= 3 , 0 , 0
       0    .055       0  1140.3   .0585       0 2570.34    .055       0
Bank Sta=1140.3,2570.34
XS Rating Curve= 0 ,0
Exp/Cntr=0.3,0.1

Type RM Length L Ch R = 1 ,-952.091,534.3,533.97,511.38
XS GIS Cut Line= 2
     391024.7287    5913099.8707     395599.7588    5913196.2241
#Sta/Elev= 30
       0    1.86   69.94    2.24  104.91     .35  169.85    1.76  444.62    1.76
  454.61    -.06  549.52    1.94  839.28    1.73  909.21     .14 1049.09    1.24
  1094.3  -10.74 1113.27  -13.02 1123.35    -9.9 1133.78  -14.03 1144.23  -14.02
 1204.32   -5.89 1386.91   -3.27  1427.4   -1.31 1722.41   -2.94 2221.13   -2.06
 2242.52       0 2283.87     .24 2510.54   -5.36 2540.43   -4.68 2577.77    1.67
  3911.6     .08 3931.58    1.26 3971.55    -.19 4446.13    1.12 4576.01    -.11
#Mann= 3 , 0 , 0
       0    .055       0 1049.09   .0585       0 2577.77    .055       0
Bank Sta=1049.09,2577.77
XS Rating Curve= 0 ,0
Exp/Cntr=0.3,0.1

Type RM Length L Ch R = 1 ,-1486.06,487.84,486.02,490.18
XS GIS Cut Line= 2
     391133.8455    5913604.0628     395556.5846    5913697.2088
#Sta/Elev= 30
       0    1.98  164.95     2.7  184.95    1.26  369.89     .11  429.88    2.02
  454.87     .47  559.84    1.83  649.81      .3  709.79    1.62  724.79     .14
  874.75    1.99 1148.59    1.32 1191.67   -9.97  1216.7   -9.66 1226.86  -11.54
 1470.92   -2.13 2112.22   -1.06 2162.92   -2.92 2224.21   -2.15 2264.84    -4.8
 2345.45   -5.92  2373.8   -5.66 2423.99   -1.05 2645.68   -4.09 2677.29    1.26
 3878.88    -.25 3978.85    1.39 4263.76    -.17 4273.76    1.27 4423.72    -.16
#Mann= 3 , 0 , 0
       0    .055       0 1148.59   .0585       0 2677.29    .055       0
Bank Sta=1148.59,2677.29
XS Rating Curve= 0 ,0
Exp/Cntr=0.3,0.1

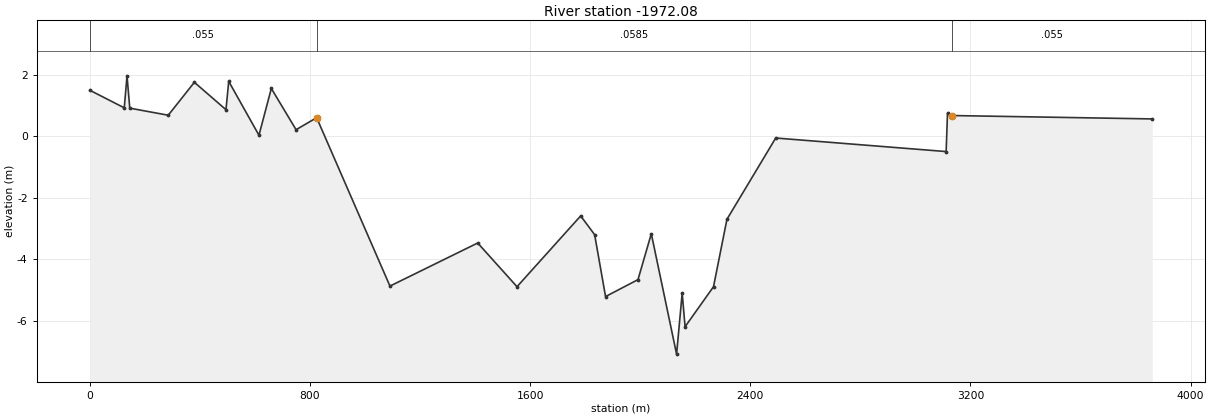
Type RM Length L Ch R = 1 ,-1972.08,100,100,100
XS GIS Cut Line= 2
      391501.249    5914089.8532     395361.2289    5914171.1471
#Sta/Elev= 30
       0    1.49  124.87     .92  134.85    1.96  144.84     .91  284.69     .68
  379.59    1.75  494.47     .86  504.46    1.78  614.34     .03  659.29    1.55
  749.19     .21  824.04      .6  1090.4   -4.87  1409.3   -3.47 1552.14   -4.89
  1783.5   -2.59 1834.26    -3.2 1873.89   -5.21 1991.78   -4.66 2040.17   -3.17
 2132.07   -7.08 2152.39    -5.1 2162.92   -6.19 2266.22   -4.89 2315.06    -2.7
 2492.31    -.06 3111.65     -.5 3116.64     .75 3132.86     .67 3860.84     .56
#Mann= 3 , 0 , 0
       0    .055       0  824.04   .0585       0 3132.86    .055       0
Bank Sta=824.04,3132.86
XS Rating Curve= 0 ,0
Exp/Cntr=0.3,0.1

Storage Area=Mud Lake        ,396360.7636923,5907381.7871506
Storage Area Surface Line= 6
   394736.733584 5907779.6846083
  395907.3849677 5909664.4333359
  397253.6340588 5909336.6509485
  397109.6146895 5904912.8256111
  395818.8498631 5905249.7865669
   394736.733584 5907779.6846083
Storage Area Type= 0
Storage Area Area=8000
Storage Area Min Elev=-5
Storage Area Vol Elev= 1
               0