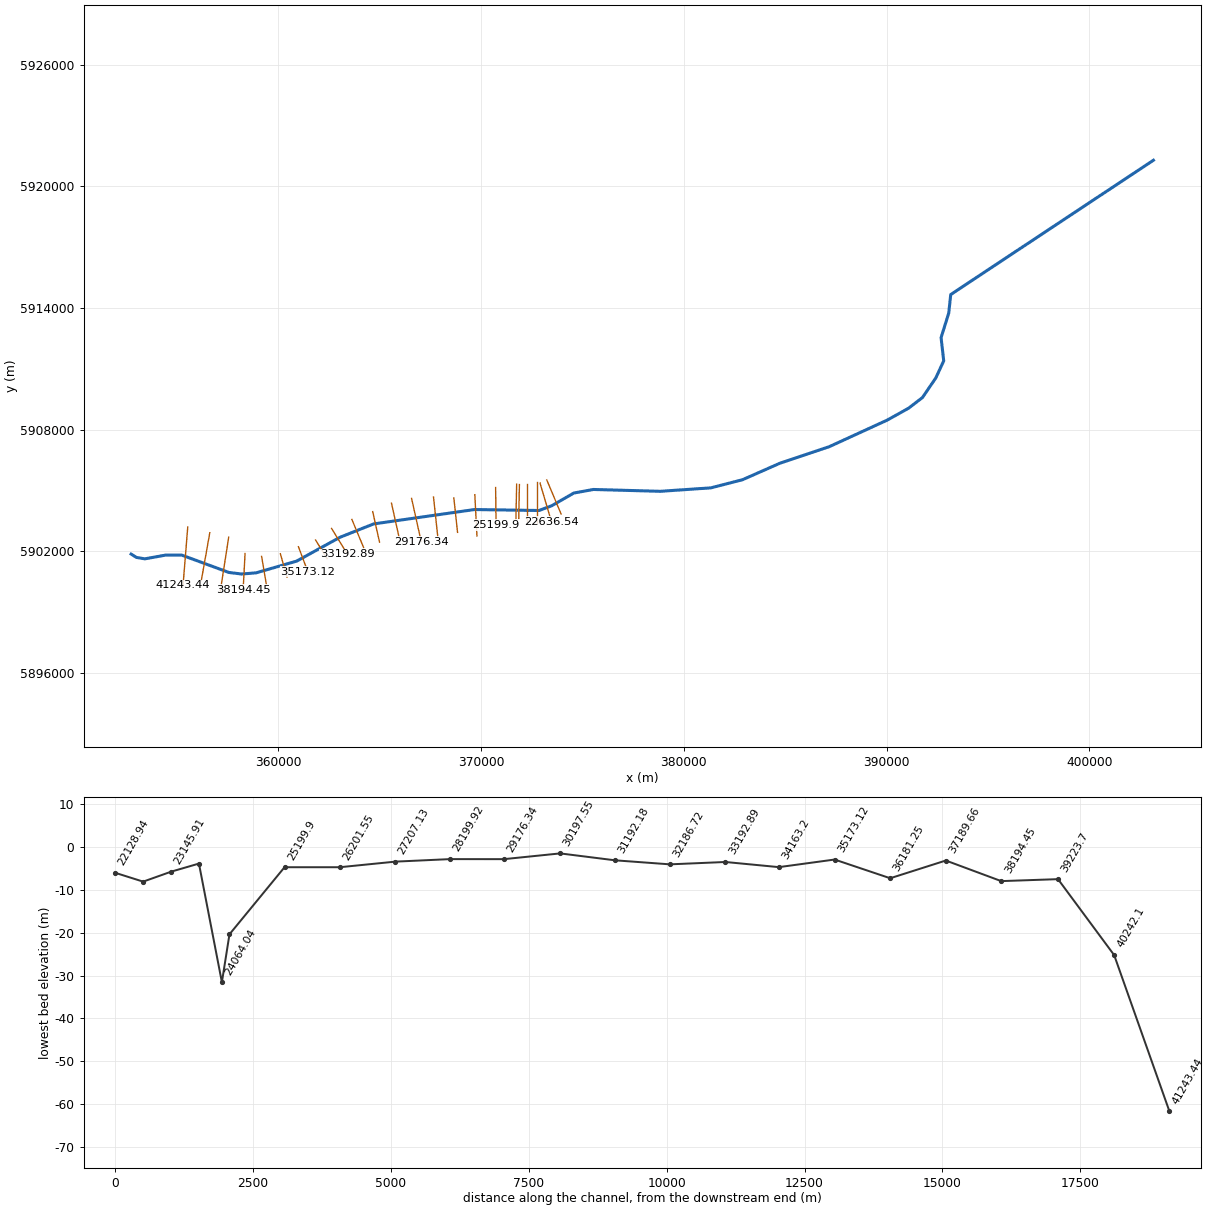
HEC-RAS study Churchill_Forecasting.prj: ChurchillRiver_Forecasting

--- Churchill_Forecasting.u04 (unsteady flow) ---

Flow Title=2018 Jun - Aug
Program Version=4.10
Use Restart= 0
Initial Flow Loc=Churchill River ,Main            ,41243.44,3785
Boundary Location=Churchill River ,Main            ,41243.44,        ,                ,                ,
Interval=1HOUR
Flow Hydrograph= 1464
3785.4953784.7843786.4073788.1633788.2973789.1953790.6283793.211 3793.843796.502
4062.073 4052.46 4052.434053.3744054.375 4051.344052.2834172.9424172.6184172.556
4172.8494169.3094173.5294174.889 4320.684324.4854325.849 4328.354331.2034336.247
4518.1644522.8344527.735 4861.824834.1724834.5894837.2894844.1584840.5024843.471
4847.7894999.2415006.7425014.9725020.9335023.9935024.8135027.3055078.4635082.915
5080.8165086.5415083.138  5086.75087.0825087.4635087.5595095.0045087.2415089.754
 5091.445085.937 5087.055084.8555082.7565081.2295079.2585081.3564943.4724950.209
4948.3694951.0834953.5474949.616 4950.244952.6114949.7414950.646 4955.174944.251
4942.8174936.8614931.4064928.9434924.7064925.5164639.7574662.5664663.9634663.797
4667.349 4669.224671.1144667.3494668.675 4666.974668.8884666.3074666.4024664.981
4662.2344658.7534658.3514655.0594650.5354648.2614426.744 4440.374444.2284440.438
4446.7314444.0024445.5134441.1824443.528 4439.314441.0474439.6254302.4464312.324
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Use DSS=False
CWMS InputPosition= 0
Use Fixed Start Time=False
Is Critical Boundary=False
Boundary Location=Churchill River ,Main            ,-12000  ,        ,                ,                ,
Interval=1HOUR
Stage Hydrograph= 1464
  .00278   .0838   .0798   .0107   -.058-.127543-.196668-.265792-.334917-.360933
-.300732-.240531-.180331 -.12013   -.097-.145973-.194101-.242229-.290358-.338486
 -.37154-.290459-.209378-.128297   -.047   .0338.1149459   .0533   -.015   -.084
-.154041-.223165 -.29229-.361414-.338425-.279019-.219613-.160208-.100802-.113171
-.161428-.209686-.257943-.306201-.354458-.351411-.285657-.219904 -.15415   -.088
   -.022   -.001   -.055 -.11068-.165474-.220269-.275063-.329858-.377141-.319263
-.261385-.203508 -.14563   -.087-.109882 -.14258-.175277-.207975-.240673 -.27337
-.242452-.192173-.141893   -.091   -.041  .00894-.024049   -.077-.131672-.185484
-.239295-.293107-.346919-.360754-.305539-.250325 -.19511-.139895   -.084-.112728
-.146722-.180716-.214711-.248705 -.27845-.227459-.176467-.125475   -.074   -.023
   .0102   -.042   -.095-.148032 -.20078-.253527-.306274-.359022   -.361-.326714
-.292428-.258142-.223857-.189571-.194636-.212818   -.231-.249181-.267363-.268324
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Use DSS=False
CWMS InputPosition= 0
Use Fixed Start Time=False
Is Critical Boundary=False

--- Churchill_Forecasting.u05 (unsteady flow) ---

Flow Title=2017 Jun - Aug
Program Version=4.10
Use Restart= 0
Initial Flow Loc=Churchill River ,Main            ,41243.44,1600
Boundary Location=Churchill River ,Main            ,41243.44,        ,                ,                ,
Interval=1HOUR
Flow Hydrograph= 2209
    15751577.0831579.167 1581.251583.3331585.417  1587.51589.5831591.667 1593.75
1595.8331597.917    16001602.0921604.1981606.3181608.4491610.5891612.7341614.885
1617.0371619.189 1621.341623.4861625.6251627.7561629.8761631.9821634.0741636.148
1638.2031640.2361642.2451644.2291646.1831648.108    1650  1651.91653.843 1655.82
1657.8241659.8451661.8751663.9051665.926 1667.931669.907 1671.85 1673.751675.598
1677.3841679.1021680.7411682.293 1683.751685.1031686.3431687.4611688.4491689.298
    16901690.5651691.0131691.3481691.5741691.6961691.7191691.6461691.481 1691.23
1690.8971690.485    16901689.4451688.8251688.1451687.4071686.6181685.7811684.901
1683.9811683.0271682.0431681.032    16801678.8161677.3671675.6841673.7961671.735
1669.5311667.2141664.8151662.363 1659.891657.426    16551652.6441650.3881648.262
1646.2961644.5221642.9691641.6671640.6481639.9411639.5781639.587    16401640.596
1641.1551641.7091642.2921642.9351643.6721644.5351645.5561646.7681648.2031649.895
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Use DSS=False
CWMS InputPosition= 0
Use Fixed Start Time=False
Is Critical Boundary=False
Boundary Location=Churchill River ,Main            ,-12000  ,        ,                ,                ,
Interval=1HOUR
Stage Hydrograph= 2209
-.0888743.17E-037.80E-02.1174316.10539154.76E-02-3.9E-02-.141688-.241794-.324467
-.373922-.375031-.329945-.257984-.179035-.112983-7.9E-02-8.9E-02-.129984-.185200
-.239402-.276796-.281586-.241135-.165392-7.2E-021.77E-028.80E-02.11935369.86E-02
3.55E-02-5.4E-02-.156294-.254149-.332753-.376694-.372100-.324971-.253746-.176916
-.112971-8.0E-02-8.8E-02-.126231-.178548-.231375-.270394-.281288-.253877-.197437
-.126944-5.7E-02-3.6E-031.91E-022.69E-05-5.3E-02-.127736-.210583-.288849-.349613
-.379957-.368591-.321178-.253262-.180502-.118553-.083071-8.5E-02-.119371-.169556
-.222642-.264788-.282152-.262334-.209947-.140279-6.8E-02-1.0E-02.01811594.03E-03
-4.8E-02-.125883-.212390-.293668-.355022-.381754-.360687-.297494-.210273-.117327
-3.6E-021.25E-021.49E-02-2.4E-02-9.0E-02-.164689-.231557-.274179-.276205-.234984
-.167153-9.0E-02-2.3E-021.51E-029.69E-03-3.9E-02-.116145-.204801-.289226-.353374
-.381204-.359742-.297396-.211638-.119973-3.9E-02.01106331.72E-02-1.7E-02-7.8E-02
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Use DSS=False
CWMS InputPosition= 0
Use Fixed Start Time=False
Is Critical Boundary=False

--- Churchill_Forecasting.u06 (unsteady flow) ---

Flow Title=2017 Oct - Nov
Program Version=4.10
Use Restart= 0
Initial Flow Loc=Churchill River ,Main            ,41243.44,1500
Boundary Location=Churchill River ,Main            ,41243.44,        ,                ,                ,
Interval=1HOUR
Flow Hydrograph= 744
    1508    1507    1507    1507    1507    1508    1507    1507    1507    1507
    1508    1508    1429    1429    1429    1429    1429    1429    1429    1429
    1429    1429    1430    1430    1430    1430    1430    1430    1430    1430
    1430    1431    1431    1431    1431    1431    1432    1432    1432    1432
    1432    1432    1403    1402    1403    1403    1402    1403    1403    1402
    1402    1402    1402    1402    1402    1402    1402    1402    1402    1341
    1341    1341    1342    1342    1342    1341    1342    1342    1341    1341
    1341    1341    1341    1341    1341    1341    1341    1341    1341    1340
    1340    1340    1340    1340    1309    1310    1310    1310    1310    1310
    1310    1311    1311    1311    1311    1311    1311    1311    1311    1312
    1312    1312    1312    1312    1312    1312    1312    1313    1403    1403
    1403    1403    1403    1403    1403    1403    1403    1402    1402    1402
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Use DSS=False
CWMS InputPosition= 0
Use Fixed Start Time=False
Is Critical Boundary=False
Boundary Location=Churchill River ,Main            ,-12000  ,        ,                ,                ,
Interval=1HOUR
Stage Hydrograph= 744
-.216993-.294926-.353979-.380924-.364158-.310257-.237014-.162376-.104291-8.0E-02
-.103121-.159537-.232809-.305787-.361323-.382266-.354053-.284663-.193398-9.9E-02
-2.2E-021.78E-026.93E-03-4.7E-02-.127895-.218468-.302245-.362552-.382713-.348846
-.271477-.173249-7.6E-02-5.0E-031.95E-02-.013127-8.6E-02-.179808-.273557-.347392
-.381173-.357687-.286066-.189374-.090802-1.3E-021.92E-02-9.6E-03-8.7E-02-.193304
-.306294-.405486-.469956-.478779-.420454-.315681-.191924-7.6E-022.69E-032.08E-02
-.019844-9.8E-02-.195201-.288362-.357493-.381829-.346612-.266790-.166410-6.9E-02
-1.7E-041.75E-02-2.7E-02-.116385-.228078-.340495-.431823-.480248-.464672-.385991
-.270578-.146221-4.0E-021.81E-021.22E-02-4.4E-02-.131296-.228347-.315220-.371638
-.377380-.324786-.234671-.131770-4.0E-021.34E-026.95E-03-6.0E-02-.164652-.282949
-.391254-.465822-.482914-.422843-.302320-.154552-1.2E-028.97E-02.12045097.11E-02
-3.3E-02-.167606-.303891-.415978-.477267-.463207-.380574-.259896-.132223-2.8E-02
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Use DSS=False
CWMS InputPosition= 0
Use Fixed Start Time=False
Is Critical Boundary=False

--- Churchill_Forecasting.u07 (unsteady flow) ---

Flow Title=2018 Jun - Aug Clipped
Program Version=4.10
Use Restart= 0
Initial Flow Loc=Churchill River ,Main            ,41243.44,3785
Boundary Location=Churchill River ,Main            ,41243.44,        ,                ,                ,
Interval=1HOUR
Flow Hydrograph= 1464
3785.4953784.7843786.4073788.1633788.2973789.1953790.6283793.211 3793.843796.502
4062.073 4052.46 4052.434053.3744054.375 4051.344052.2834172.9424172.6184172.556
4172.8494169.3094173.5294174.889 4320.684324.4854325.849 4328.354331.2034336.247
4518.1644522.8344527.735 4861.824834.1724834.5894837.2894844.1584840.5024843.471
4847.7894999.2415006.7425014.9725020.9335023.9935024.8135027.3055078.4635082.915
5080.8165086.5415083.138  5086.75087.0825087.4635087.5595095.0045087.2415089.754
 5091.445085.937 5087.055084.8555082.7565081.2295079.2585081.3564943.4724950.209
4948.3694951.0834953.5474949.616 4950.244952.6114949.7414950.646 4955.174944.251
4942.8174936.8614931.4064928.9434924.7064925.5164639.7574662.5664663.9634663.797
4667.349 4669.224671.1144667.3494668.675 4666.974668.8884666.3074666.4024664.981
4662.2344658.7534658.3514655.0594650.5354648.2614426.744 4440.374444.2284440.438
4446.7314444.0024445.5134441.1824443.528 4439.314441.0474439.6254302.4464312.324
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Use DSS=False
CWMS InputPosition= 0
Use Fixed Start Time=False
Is Critical Boundary=False
Boundary Location=Churchill River ,Main            ,32.94778,        ,                ,                ,
Interval=1HOUR
Stage Hydrograph= 1464
    .307     .36     .36    .333    .286    .245    .212.1670001    .159    .144
    .143    .194.2549999    .299    .313    .314    .302    .266    .245    .215
.2380001     .26.3149999    .377    .446.5429999    .576    .572.5470001    .524
    .472    .452    .413    .386    .371    .396    .423    .448    .488    .513
    .502    .484.4649999    .449    .443    .433    .444    .486.5419999    .601
    .622    .637     .65.5920001    .581.5669999.5519999    .507    .488      .5
    .501    .506    .553    .565    .573    .577     .56    .543.5140001.5089999
.4800001    .492    .504    .548.6019999    .602    .611    .578    .539.5000001
    .488     .45    .463    .436.4270001    .471    .469    .485     .51    .514
    .516    .489    .456    .428    .418    .394.3980001    .443    .501     .55
    .566    .534    .531    .494    .471    .439    .409    .388    .374    .361
.4029999    .412    .445    .443    .447    .446     .44    .418    .395    .385
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Use DSS=False
CWMS InputPosition= 0
Use Fixed Start Time=False
Is Critical Boundary=False

--- Churchill_Forecasting.u08 (unsteady flow) ---

Flow Title=2017 Jun - Aug Clipped
Program Version=4.10
Use Restart= 0
Initial Flow Loc=Churchill River ,Main            ,41243.44,1575
Boundary Location=Churchill River ,Main            ,41243.44,        ,                ,                ,
Interval=1HOUR
Flow Hydrograph= 2209
    15751577.0831579.167 1581.251583.3331585.417  1587.51589.5831591.667 1593.75
1595.8331597.917    16001602.0921604.1981606.3181608.4491610.5891612.7341614.885
1617.0371619.189 1621.341623.4861625.6251627.7561629.8761631.9821634.0741636.148
1638.2031640.2361642.2451644.2291646.1831648.108    1650  1651.91653.843 1655.82
1657.8241659.8451661.8751663.9051665.926 1667.931669.907 1671.85 1673.751675.598
1677.3841679.1021680.7411682.293 1683.751685.1031686.3431687.4611688.4491689.298
    16901690.5651691.0131691.3481691.5741691.6961691.7191691.6461691.481 1691.23
1690.8971690.485    16901689.4451688.8251688.1451687.4071686.6181685.7811684.901
1683.9811683.0271682.0431681.032    16801678.8161677.3671675.6841673.7961671.735
1669.5311667.2141664.8151662.363 1659.891657.426    16551652.6441650.3881648.262
1646.2961644.5221642.9691641.6671640.6481639.9411639.5781639.587    16401640.596
1641.1551641.7091642.2921642.9351643.6721644.5351645.5561646.7681648.2031649.895
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Use DSS=False
CWMS InputPosition= 0
Use Fixed Start Time=False
Is Critical Boundary=False
Boundary Location=Churchill River ,Main            ,32.94778,        ,                ,                ,
Interval=1HOUR
Stage Hydrograph= 2209
   -.023    .075    .152    .173     .16    .119    .056   -.015   -.082   -.147
   -.199   -.227   -.236    -.19    -.13   -.077   -.041   -.055   -.091   -.137
   -.188   -.232    -.25   -.255   -.227   -.168   -.091    -.02    .015    .008
   -.036   -.097    -.16   -.221   -.279   -.317   -.343   -.336   -.283   -.204
   -.151   -.117   -.121   -.155   -.202   -.243   -.269   -.288   -.281   -.246
   -.176   -.109   -.048   -.025   -.034    -.07   -.125   -.185    -.24   -.293
   -.337   -.349   -.337   -.288   -.214   -.145   -.107   -.102   -.142   -.187
   -.222   -.253    -.26   -.265    -.24    -.19   -.107   -.058   -.036   -.048
   -.082   -.124   -.181   -.229   -.267   -.304   -.306   -.281   -.205   -.128
   -.061   -.019   -.012   -.029   -.071   -.111   -.143   -.169   -.175   -.159
   -.109   -.028    .041    .084    .089    .055   -.001   -.048   -.093   -.134
   -.162   -.147   -.105   -.038    .065    .138    .186    .201     .18    .124
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Use DSS=False
CWMS InputPosition= 0
Use Fixed Start Time=False
Is Critical Boundary=False

--- Churchill_Forecasting.u09 (unsteady flow) ---

Flow Title=2017 Oct - Nov Clipped
Program Version=4.10
Use Restart= 0
Initial Flow Loc=Churchill River ,Main            ,41243.44,1508
Boundary Location=Churchill River ,Main            ,41243.44,        ,                ,                ,
Interval=1HOUR
Flow Hydrograph= 744
    1508    1507    1507    1507    1507    1508    1507    1507    1507    1507
    1508    1508    1429    1429    1429    1429    1429    1429    1429    1429
    1429    1429    1430    1430    1430    1430    1430    1430    1430    1430
    1430    1431    1431    1431    1431    1431    1432    1432    1432    1432
    1432    1432    1403    1402    1403    1403    1402    1403    1403    1402
    1402    1402    1402    1402    1402    1402    1402    1402    1402    1341
    1341    1341    1342    1342    1342    1341    1342    1342    1341    1341
    1341    1341    1341    1341    1341    1341    1341    1341    1341    1340
    1340    1340    1340    1340    1309    1310    1310    1310    1310    1310
    1310    1311    1311    1311    1311    1311    1311    1311    1311    1312
    1312    1312    1312    1312    1312    1312    1312    1313    1403    1403
    1403    1403    1403    1403    1403    1403    1403    1402    1402    1402
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Use DSS=False
CWMS InputPosition= 0
Use Fixed Start Time=False
Is Critical Boundary=False
Boundary Location=Churchill River ,Main            ,32.94778,        ,                ,                ,
Interval=1HOUR
Stage Hydrograph= 744
   -.122    -.19   -.241   -.269   -.283   -.265   -.221   -.139   -.059    -.03
   -.048   -.096    -.16   -.203   -.234    -.26   -.252   -.227    -.15   -.039
    .061    .119    .121    .075   -.004    -.08   -.148   -.191   -.207   -.174
    -.09    .021    .135    .209     .24    .223    .154    .074    .005   -.059
   -.105   -.118   -.078    .013    .113    .199    .222    .199    .138    .056
   -.034   -.106   -.175   -.214   -.209   -.135   -.017    .087    .157    .153
    .111    .034   -.048   -.126   -.192   -.239   -.241   -.175   -.064    .051
    .121    .133    .088    .011    -.08   -.165   -.238   -.294   -.306   -.256
    -.15   -.019    .087    .131    .112    .048   -.036   -.122   -.188   -.238
   -.263   -.226   -.125    .002    .125    .189    .173    .098   -.003   -.099
    -.19   -.262    -.31   -.303    -.23   -.107    .018     .09    .112    .072
   -.003   -.092   -.186   -.256    -.31   -.323   -.273    -.18   -.069    .036
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Use DSS=False
CWMS InputPosition= 0
Use Fixed Start Time=False
Is Critical Boundary=False

--- Churchill_Forecasting.g11 (geometry) ---

Geom Title=Current Conditions - Nalcor LiDAR
Program Version=4.10

River Reach=Churchill River ,Main
Reach XY= 30
      352746.205    5901870.9107     353004.0902    5901707.0009
     353420.8098     5901636.357     354472.7952     5901825.799
     355239.9892    5901821.6318     357565.9195    5900965.5575
     358197.8339    5900887.5714     358908.5981    5900946.8374
      360910.702    5901525.1009     363043.2479    5902699.8532
     364704.8346    5903358.6671     369682.2204    5904067.5335
     372857.1925    5904020.3913     373484.7877    5904254.4113
     374575.1212    5904881.1223     375539.3177    5905057.0816
     378839.9485    5904966.4881     381332.8312    5905136.4065
     382895.9556    5905538.7512     384737.2631    5906351.3853
     387170.5262    5907167.2208     390033.3236    5908479.5568
     391083.8457     5909065.741     391766.4875    5909590.2807
      392425.707     5910559.566     392814.3388    5911398.6122
     392684.1423    5912543.1765     393062.4973    5913758.3882
393159.3760869765914668.27501536403154.9861609515921290.41406772

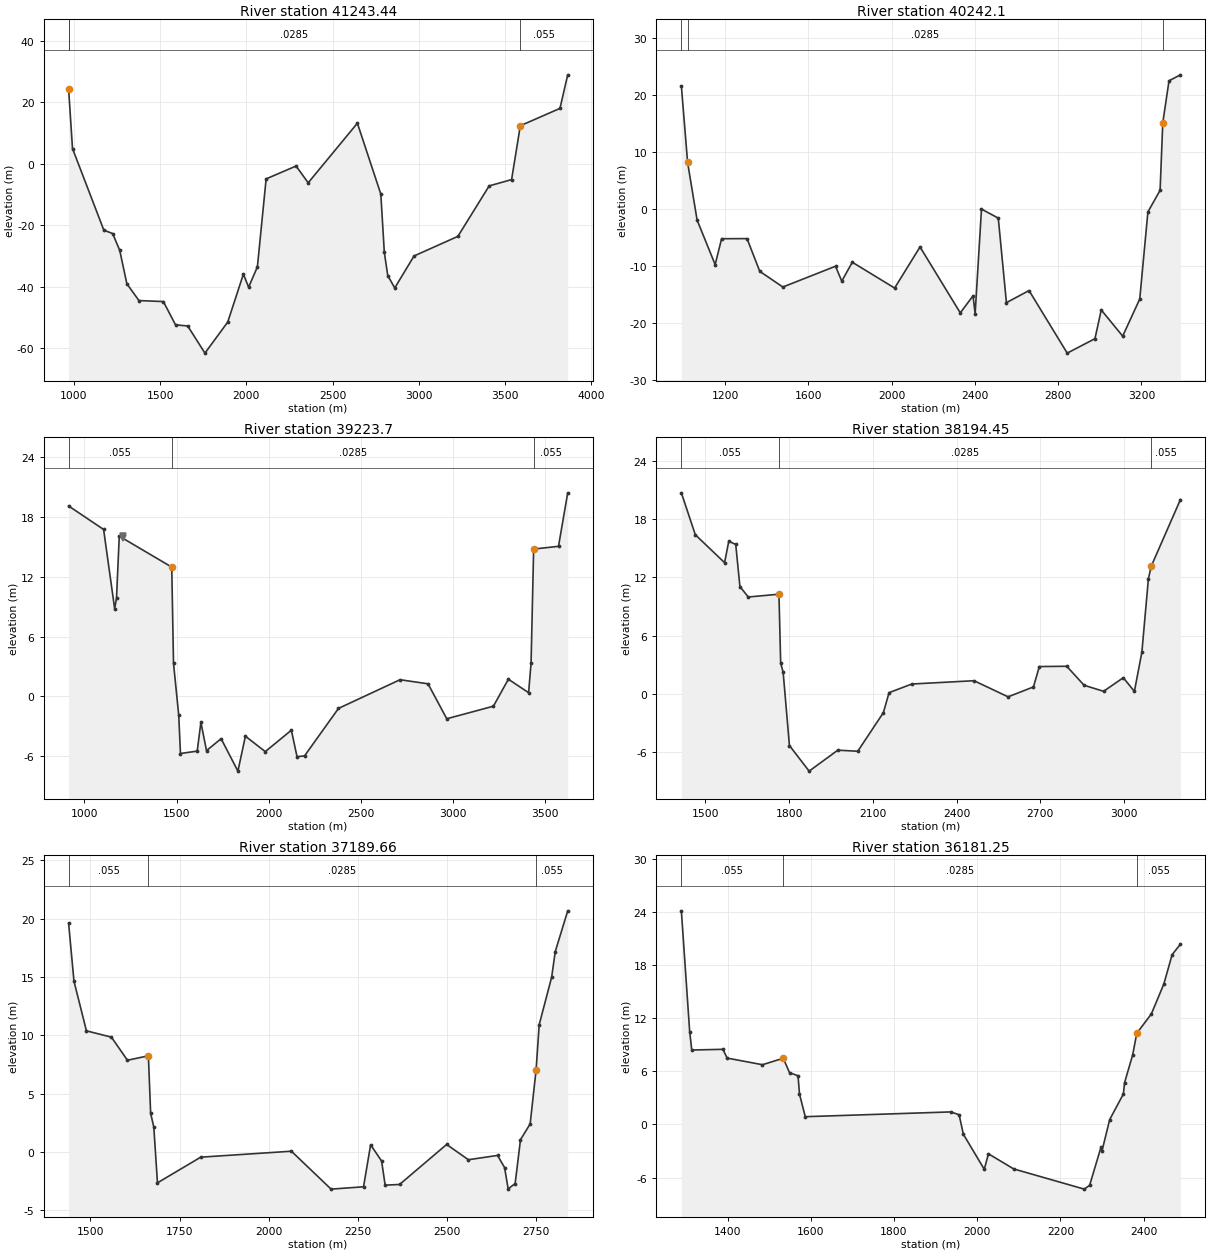
Type RM Length L Ch R = 1 ,41243.44,1199.65,1001.34,790.16
XS GIS Cut Line= 2
355538.233438958 5903210.9299795355305.4634303595900327.36277047
#Sta/Elev= 30
  969.32   24.28  991.86    4.99 1173.44  -21.58 1224.59  -22.69 1265.67  -28.19
 1306.91  -39.04 1376.88  -44.51 1518.59  -44.84  1589.1  -52.43 1659.56  -52.78
 1759.43  -61.63 1891.64  -51.51 1982.31  -35.92 2012.73  -40.16 2063.54  -33.53
 2114.18   -4.89  2287.7     -.7 2357.95   -6.16 2643.14   13.25 2778.97   -9.84
 2799.18  -28.77 2819.15  -36.36 2859.64  -40.41  2971.5  -29.99 3225.62  -23.61
 3407.01   -7.17 3536.99   -5.12 3587.48   12.42 3817.32   18.07 3862.29      29
#Mann= 3 , 0 , 0
  969.32    .055       0  969.32   .0285       0 3587.48    .055       0
Bank Sta=969.32,3587.48
XS Rating Curve= 0 ,0
Exp/Cntr(USF)=0.5,0.3
Exp/Cntr=0.3,0.1

Type RM Length L Ch R = 1 ,40242.1 ,968.29,1018.41,1034.79
XS GIS Cut Line= 2
356624.7898328565902924.55098587356206.4365599485900563.29083495
#Sta/Elev= 30
  989.19   21.57 1019.17    8.17 1064.79   -1.92 1151.59   -9.73 1182.43   -5.19
 1304.68   -5.17 1365.85   -10.9 1476.86  -13.65 1729.91  -10.01 1759.88  -12.62
 1810.56   -9.31 2013.92  -13.83 2135.87   -6.63 2329.32  -18.18 2390.49   -15.2
 2400.71  -18.32 2431.23       0 2511.85   -1.58 2551.03  -16.39 2659.73  -14.27
 2843.13  -25.23 2976.34   -22.7 3006.69  -17.67 3109.61  -22.25 3191.64  -15.75
 3230.76     -.5 3289.36    3.29  3302.3   15.12 3332.28   22.48 3387.23   23.52
#Mann= 3 , 0 , 0
  989.19    .055       0 1019.17   .0285       0  3302.3    .055       0
Bank Sta=1019.17,3302.3
XS Rating Curve= 0 ,0
Exp/Cntr(USF)=0.5,0.3
Exp/Cntr=0.3,0.1

Type RM Length L Ch R = 1 ,39223.7 ,827.11,1029.24,1183.39
XS GIS Cut Line= 2
357556.8319231745902704.63078815357141.5808249635900028.53733652
#Sta/Elev= 30
  914.37   19.11 1104.24   16.75 1164.19    8.79 1174.19    9.85 1189.18   16.08
 1473.98   12.97  1483.5     3.3 1511.85   -1.91 1521.24   -5.75 1612.08   -5.51
 1632.11   -2.62 1662.61   -5.46 1741.73   -4.26 1832.97   -7.52 1873.58   -4.01
  1981.4   -5.56 2123.01   -3.41 2153.71   -6.07 2194.44   -5.99 2378.74   -1.22
 2712.49    1.66 2864.45    1.25 2966.16   -2.26 3219.26      -1 3300.44    1.71
 3410.28     .36 3423.63    3.34 3437.62   14.78 3572.53   15.06 3622.49   20.43
#Mann= 3 , 0 , 0
  914.37    .055       0 1473.98   .0285       0 3437.62    .055       0
Levee=-1,1207.22,16.05,0,,,Levee 1,
Bank Sta=1473.98,3437.62
XS Rating Curve= 0 ,0
Exp/Cntr(USF)=0.5,0.3
Exp/Cntr=0.3,0.1

Type RM Length L Ch R = 1 ,38194.45,590.64,1004.79,1303.96
XS GIS Cut Line= 2
358363.9767182535901896.23911991358268.1821198525900110.37796295
#Sta/Elev= 30
 1413.75   20.71 1463.71   16.39 1568.62   13.51  1583.6   15.72 1608.58   15.39
 1623.57   11.05 1653.54    9.97 1763.45   10.26 1769.64    3.14 1778.41    2.24
 1800.95   -5.34 1871.59   -7.98 1974.36   -5.82 2045.81   -5.93 2137.63   -1.95
 2157.97     .11 2239.49       1 2462.37    1.34 2584.52    -.32 2675.39      .7
 2696.49     2.8 2794.67    2.83 2856.96     .87 2926.72     .25 2997.33    1.65
 3037.14     .24 3063.97    4.29 3087.28   11.85 3097.27   13.13 3202.18   20.02
#Mann= 3 , 0 , 0
 1413.75    .055       0 1763.45   .0285       0 3097.27    .055       0
Bank Sta=1763.45,3097.27
XS Rating Curve= 0 ,0
Exp/Cntr(USF)=0.5,0.3
Exp/Cntr=0.3,0.1

Type RM Length L Ch R = 1 ,37189.66,843.23,1008.41,1150.62
XS GIS Cut Line= 2
359179.4351656125901755.21912747359414.2732619825900375.98532351
#Sta/Elev= 30
 1439.07    19.6 1454.06   14.65 1489.04   10.39 1558.99    9.85 1603.96    7.87
 1662.67    8.25 1669.03    3.31 1677.84    2.15 1688.12   -2.64 1809.45    -.44
 2063.59     .07 2174.82   -3.18 2265.79   -2.98 2285.66     .62  2316.4    -.77
 2326.42   -2.84 2366.79   -2.78 2498.76     .65 2559.72    -.66 2641.36    -.29
 2661.18   -1.33 2671.24   -3.16 2690.79    -2.7 2705.79    1.06 2732.86    2.41
 2749.49    7.03 2758.21   10.92 2793.19      15 2803.18   17.18 2838.16   20.68
#Mann= 3 , 0 , 0
 1439.07    .055       0 1662.67   .0285       0 2749.49    .055       0
Bank Sta=1662.67,2749.49
XS Rating Curve= 0 ,0
Exp/Cntr(USF)=0.5,0.3
Exp/Cntr=0.3,0.1

Type RM Length L Ch R = 1 ,36181.25,885.13,1008.13,1123.83
XS GIS Cut Line= 2
360103.9275810965901889.68710072360433.6810565735900736.72489928
#Sta/Elev= 30
 1289.13   24.12 1309.11   10.47 1314.11     8.4 1389.06    8.48 1399.05    7.49
 1483.99    6.74 1533.96    7.47 1548.95    5.85 1569.47    5.49 1572.96    3.42
 1586.82     .87 1936.57    1.41 1956.49    1.09 1966.64   -1.11 2016.94   -5.07
 2026.95   -3.32 2087.67   -5.03 2257.19   -7.31 2270.07   -6.88 2297.74   -2.52
 2299.91   -2.97  2318.3     .55 2351.23    3.44 2354.06    4.72 2373.39    7.83
 2383.39   10.29 2418.36   12.47 2448.34   15.85 2468.33   19.17 2488.31   20.36
#Mann= 3 , 0 , 0
 1289.13    .055       0 1533.96   .0285       0 2383.39    .055       0
Bank Sta=1533.96,2383.39
XS Rating Curve= 0 ,0
Exp/Cntr(USF)=0.5,0.3
Exp/Cntr=0.3,0.1

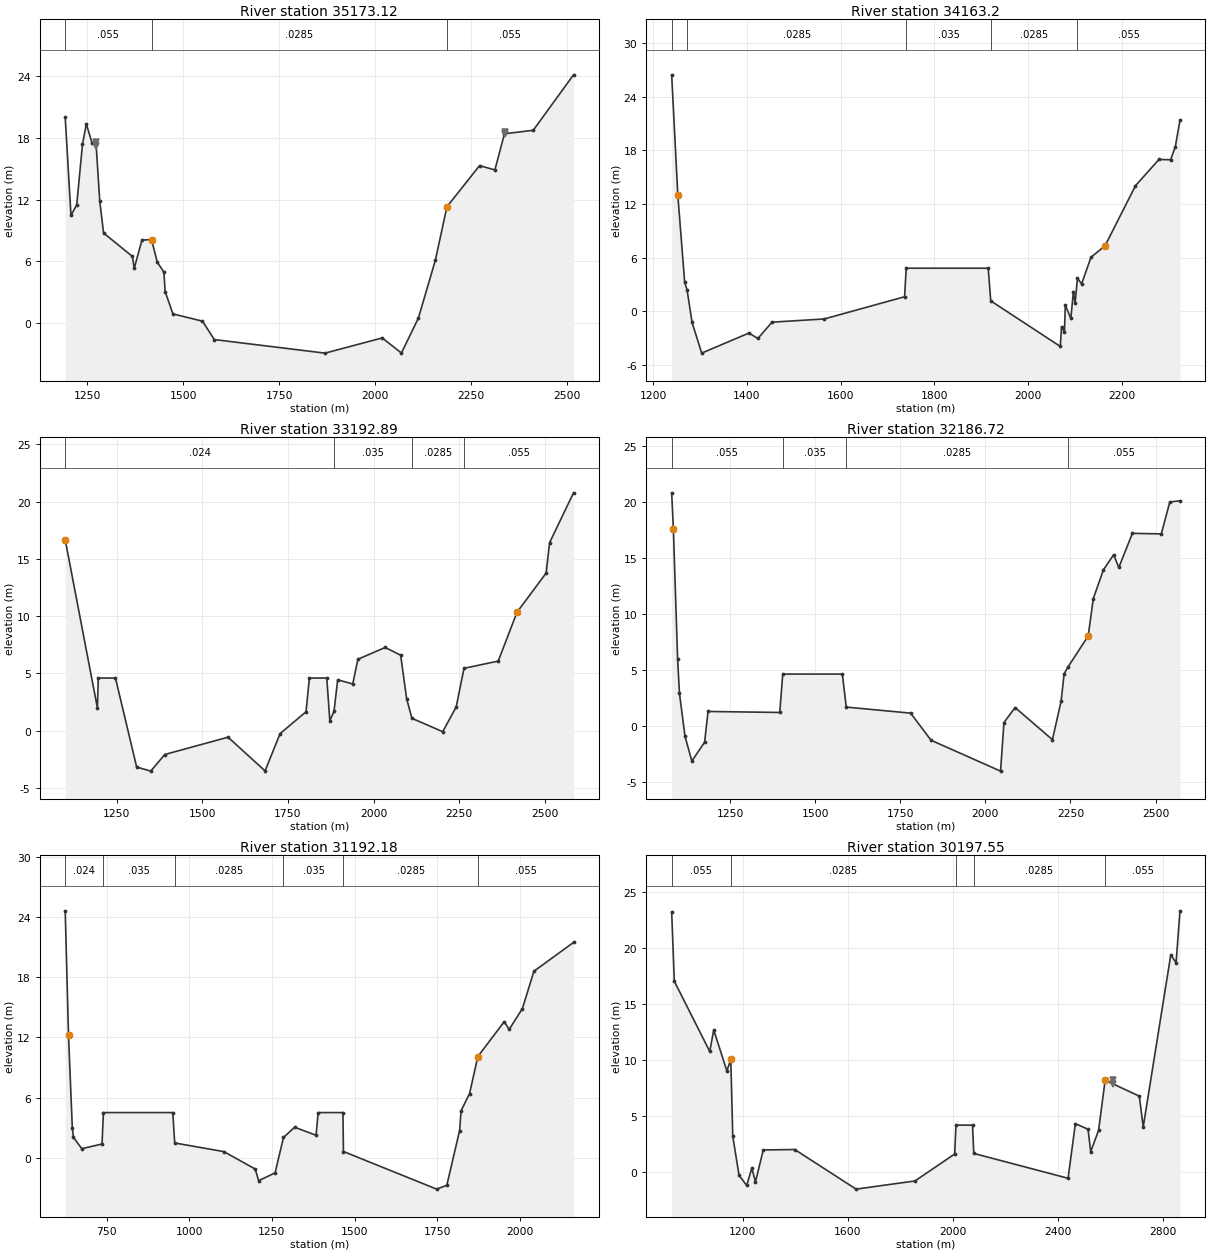
Type RM Length L Ch R = 1 ,35173.12,734.97,1009.92,1301.42
XS GIS Cut Line= 2
360995.0328001215902233.47744978361462.0506267375900995.49208828
#Sta/Elev= 30
 1193.34   20.02 1208.32   10.47  1223.3   11.48 1238.28   17.37 1248.27   19.36
 1263.24   17.51 1273.23   17.69 1283.22   11.87  1293.2    8.75  1368.1    6.47
 1373.09    5.32 1393.06    8.05 1418.03    8.11 1433.01    5.91 1450.19    4.94
 1453.47    3.05 1473.72     .87 1550.69     .16 1581.39   -1.63 1869.74   -2.95
 2018.55   -1.47 2068.51   -2.94 2112.78     .47    2157    6.12 2186.96    11.3
 2271.85   15.31 2311.79   14.89 2336.76   18.41 2411.65   18.75 2516.51   24.15
#Mann= 3 , 0 , 0
 1193.34    .055       0 1418.03   .0285       0 2186.96    .055       0
Levee=-1,1274.11,17.58,-1,2339.14,18.55,Levee 2,Levee 3
Bank Sta=1418.03,2186.96
XS Rating Curve= 0 ,0
Exp/Cntr(USF)=0.5,0.3
Exp/Cntr=0.3,0.1

Type RM Length L Ch R = 1 ,34163.2 ,971.99,970.31,998.23
XS GIS Cut Line= 2
361840.6306077325902567.25777953362409.2559906375901643.65944352
#Sta/Elev= 30
 1239.56   26.48 1252.61   13.03 1267.31    3.21 1272.39    2.38  1283.1   -1.28
 1303.62   -4.72 1404.38   -2.47 1423.55   -3.08  1453.6   -1.25    1565    -.89
 1736.52     1.6    1740     4.8    1915     4.8 1920.35    1.14 2068.78   -3.97
  2071.5   -1.75 2077.66   -2.36 2079.42     .65 2091.27    -.83 2096.72    2.18
 2100.31     .86 2105.39    3.67 2114.25    3.04 2134.25    6.03 2164.23    7.31
 2229.21   14.05  2279.2   16.99 2304.19   16.96 2314.18   18.42 2324.18   21.42
#Mann= 5 ,-1 , 0
 1239.56    .055       0 1272.39   .0285       0    1740    .035       0
 1920.35   .0285       0 2105.39    .055       0
Bank Sta=1252.61,2164.23
XS Rating Curve= 0 ,0
Exp/Cntr(USF)=0.5,0.3
Exp/Cntr=0.3,0.1

Type RM Length L Ch R = 1 ,33192.89,1234.76,1006.17,727.63
XS GIS Cut Line= 2
362630.6979425485903133.15579225363408.9064251195901869.13893486
#Sta/Elev= 30
 1099.53   16.66 1193.52       2 1196.11     4.6 1246.29     4.6 1308.13   -3.16
  1349.2   -3.52 1390.19   -2.07 1575.04    -.56 1683.15    -3.5 1726.98    -.25
 1802.73    1.66 1812.54     4.6 1863.37     4.6 1872.25     .88 1884.47    1.69
 1895.18    4.45 1939.17    4.08 1954.16    6.24 2034.12    7.27  2079.1    6.59
 2096.62    2.79 2111.88    1.09 2201.93    -.08 2241.36    2.09 2264.03    5.45
 2363.98    6.08 2418.96   10.35 2503.92   13.76 2513.92   16.41 2583.89   20.76
#Mann= 4 ,-1 , 0
 1099.53    .024       0 1884.47    .035       0 2111.88   .0285       0
 2264.03    .055       0
Bank Sta=1099.53,2418.96
XS Rating Curve= 0 ,0
Exp/Cntr(USF)=0.5,0.3
Exp/Cntr=0.3,0.1

Type RM Length L Ch R = 1 ,32186.72,1219.67,994.54,671.77
XS GIS Cut Line= 2
 363631.709871595903578.71580343364207.1422299995902200.81437446
#Sta/Elev= 30
 1078.71   20.79 1083.71   17.56 1096.16    5.94 1101.62    2.87 1117.85    -.96
 1137.88   -3.17 1175.41   -1.49 1185.54    1.26 1396.22    1.17    1405     4.6
    1580     4.6 1591.57    1.65 1780.72    1.11  1840.6   -1.31 2044.77   -4.07
  2054.8     .27 2087.54    1.61 2197.18   -1.26 2222.78    2.19 2231.52    4.62
 2242.33    5.21 2302.25       8 2317.24   11.34  2347.2   13.93 2377.17   15.26
 2392.15   14.12  2432.1   17.17    2517   17.12 2541.97   19.97 2571.93   20.08
#Mann= 4 ,-1 , 0
 1078.71    .055       0    1405    .035       0 1591.57   .0285       0
 2242.33    .055       0
Bank Sta=1083.71,2302.25
XS Rating Curve= 0 ,0
Exp/Cntr(USF)=0.5,0.3
Exp/Cntr=0.3,0.1

Type RM Length L Ch R = 1 ,31192.18,1034.11,994.63,993.08
XS GIS Cut Line= 2
364659.094328575 5903964.7554875364993.4189005785902463.03305586
#Sta/Elev= 30
  624.39   24.61  634.38    12.2  645.88    2.99   649.4    2.03  674.61      .9
  735.88    1.37     740     4.5     950     4.5  955.84    1.47 1104.56     .61
 1199.53   -1.13 1209.85   -2.29  1259.6   -1.51 1285.02    2.02 1318.71    3.04
 1383.65    2.24    1390     4.5    1465     4.5 1466.49     .62 1748.66   -3.13
 1779.35   -2.75  1818.1    2.71 1822.53    4.68 1848.19    6.39 1873.17   10.08
 1953.09   13.56 1968.08   12.79 2008.04   14.86    2043   18.59 2162.88   21.46
#Mann= 6 ,-1 , 0
  624.39    .024       0     740    .035       0  955.84   .0285       0
 1285.02    .035       0 1466.49   .0285       0 1873.17    .055       0
Bank Sta=634.38,1873.17
XS Rating Curve= 0 ,0
Exp/Cntr(USF)=0.5,0.3
Exp/Cntr=0.3,0.1

Type RM Length L Ch R = 1 ,30197.55,1025.02,1021.21,1018.34
XS GIS Cut Line= 2
 365584.825019185904376.40324965366005.2681428385902487.85265764
#Sta/Elev= 30
  929.89   23.25  939.89   17.06 1074.88   10.78 1089.88   12.71 1139.87    9.05
 1154.87   10.07 1162.47     3.2 1186.24    -.28 1215.43   -1.19 1235.04     .36
 1248.87    -.87 1278.44    1.98 1398.24    2.02 1631.86   -1.52 1855.94    -.79
 2007.11    1.62    2012     4.2    2075     4.2 2079.76    1.67 2438.66    -.55
 2466.46    4.33 2514.71    3.83 2524.71    1.83 2554.71    3.72  2579.7    8.21
 2709.69    6.79 2724.69    4.04 2829.68   19.43 2849.67   18.71 2864.67   23.35
#Mann= 5 ,-1 , 0
  929.89    .055       0 1154.87   .0285       0    2012    .035       0
 2079.76   .0285       0  2579.7    .055       0
Levee=-1,920.97,25.37,-1,2611.08,8.23,Levee 4,Levee 5
Bank Sta=1154.87,2579.7
XS Rating Curve= 0 ,0
Exp/Cntr(USF)=0.5,0.3
Exp/Cntr=0.3,0.1

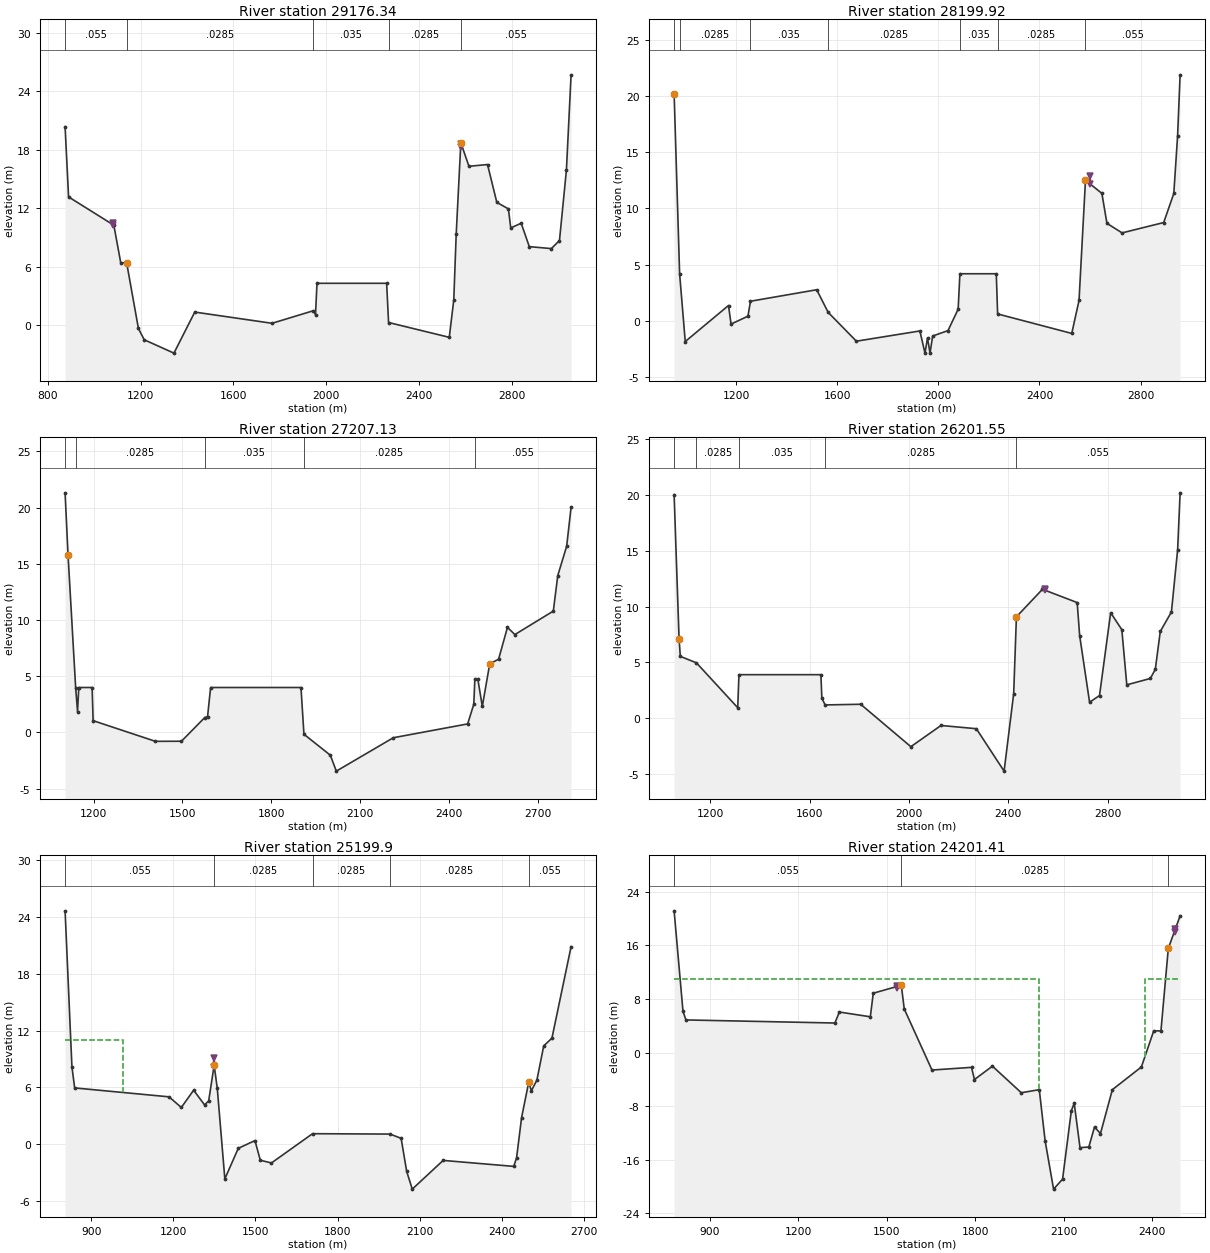
Type RM Length L Ch R = 1 ,29176.34,1138.34,976.42,790.73
XS GIS Cut Line= 2
366575.0504711595904614.59656991367048.7107041215902487.00490546
#Sta/Elev= 30
  874.87   20.36  889.87   13.16 1084.84   10.26 1114.84    6.38 1139.83    6.43
 1190.71    -.33 1215.73   -1.49 1343.76   -2.86 1433.44    1.35 1766.38      .2
 1944.53    1.49 1953.58    1.09    1960     4.3    2260     4.3 2268.33     .28
 2529.83   -1.24 2549.24     2.6 2559.62    9.31 2579.62   18.71 2614.62    16.3
  2694.6   16.48  2734.6    12.6 2784.59   11.93 2794.59    9.98 2839.58   10.46
 2874.58    8.06 2969.56    7.86 3004.56    8.69 3034.56   15.95 3054.55   25.68
#Mann= 5 ,-1 , 0
  874.87    .055       0 1139.83   .0285       0 1944.53    .035       0
 2268.33   .0285       0 2579.62    .055       0
Levee=-1,1080.27,10.49,-1,2581.21,18.28,Levee 4,Levee 5
Bank Sta=1139.83,2579.62
XS Rating Curve= 0 ,0
Exp/Cntr(USF)=0.5,0.3
Exp/Cntr=0.3,0.1

Type RM Length L Ch R = 1 ,28199.92,995.41,992.79,993.66
XS GIS Cut Line= 2
367655.3898128915904687.76428615367869.613936821  5902696.538264
#Sta/Elev= 30
   953.9    20.2  975.63     4.2  997.91   -1.82 1169.13    1.38 1179.25    -.27
 1246.03     .43 1256.19    1.76 1518.25    2.78 1563.64     .77 1675.29   -1.79
 1926.58    -.88 1946.78   -2.85 1956.78    -1.5 1966.78   -2.85 1977.19   -1.33
 2037.83    -.85 2078.12    1.05    2085     4.2    2229     4.2 2234.28     .63
 2527.66    -1.1 2556.52    1.83 2582.03   12.51 2646.95   11.34 2666.93    8.68
 2726.86    7.83 2891.66    8.75 2931.62   11.33  2946.6   16.44 2956.59   21.87
#Mann= 7 ,-1 , 0
   953.9    .055       0  975.63   .0285       0 1256.19    .035       0
 1563.64   .0285       0    2085    .035       0 2234.28   .0285       0
 2582.03    .055       0
Levee=0,,,-1,2598.63,12.92,,Levee 5
Bank Sta=953.9,2582.03
XS Rating Curve= 0 ,0
Exp/Cntr(USF)=0.5,0.3
Exp/Cntr=0.3,0.1

Type RM Length L Ch R = 1 ,27207.13,1086.67,1005.59,915.85
XS GIS Cut Line= 2
 368658.787946125904640.07015667368841.4941561275902941.80450296
#Sta/Elev= 30
 1103.75   21.32 1113.74   15.77 1139.49    3.95 1145.74    1.86    1150       4
    1195       4 1198.36    1.05 1408.78    -.79  1496.6    -.78 1575.28    1.33
  1584.6    1.39    1595       4    1900       4 1910.04    -.16 1999.01   -2.02
 2019.36   -3.44  2211.6    -.47 2462.69     .76  2483.4    2.51 2486.99    4.74
 2497.17    4.72 2512.16    2.32 2537.13     6.1  2567.1    6.52 2597.06    9.35
 2622.03    8.71 2751.89    10.8 2766.87   13.96 2796.84   16.56 2811.82   20.02
#Mann= 5 ,-1 , 0
 1103.75    .055       0 1139.49   .0285       0 1575.28    .035       0
 1910.04   .0285       0 2486.99    .055       0
Bank Sta=1113.74,2537.13
XS Rating Curve= 0 ,0
Exp/Cntr(USF)=0.5,0.3
Exp/Cntr=0.3,0.1

Type RM Length L Ch R = 1 ,26201.55,1068.28,1001.65,945.48
XS GIS Cut Line= 2
369693.6218208885904800.33809111369798.5638235755902765.25934895
#Sta/Elev= 30
 1053.86   20.02 1073.83    7.09 1078.83    5.54 1143.76    4.96    1310     .94
    1315     3.9    1645     3.9 1648.78     1.8 1662.12    1.19 1805.22    1.25
 2007.26   -2.55 2128.61    -.65 2271.01    -.94  2382.8   -4.74 2421.41    2.21
 2432.36    9.08 2537.25   11.55  2677.1   10.36 2687.08     7.4 2727.04    1.43
    2767    2.03 2811.95    9.45  2856.9    7.93 2876.88    2.99 2971.78    3.56
 2991.76    4.38 3011.74    7.77 3056.69    9.52 3081.66    15.1 3091.65   20.19
#Mann= 5 ,-1 , 0
 1053.86    .055       0 1143.76   .0285       0    1315    .035       0
 1662.12   .0285       0 2432.36    .055       0
Levee=0,,,-1,2548.85,11.54,,Levee 6
Bank Sta=1073.83,2432.36
XS Rating Curve= 0 ,0
Exp/Cntr(USF)=0.5,0.3
Exp/Cntr=0.3,0.1

Type RM Length L Ch R = 1 ,25199.9 ,1065.31,998.49,975.09
XS GIS Cut Line= 2
370718.7755874455905151.77759483370740.4105410685903303.20609274
#Sta/Elev= 30
  804.43   24.63  829.41    8.17   839.4    5.94 1184.16       5 1229.12    3.88
 1274.09     5.7 1314.06    4.15 1329.05    4.57 1349.04    8.34 1360.51    5.88
 1388.08   -3.66 1437.24    -.43 1498.09     .38 1517.74   -1.69 1558.29   -1.98
 1708.49    1.11 1991.75    1.07 2032.18     .62 2052.44   -2.87 2072.87   -4.74
 2185.69   -1.71 2443.79   -2.34 2454.04   -1.42 2472.27    2.81 2498.22    6.52
 2508.21    5.64  2528.2    6.77 2553.18   10.38 2583.16   11.19 2653.11   20.85
#Mann= 5 ,-1 , 0
  804.43    .055       0 1349.04   .0285       0 1708.49   .0285       0
 1991.75   .0285       0 2498.22    .055       0
Levee=-1,1347.83,9.11,0,,,Levee 7,
#XS Ineff= 2 , 0
       0  1016.5      11               0
Permanent Ineff=
       F       F
Bank Sta=1349.04,2498.22
XS Rating Curve= 0 ,0
Exp/Cntr(USF)=0.5,0.3
Exp/Cntr=0.3,0.1

Type RM Length L Ch R = 1 ,24201.41,139.37,137.37,138.3
XS GIS Cut Line= 2
371755.4124039625905315.34396905371721.1203393415903600.74243302
#Sta/Elev= 30
  779.98   21.17  809.97    6.19  819.97    4.88 1324.96    4.42 1339.96    6.06
 1444.95    5.35 1454.95    8.87 1549.95   10.06 1559.95    6.52 1653.94    -2.6
  1787.9    -2.2  1797.9   -4.02  1858.7   -2.02 1956.68   -5.99 2017.59   -5.53
 2037.37  -13.16 2066.03  -20.38 2096.55  -18.89 2126.27   -8.67 2136.02   -7.56
 2155.63  -14.19 2185.55  -14.09 2204.82   -11.1 2224.98  -12.08 2265.34   -5.53
 2363.69   -2.14 2405.55    3.26 2429.92    3.24 2454.92   15.56 2494.92   20.43
#Mann= 3 , 0 , 0
  779.98    .055       0 1549.95   .0285       0 2454.92    .055       0
Levee=-1,1535.47,9.67,-1,2478.53,18.01,Levee 7,Levee 8
#XS Ineff= 2 , 0
       0    2015      11    2375       0      11
Permanent Ineff=
       F       F
Bank Sta=1549.95,2454.92
XS Rating Curve= 0 ,0
Exp/Cntr(USF)=0.5,0.3
Exp/Cntr=0.3,0.1

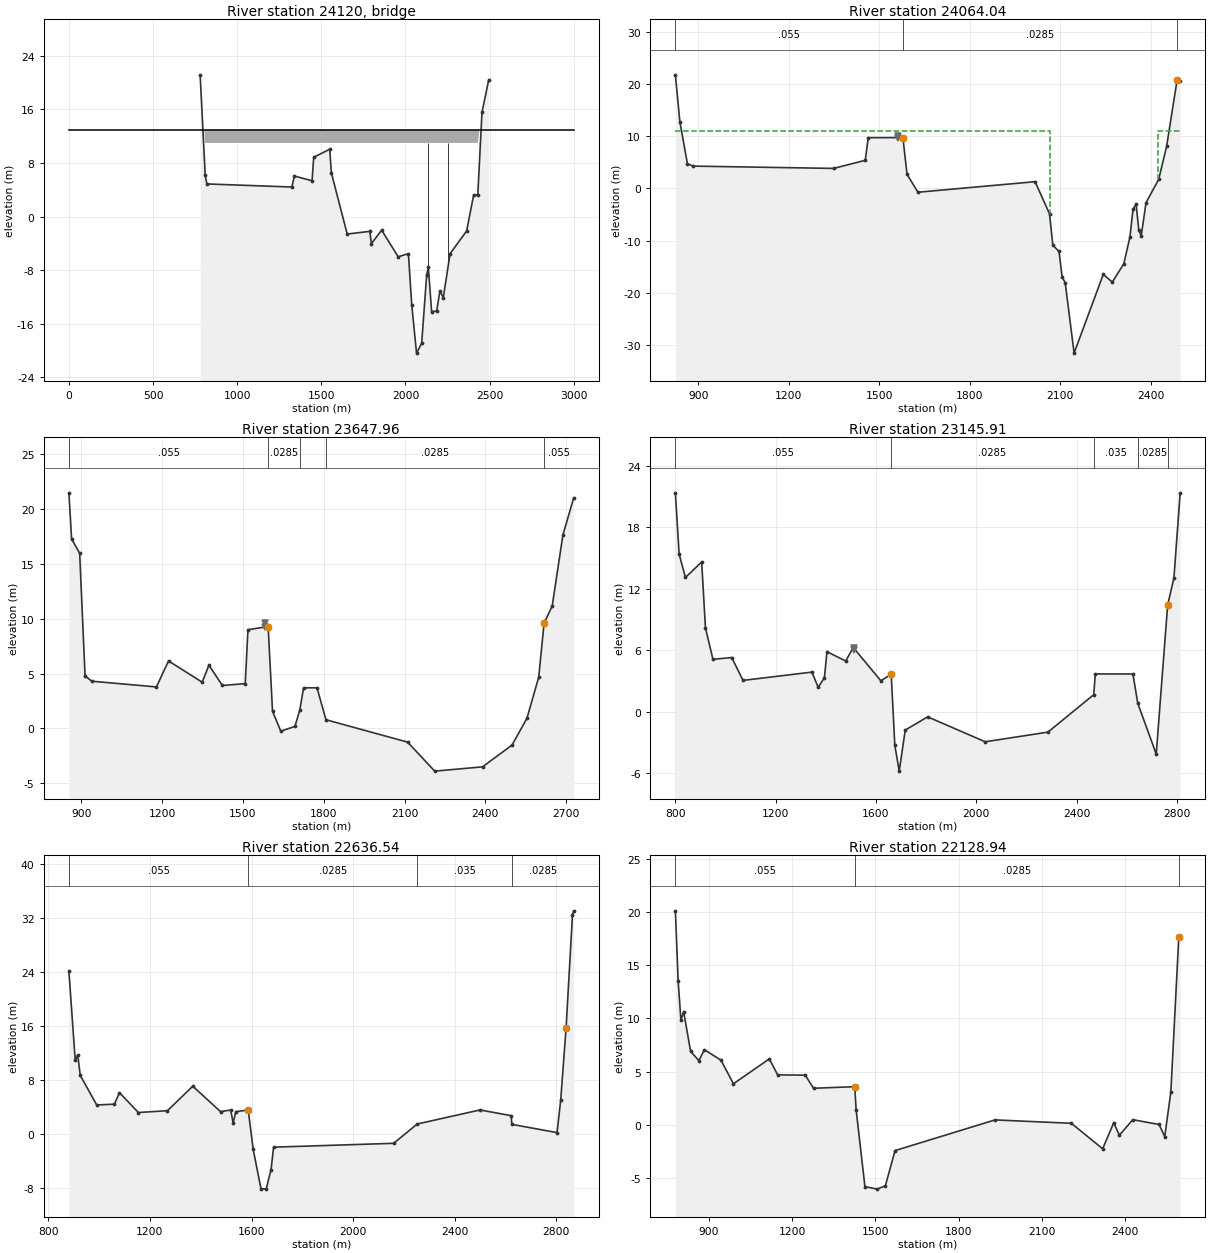
Type RM Length L Ch R = 3 ,24120   ,,,
Bridge Culvert--1,0,-1,-1, 0
Deck Dist Width WeirC Skew NumUp NumDn MinLoCord MaxHiCord MaxSubmerge Is_Ogee
60,20,1.4,0, 2, 2, , , 0.98, 0, 0,0,,
       0    3000
      13      13
      11      11
       0    3000
      13      13
      11      11
Pier Skew, UpSta & Num, DnSta & Num=  ,2135, 2 ,2185, 2 , 0 , 0 , 0 ,,
       1       1
   10.99   10.99
       1       1
   10.99   10.99
Pier Skew, UpSta & Num, DnSta & Num=  ,2255, 2 ,2305, 2 , 0 , 0 , 0 ,,
       1       1
   10.99   10.99
       1       1
   10.99   10.99
Abutment Skew #Up #Dn= , 2 , 2
       0    2015
      11      11
       0    2065
      11      11
Abutment Skew #Up #Dn= , 2 , 2
    2375    3000
      11      11
    2425    3000
      11      11
BR Coef=-1 , 0 , 0 ,, 0 ,,,0.8,-1,,0,
WSPro=,,,, 1 ,,,, 0 ,,,, 0 ,,,,-1 ,-1 ,-1 , 0 , 0 , 0 , 0 , 0
BC Design=,, 0 ,, 0 ,,,,,,
BC HTab HWMax=20
BC Use User HTab Curves=0
BC User HTab FreeFlow(D)= 0

Type RM Length L Ch R = 1 ,24064.04,382.78,416.08,439.98
XS GIS Cut Line= 2
371892.4654726395905298.67045102371859.012873567 5903626.0427694
#Sta/Elev= 30
     824   21.71  838.98   12.71  863.95    4.69  883.93    4.24 1348.36     3.8
 1453.23    5.35 1463.22    9.68 1578.08     9.7 1591.72    2.68 1627.89    -.76
 2016.08    1.26    2064   -4.89 2074.88   -10.9 2095.38  -12.09 2105.74  -16.97
  2115.9  -18.07 2145.42  -31.55 2242.07  -16.48    2272  -17.95 2310.14  -14.46
 2330.35   -9.37 2340.73   -4.01 2350.89   -3.02 2359.92   -8.04 2367.92   -9.09
 2383.75   -2.76 2425.77     1.7 2452.02    8.01 2486.98    20.8 2496.96   20.51
#Mann= 3 , 0 , 0
     824    .055       0 1578.08   .0285       0 2486.98    .055       0
Levee=-1,1561.61,10.08,0,,,Levee 7,
#XS Ineff= 2 , 0
       0    2065      11    2425       0      11
Permanent Ineff=
       F       F
Bank Sta=1578.08,2486.98
XS Rating Curve= 0 ,0
Exp/Cntr(USF)=0.5,0.3
Exp/Cntr=0.3,0.1

Type RM Length L Ch R = 1 ,23647.96,505.71,502.05,500
XS GIS Cut Line= 2
     372282.06125905313.54542197     372282.06125903440.10480742
#Sta/Elev= 30
  854.29   21.46  864.28   17.26  894.26   15.95  914.24    4.78  939.22     4.3
 1179.02    3.78 1223.98    6.15 1348.88    4.21 1373.86    5.76 1423.82    3.91
 1508.75    4.08 1518.74    8.99 1593.68    9.28 1609.95    1.57 1640.47    -.25
 1693.16     .18 1711.32     1.7 1725.24     3.7    1775     3.7 1808.29     .79
 2111.44   -1.25 2211.82   -3.89 2389.29    -3.5 2498.71   -1.52 2554.27     .93
 2597.84    4.67 2617.83    9.59  2647.8   11.14 2687.77   17.63 2727.73      21
#Mann= 5 ,-1 , 0
  854.29    .055       0 1593.68   .0285       0 1711.32    .035       0
 1808.29   .0285       0 2617.83    .055       0
Levee=-1,1580.58,9.6,0,,,Levee 7,
Bank Sta=1593.68,2617.83
XS Rating Curve= 0 ,0
Exp/Cntr(USF)=0.5,0.3
Exp/Cntr=0.3,0.1

Type RM Length L Ch R = 1 ,23145.91,131.3,509.36,874.95
XS GIS Cut Line= 2
     372782.06125905431.07412441     372782.06125903417.07729258
#Sta/Elev= 30
   799.6   21.35   814.6   15.39  839.59    13.1  904.55   14.61  919.55     8.2
  949.53    5.12 1024.49     5.3 1069.47    3.07 1344.34    3.88 1369.33     2.4
 1394.31    3.34 1404.31    5.87 1479.27    4.96 1509.26    6.28  1619.2    3.04
 1660.71    3.66 1675.14   -3.25 1692.71   -5.77 1716.64   -1.77 1806.09    -.48
 2035.59   -2.91 2285.98   -1.97 2468.83    1.68    2475     3.7    2625     3.7
 2644.58     .83 2718.07   -4.11 2763.64   10.41 2788.63   13.05 2813.61   21.34
#Mann= 5 ,-1 , 0
   799.6    .055       0 1660.71   .0285       0 2468.83    .035       0
 2644.58   .0285       0 2763.64    .055       0
Levee=-1,1510.89,6.06,0,,,Levee 7,
Bank Sta=1660.71,2763.64
XS Rating Curve= 0 ,0
Exp/Cntr(USF)=0.5,0.3
Exp/Cntr=0.3,0.1

Type RM Length L Ch R = 1 ,22636.54,243.38,507.6,678.94
XS GIS Cut Line= 4
372916.4242078555905376.27542926     372916.6397     5905346.413
     373087.2052     5904768.912373471.271045858 5903468.5408028
#Sta/Elev= 30
  880.88   24.09  905.77   10.93  915.72   11.74  925.67    8.69  990.37    4.34
 1060.04    4.45 1079.95    6.15  1154.6    3.22 1269.06    3.49 1368.59    7.11
 1478.07    3.35 1517.89    3.59 1527.86    1.66 1537.83    3.34 1586.97     3.6
 1606.58   -2.22 1637.13   -8.02 1657.57    -8.1 1676.97   -5.22 1686.98    -1.9
 2159.79   -1.33 2252.46    1.52    2500     3.6 2622.79    2.75 2625.08    1.47
 2803.23     .25 2817.65    5.09 2838.89   15.76 2863.82   32.34  2868.8   33.02
#Mann= 4 ,-1 , 0
  880.88    .055       0 1586.97   .0285       0 2252.46    .035       0
 2625.08   .0285       0
Bank Sta=1586.97,2838.89
XS Rating Curve= 0 ,0
Exp/Cntr(USF)=0.5,0.3
Exp/Cntr=0.3,0.1

Type RM Length L Ch R = 1 ,22128.94,396.14,507.49,502.51
XS GIS Cut Line= 3
373240.6307513125905529.90934562     373431.5829    5905075.4949
373945.2745325865903853.04771136
#Sta/Elev= 30
  778.94   20.09   788.9   13.52  798.86    9.84  808.82   10.62  833.71    6.91
  863.58    6.02   883.5    7.05  943.25    6.07  988.05    3.85  1117.5    6.19
 1147.38    4.69 1246.95    4.66 1276.83    3.43 1425.21    3.58 1430.28     1.4
 1461.91    -5.8 1505.84   -6.04 1535.65   -5.72 1570.49   -2.42  1930.8     .46
 2205.89     .14 2318.46   -2.25 2358.41     .19 2378.68    -.98 2427.21     .48
 2521.75     .03 2542.19   -1.11 2564.25    3.09 2592.85   17.62 2597.83   17.77
#Mann= 3 , 0 , 0
  778.94    .055       0 1425.21   .0285       0 2592.85    .055       0
Bank Sta=1425.21,2592.85
XS Rating Curve= 0 ,0
Exp/Cntr(USF)=0.5,0.3
Exp/Cntr=0.3,0.1