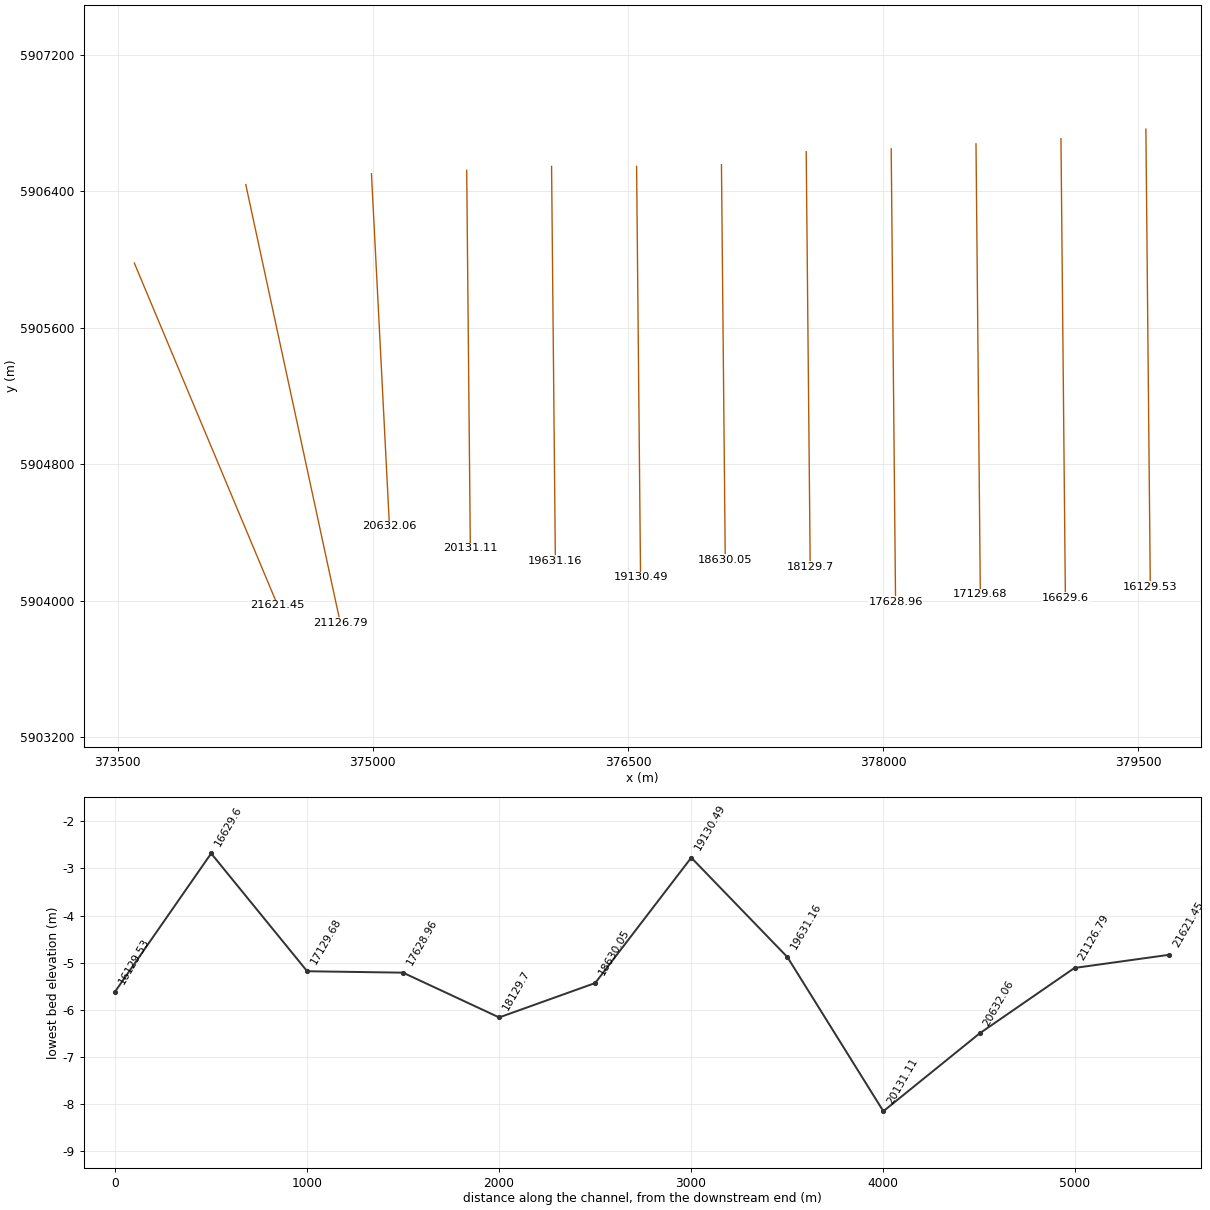
HEC-RAS study Churchill_Forecasting.prj: ChurchillRiver_Forecasting

--- Churchill_Forecasting.g11 (geometry) --- (continued)

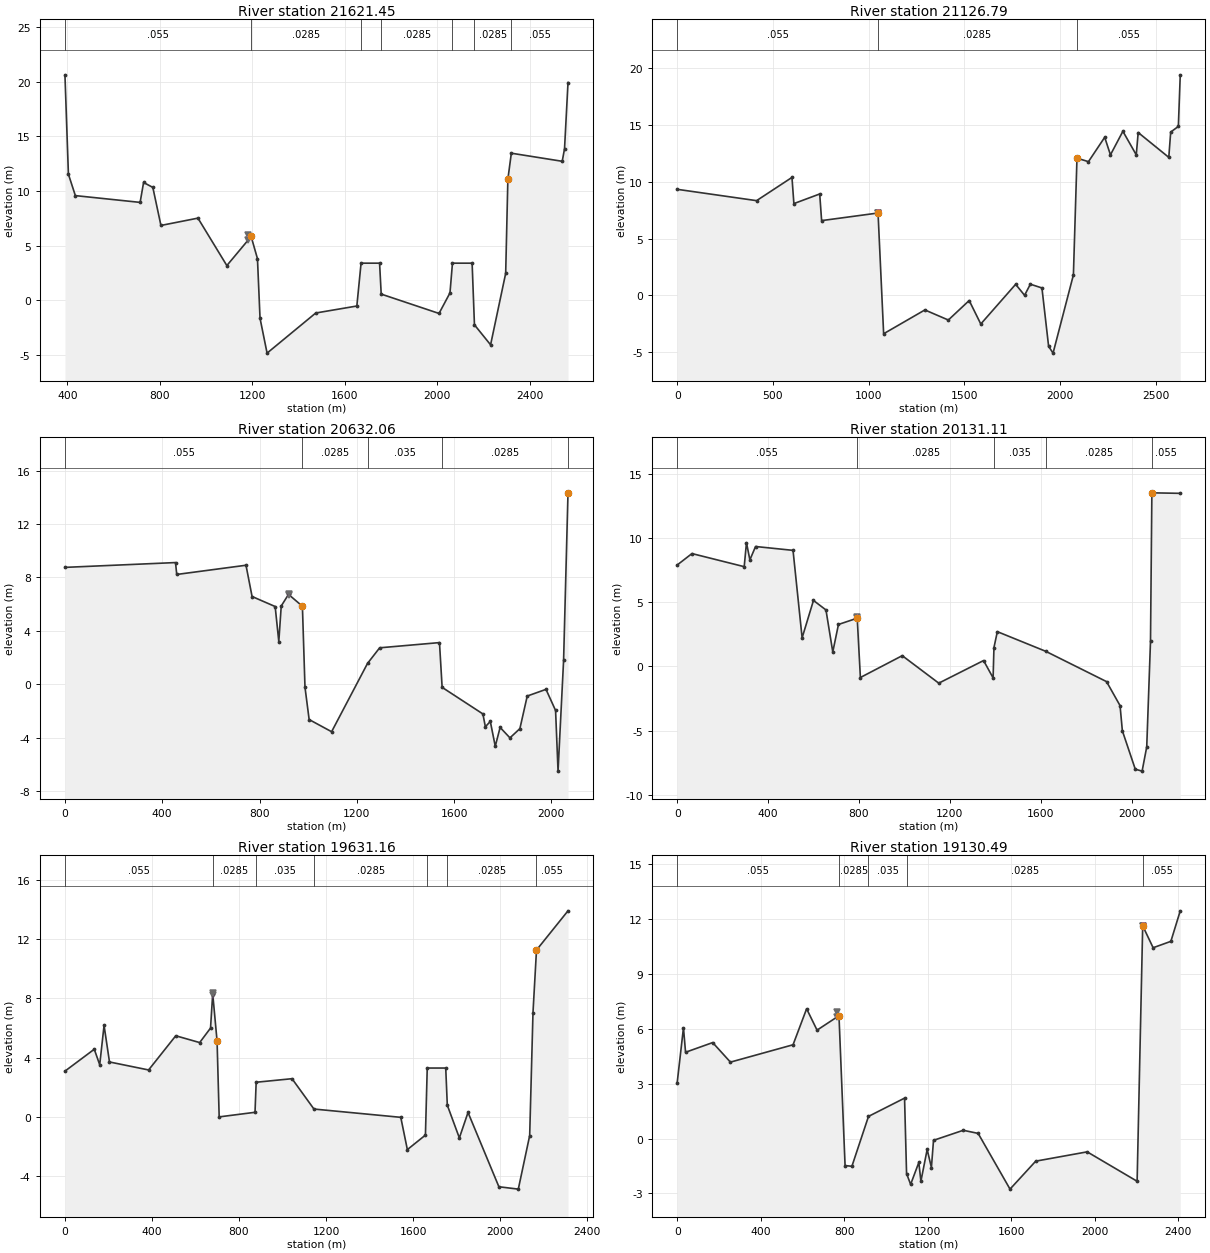
Type RM Length L Ch R = 1 ,21621.45,766.04,494.66,174.79
XS GIS Cut Line= 2
373596.8752581445905977.88533643374439.3020494875903973.13768515
#Sta/Elev= 30
  389.92   20.63  404.92   11.54  434.91    9.58  714.86    8.96  729.85   10.78
  769.85   10.33  804.84    6.85  964.81    7.52 1089.78    3.18 1194.76    5.84
 1222.12    3.81 1233.22   -1.64 1263.68   -4.83    1474   -1.16 1651.68    -.52
    1670     3.4    1750     3.4    1757     .57 2006.95    -1.2 2054.33     .68
    2065     3.4    2150     3.4 2160.08   -2.24 2229.83   -4.07 2295.08    2.47
 2304.54   11.08 2319.53   13.46 2539.49   12.72 2549.49   13.87 2564.48   19.92
#Mann= 7 ,-1 , 0
  389.92    .055       0 1194.76   .0285       0    1670    .035       0
    1757   .0285       0    2065    .035       0 2160.08   .0285       0
 2319.53    .055       0
Levee=-1,1182.33,6.02,0,,,Levee 9,
Bank Sta=1194.76,2304.54
XS Rating Curve= 0 ,0
Exp/Cntr(USF)=0.5,0.3
Exp/Cntr=0.3,0.1

Type RM Length L Ch R = 1 ,21126.79,703.23,494.73,214.27
XS GIS Cut Line= 2
     374252.2828    5906438.1996 374807.811066495903870.93978839
#Sta/Elev= 30
       0    9.34  414.48    8.34  599.24   10.39  609.23    8.08  744.06    8.93
  754.05    6.58 1048.67    7.25 1077.89    -3.4 1293.16    -1.3 1415.66   -2.19
 1524.56    -.47 1585.12   -2.54 1767.15     .96 1813.76    -.01 1843.93     .97
 1904.42     .64 1939.28   -4.51 1962.48   -5.11 2068.74    1.79 2087.36   12.09
 2147.28   11.78 2232.18   13.93 2262.14   12.38 2327.06   14.46 2396.97   12.38
 2406.95   14.35 2566.75   12.16 2576.74   14.39 2616.69   14.89 2626.67   19.44
#Mann= 3 , 0 , 0
       0    .055       0 1048.67   .0285       0 2087.36    .055       0
Levee=-1,1047.6,7.25,0,,,Levee 9,
Bank Sta=1048.67,2087.36
XS Rating Curve= 0 ,0
Exp/Cntr(USF)=0.5,0.3
Exp/Cntr=0.3,0.1

Type RM Length L Ch R = 1 ,20632.06,553.47,500.95,431.9
XS GIS Cut Line= 2
     374991.4999    5906501.4228 375097.32182344 5904435.6962342
#Sta/Elev= 30
       0    8.75  454.66    9.11  459.66    8.22  744.44    8.91  769.42    6.57
  864.35    5.82  879.34     3.2  889.33    5.86  919.31    6.73  976.39    5.84
  986.99    -.22 1004.09   -2.64 1096.46   -3.55 1244.07    1.56 1294.03    2.73
    1540    3.12  1550.9    -.23 1718.55   -2.22 1728.63   -3.18    1749   -2.78
 1769.37   -4.64 1789.32   -3.23 1829.76   -4.01 1870.57   -3.32 1900.85    -.88
 1977.94    -.38 2017.35   -1.96 2027.51    -6.5 2050.31    1.79 2068.45   14.33
#Mann= 5 ,-1 , 0
       0    .055       0  976.39   .0285       0 1244.07    .035       0
  1550.9   .0285       0 2068.45    .055       0
Levee=-1,921.28,6.75,0,,,Levee 9,
Bank Sta=976.39,2068.45
XS Rating Curve= 0 ,0
Exp/Cntr(USF)=0.5,0.3
Exp/Cntr=0.3,0.1

Type RM Length L Ch R = 1 ,20131.11,499.39,499.95,502.28
XS GIS Cut Line= 2
     375551.6424    5906521.4517375573.0191005335904307.35535739
#Sta/Elev= 30
       0     7.9   64.98    8.79  294.89    7.77  304.89    9.64  319.88     8.3
  344.87    9.34  509.81    9.04   549.8    2.23  599.78    5.14  654.76     4.4
  684.75    1.13  709.74    3.27  792.33    3.76  806.26    -.86  990.52     .84
 1151.27    -1.3 1348.47     .46 1390.41    -.89 1394.16    1.47 1409.06    2.71
 1622.04    1.18 1889.71   -1.18 1949.18   -3.05 1959.34   -5.01 2016.18      -8
 2046.25   -8.15 2066.62   -6.26 2083.22    1.97 2089.23   13.52 2214.18   13.48
#Mann= 5 ,-1 , 0
       0    .055       0  792.33   .0285       0 1394.16    .035       0
 1622.04   .0285       0 2089.23    .055       0
Levee=-1,789.71,3.85,0,,,Levee 9,
Bank Sta=792.33,2089.23
XS Rating Curve= 0 ,0
Exp/Cntr(USF)=0.5,0.3
Exp/Cntr=0.3,0.1

Type RM Length L Ch R = 1 ,19631.16,500,500.67,502.47
XS GIS Cut Line= 2
     376050.8276    5906544.7603 376073.147579075904232.96529177
#Sta/Elev= 30
       0    3.09  134.82    4.57  159.79    3.52  179.76    6.18  204.73    3.71
  384.49    3.17  509.32    5.48  619.17    5.02   669.1       6  679.09    8.32
  699.15    5.12   708.8       0  873.51     .31  878.82    2.34  1043.6    2.58
 1144.33     .53 1543.37    -.03 1573.65   -2.21 1656.69   -1.23    1665     3.3
    1750     3.3  1757.2     .79 1812.65   -1.42 1852.44      .3 1994.27   -4.72
 2083.53   -4.88  2135.8   -1.26    2151    7.05  2167.1   11.27 2311.91   13.92
#Mann= 7 ,-1 , 0
       0    .055       0  679.09   .0285       0  878.82    .035       0
 1144.33   .0285       0    1665    .035       0  1757.2   .0285       0
  2167.1    .055       0
Levee=-1,679.53,8.39,0,,,Levee 9,
Bank Sta=699.15,2167.1
XS Rating Curve= 0 ,0
Exp/Cntr(USF)=0.5,0.3
Exp/Cntr=0.3,0.1

Type RM Length L Ch R = 1 ,19130.49,499.21,500.44,499.99
XS GIS Cut Line= 2
     376550.8517    5906544.6705376574.1121869635904135.46357957
#Sta/Elev= 30
       0    3.06   29.99    6.06   39.99    4.72  169.95    5.25  254.93    4.18
  554.84    5.13  619.82     7.1  669.81    5.93  774.78    6.72  803.99   -1.48
  836.72   -1.52  916.14    1.21 1088.83    2.21 1098.51   -1.92 1117.95   -2.51
 1157.24   -1.31 1167.17   -2.34 1197.14     -.6 1217.48   -1.59 1227.52     -.1
 1369.98     .45 1441.29     .28 1593.99   -2.77 1716.95   -1.24 1963.51    -.73
 2202.71   -2.34 2229.37   11.64 2279.35   10.44 2364.33   10.79 2409.31   12.46
#Mann= 5 ,-1 , 0
       0    .055       0  774.78   .0285       0  916.14    .035       0
 1098.51   .0285       0 2229.37    .055       0
Levee=-1,764.47,6.93,-1,2230.24,11.65,Levee 9,Levee 10
Bank Sta=774.78,2229.37
XS Rating Curve= 0 ,0
Exp/Cntr(USF)=0.5,0.3
Exp/Cntr=0.3,0.1

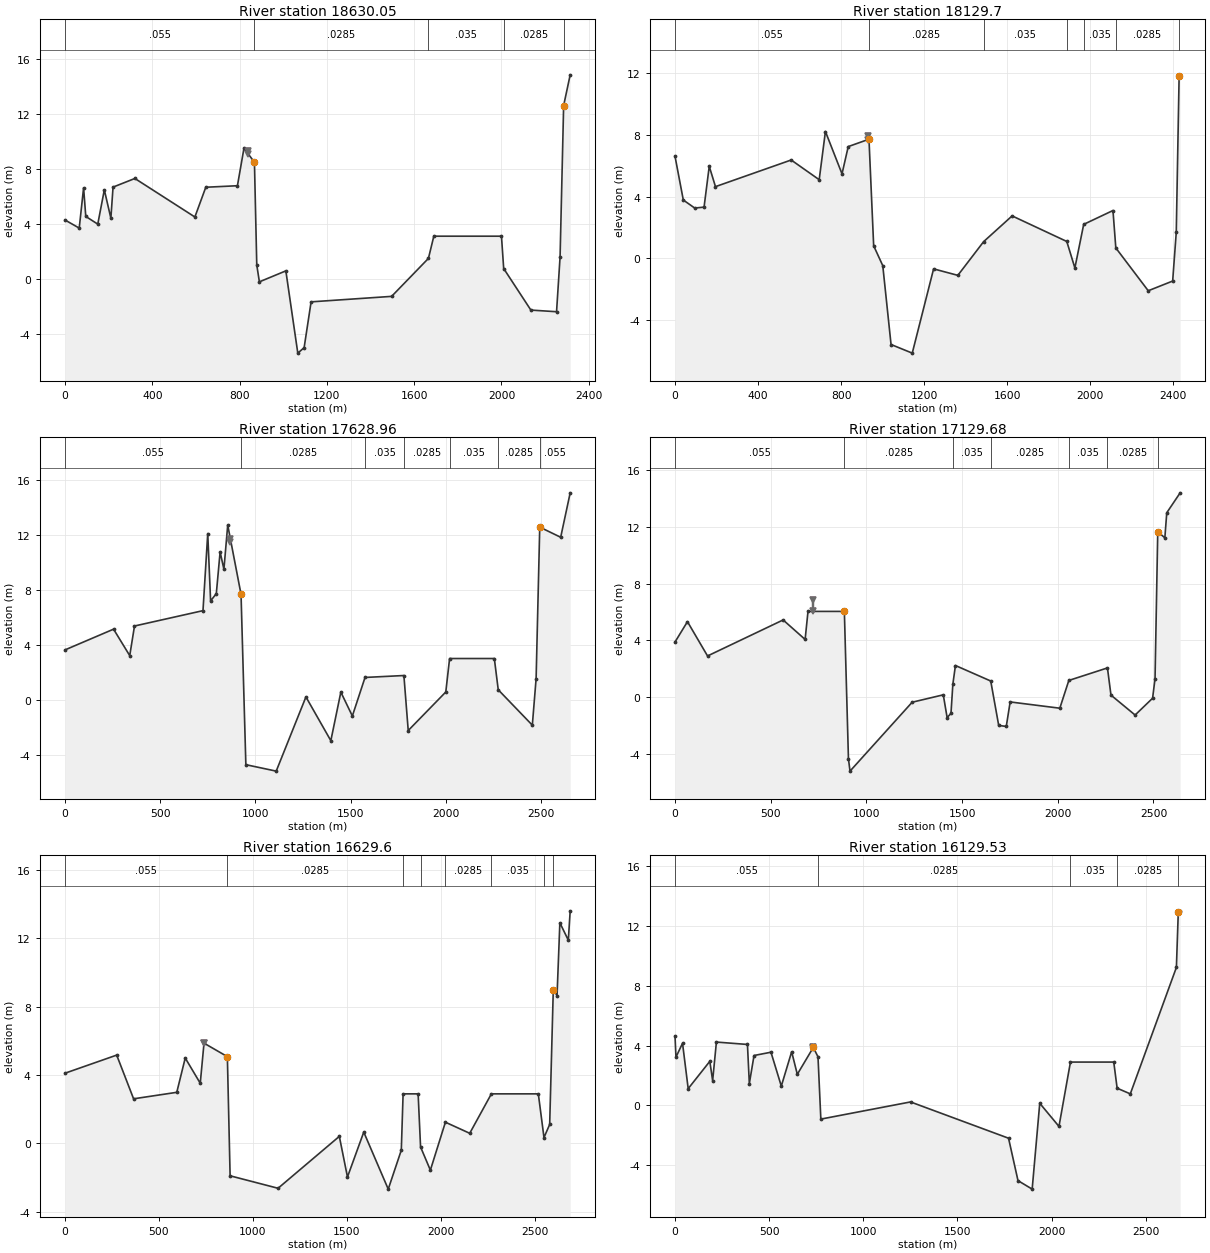
Type RM Length L Ch R = 1 ,18630.05,499.27,500.35,499.48
XS GIS Cut Line= 2
     377049.9631    5906554.4619377072.3123497025904239.62897053
#Sta/Elev= 30
       0    4.28      65    3.69      85    6.63      95    4.54     150    3.98
     180    6.48  209.99    4.41  219.99    6.68  319.99    7.31  594.99     4.5
  644.98    6.67  789.98    6.78  819.98    9.52  867.93    8.49  878.61       1
  890.58    -.23 1011.88     .57 1066.66   -5.43 1095.67   -5.03 1127.61   -1.69
 1496.55   -1.29 1665.28    1.48    1690     3.1    2000     3.1 2010.17     .74
 2134.75   -2.29 2252.45   -2.41 2268.63     1.6 2284.94   12.63 2314.94   14.87
#Mann= 5 ,-1 , 0
       0    .055       0  867.93   .0285       0 1665.28    .035       0
 2010.17   .0285       0 2284.94    .055       0
Levee=-1,840.7,9.28,-1,2315.18,14.78,Levee 9,Levee 10
Bank Sta=867.93,2284.94
XS Rating Curve= 0 ,0
Exp/Cntr(USF)=0.5,0.3
Exp/Cntr=0.3,0.1

Type RM Length L Ch R = 1 ,18129.7 ,500.09,500.74,500.29
XS GIS Cut Line= 2
     377548.4327    5906630.7123377571.9285976455904197.11987968
#Sta/Elev= 30
       0    6.62   39.98    3.78   94.95    3.26  139.93    3.32  164.91    5.97
   194.9    4.65   559.7    6.38  694.63     5.1  724.61    8.23  804.57    5.48
  834.55    7.25   934.5    7.73  957.07     .81 1000.93    -.48 1040.81    -5.6
 1142.98   -6.16 1245.83    -.69 1362.59   -1.11 1486.97    1.08 1624.13    2.75
 1887.51    1.09 1926.48    -.63 1968.94     2.2    2110     3.1 2123.73     .67
 2279.93   -2.11 2397.59   -1.48 2414.96    1.69  2428.7   11.82  2433.7   11.91
#Mann= 7 ,-1 , 0
       0    .055       0   934.5   .0285       0 1486.97    .035       0
 1887.51   .0285       0 1968.94    .035       0 2123.73   .0285       0
  2428.7    .055       0
Levee=-1,927.82,7.91,0,,,Levee 9,
Bank Sta=934.5,2428.7
XS Rating Curve= 0 ,0
Exp/Cntr(USF)=0.5,0.3
Exp/Cntr=0.3,0.1

Type RM Length L Ch R = 1 ,17628.96,499.07,499.28,499.22
XS GIS Cut Line= 2
     378048.2954    5906647.3491378073.9129169475903994.00978334
#Sta/Elev= 30
       0    3.63  254.85    5.14   339.8    3.21  364.79    5.37  724.58    6.49
  749.56   12.11  764.56     7.2  794.54    7.73  814.53   10.77  834.51    9.51
   854.5   12.73  924.46    7.68  949.78   -4.74 1109.22   -5.21 1265.31      .2
 1396.14   -2.99 1448.73     .55 1509.21   -1.19 1575.77    1.62 1779.93    1.76
 1802.66   -2.25 2000.01     .56    2020       3    2255       3 2275.54     .72
 2454.56   -1.86 2474.45    1.53 2493.55   12.58 2603.49   11.84 2653.46   15.08
#Mann= 7 ,-1 , 0
       0    .055       0  924.46   .0285       0 1575.77    .035       0
 1779.93   .0285       0    2020    .035       0 2275.54   .0285       0
 2493.55    .055       0
Levee=-1,869.01,11.53,0,,,Levee 9,
Bank Sta=924.46,2493.55
XS Rating Curve= 0 ,0
Exp/Cntr(USF)=0.5,0.3
Exp/Cntr=0.3,0.1

Type RM Length L Ch R = 1 ,17129.68,501.79,500.08,500.22
XS GIS Cut Line= 2
     378547.0115    5906676.9166378572.495428576 5904037.4062686
#Sta/Elev= 30
       0    3.89   64.99    5.32  169.98    2.91  564.92    5.44  679.91    4.07
   694.9    6.04  884.88    6.04   906.3   -4.32  914.46   -5.18  1239.2    -.34
 1401.87     .18 1421.92   -1.42  1442.1   -1.12 1451.88     .93 1465.35    2.24
  1649.8    1.15 1691.46   -1.97 1730.99   -2.04 1751.29    -.32 2010.74    -.76
 2057.86    1.19 2259.69    2.07 2278.11     .16 2404.22   -1.24 2495.55    -.06
 2508.36    1.31 2522.55   11.64 2559.65   11.21 2569.64   12.97 2639.63   14.37
#Mann= 7 ,-1 , 0
       0    .055       0  884.88   .0285       0 1451.88    .035       0
  1649.8   .0285       0 2057.86    .035       0 2259.69   .0285       0
 2522.55    .055       0
Levee=-1,723.09,6.86,0,,,Levee 9,
Bank Sta=884.88,2522.55
XS Rating Curve= 0 ,0
Exp/Cntr(USF)=0.5,0.3
Exp/Cntr=0.3,0.1

Type RM Length L Ch R = 1 ,16629.6 ,502.37,500.06,500.22
XS GIS Cut Line= 2
     379046.7455     5906706.877 379072.712500435904017.34020981
#Sta/Elev= 30
       0    4.11  274.97    5.17  364.95    2.61  594.93    2.99  639.92       5
  719.91    3.52  739.91    5.87  864.24    5.08  878.88    -1.9 1134.19   -2.63
 1460.43     .41 1503.75   -1.97 1590.51     .66 1720.87   -2.68  1790.4     -.4
    1800     2.9    1880     2.9 1892.95    -.21 1945.19   -1.57 2025.18    1.24
 2154.73     .59    2270     2.9    2520     2.9 2550.13     .34 2580.46    1.11
 2599.67    9.01 2619.67    8.66 2634.67   12.92 2679.66    11.9 2689.66   13.62
#Mann= 8 ,-1 , 0
       0    .055       0  864.24   .0285       0    1800    .035       0
 1892.95   .0285       0 2025.18   .0285       0    2270    .035       0
 2550.13   .0285       0 2599.67    .055       0
Levee=-1,740.51,5.87,0,,,Levee 9,
Bank Sta=864.24,2599.67
XS Rating Curve= 0 ,0
Exp/Cntr(USF)=0.5,0.3
Exp/Cntr=0.3,0.1

Type RM Length L Ch R = 1 ,16129.53,375.92,507.29,629.41
XS GIS Cut Line= 2
     379546.2263    5906763.0699379572.1249567725904080.60585703
#Sta/Elev= 30
       0    4.65       5    3.23   39.96    4.16   69.94    1.12  184.83    2.95
  199.82    1.66   219.8    4.24  384.66    4.08  394.65    1.46  419.63    3.34
  509.55    3.56   564.5    1.29  619.45    3.59  649.42    2.08  734.34    3.88
  759.32    3.25  774.41    -.92 1250.86     .23 1771.25    -2.2  1821.4   -5.04
  1896.7   -5.61 1936.96     .14 2039.01   -1.41    2100     2.9    2330     2.9
  2347.9    1.15 2417.84     .77 2662.62    9.24 2672.61   12.93  2682.6   13.03
#Mann= 5 ,-1 , 0
       0    .055       0  759.32   .0285       0    2100    .035       0
  2347.9   .0285       0 2672.61    .055       0
Levee=-1,733.98,3.89,0,,,Levee 9,
Bank Sta=734.34,2672.61
XS Rating Curve= 0 ,0
Exp/Cntr(USF)=0.5,0.3
Exp/Cntr=0.3,0.1