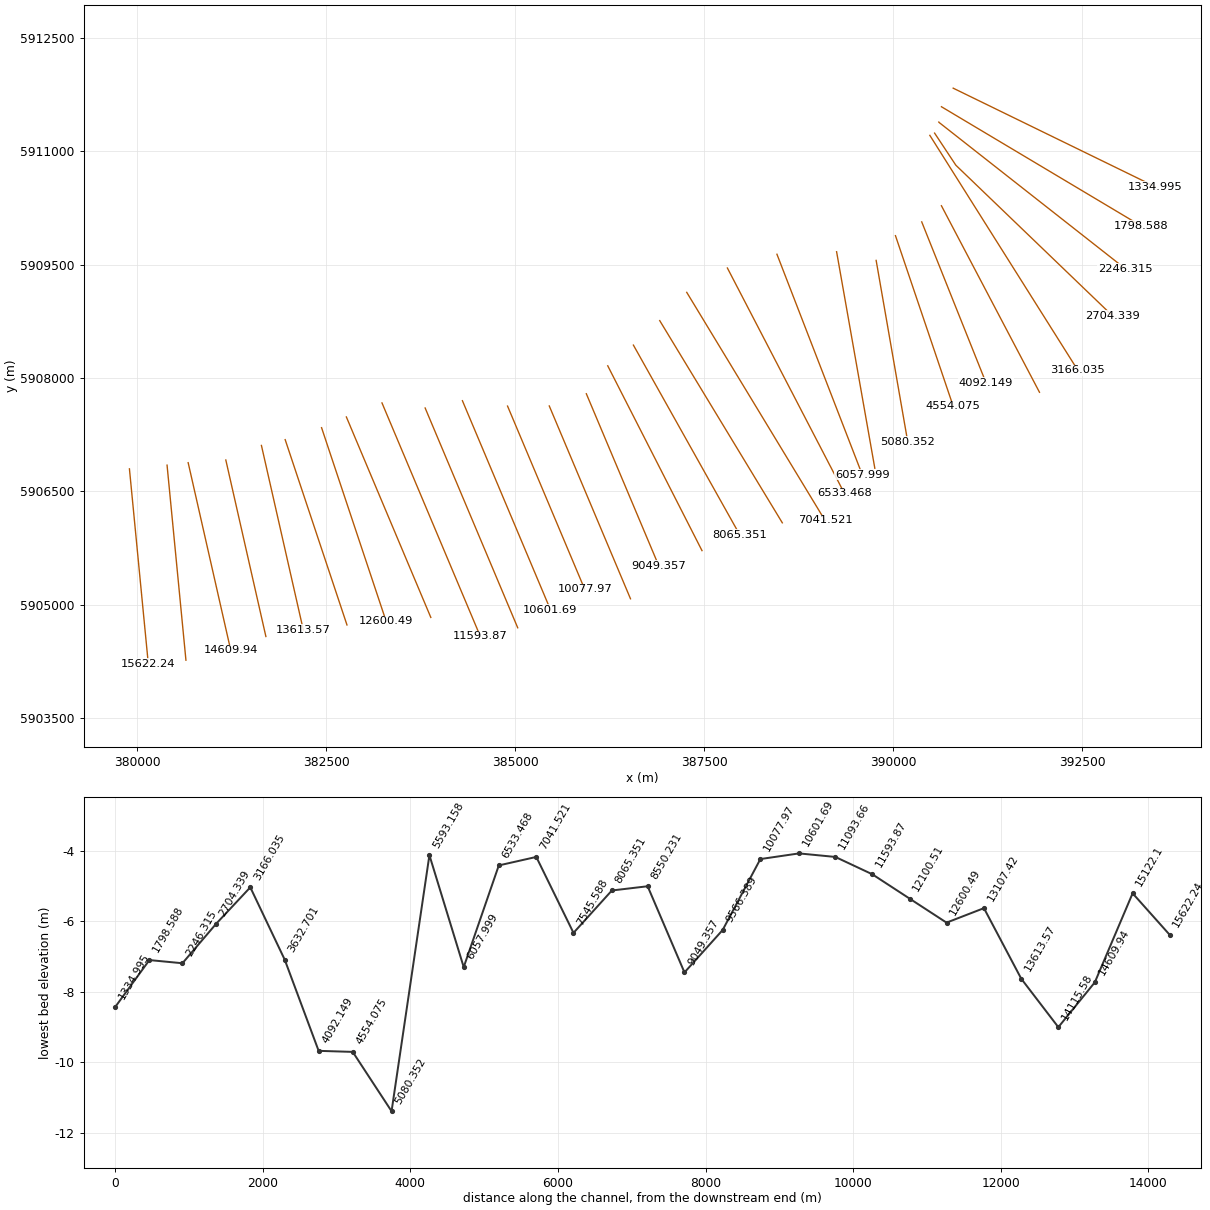
HEC-RAS study Churchill_Forecasting.prj: ChurchillRiver_Forecasting

--- Churchill_Forecasting.g11 (geometry) --- (continued)

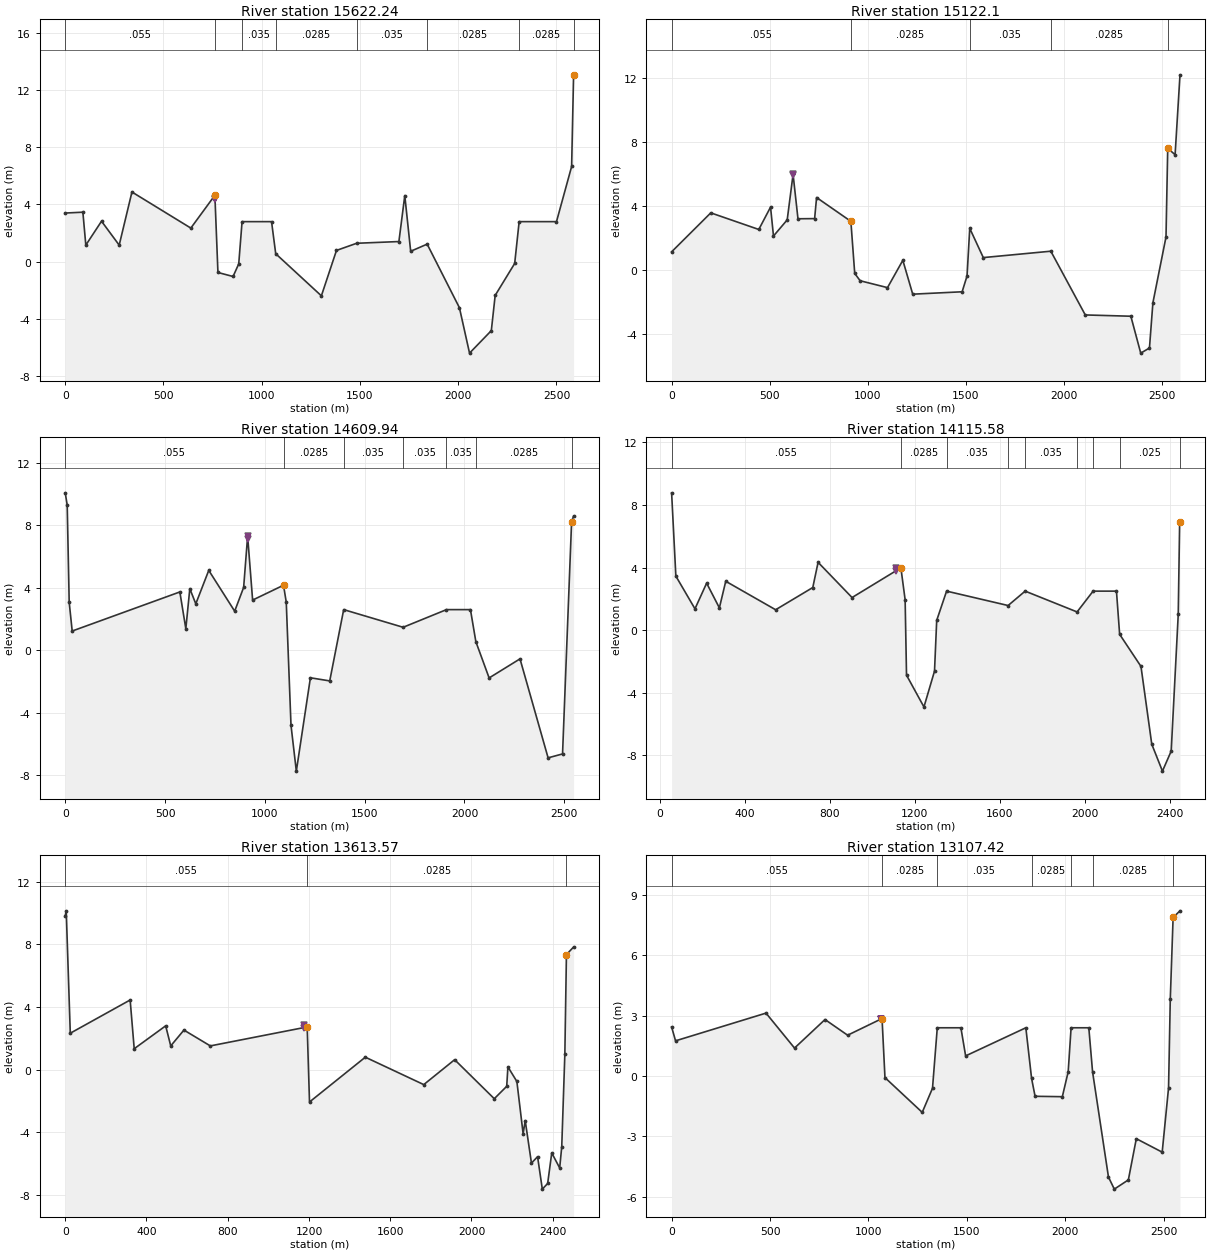
Type RM Length L Ch R = 1 ,15622.24,502.11,500.14,501.46
XS GIS Cut Line= 2
     379896.7436    5906799.3701380146.0105672965904224.39180596
#Sta/Elev= 30
       0     3.4    89.9    3.46  104.88    1.16  184.79    2.83  274.68    1.16
  339.61    4.87  639.26    2.35  761.59    4.64  777.19    -.75  854.15   -1.03
  883.03    -.15     900     2.8    1050     2.8  1071.2     .56 1303.56   -2.38
  1380.4     .79 1483.28    1.29 1698.04    1.41    1728    4.62 1757.97     .73
 1841.84    1.23 2006.04   -3.21 2057.52   -6.38 2168.37   -4.81 2187.98   -2.35
 2287.24    -.12    2310     2.8    2500     2.8 2577.02    6.65 2587.01   13.05
#Mann= 8 ,-1 , 0
       0    .055       0  761.59   .0285       0     900    .035       0
  1071.2   .0285       0 1483.28    .035       0 1841.84   .0285       0
    2310   .0285       0 2587.01    .055       0
Levee=-1,762.29,4.39,0,,,Levee 9,
Bank Sta=761.59,2587.01
XS Rating Curve= 0 ,0
Exp/Cntr(USF)=0.5,0.3
Exp/Cntr=0.3,0.1

Type RM Length L Ch R = 1 ,15122.1 ,308.62,512.16,677.55
XS GIS Cut Line= 2
     380394.3265    5906848.4833380644.0627147735904268.65853826
#Sta/Elev= 30
       0    1.13  199.76    3.57  444.47    2.53  504.39    3.93  519.38    2.12
  589.29    3.13  619.26    5.98  644.23     3.2  729.12    3.21  739.11    4.53
   913.9    3.04  933.55    -.22  961.21    -.68 1100.61   -1.11 1178.85      .6
 1229.26   -1.52 1481.17   -1.37 1506.16    -.38    1520     2.6 1589.05     .77
 1933.31    1.17    2109   -2.82  2341.3    -2.9 2391.73   -5.21 2436.22   -4.89
 2453.74   -2.06 2520.54    2.06 2529.34    7.61 2566.92    7.21 2591.89   12.21
#Mann= 5 ,-1 , 0
       0    .055       0   913.9   .0285       0    1520    .035       0
 1933.31   .0285       0 2529.34    .055       0
Levee=-1,618.54,5.99,0,,,Levee 9,
Bank Sta=913.9,2529.34
XS Rating Curve= 0 ,0
Exp/Cntr(USF)=0.5,0.3
Exp/Cntr=0.3,0.1

Type RM Length L Ch R = 1 ,14609.94,493.61,494.36,496.64
XS GIS Cut Line= 2
     380673.5607    5906880.9974381237.2363106745904397.48940654
#Sta/Elev= 30
       0   10.07    9.99    9.29   19.97    3.07   34.95    1.23  574.25    3.73
  604.21    1.38  624.19    3.94  654.15    2.97  719.07    5.11   848.9     2.5
  893.84    4.02  913.81     7.3  938.78    3.21 1093.58    4.16 1107.27    3.08
 1131.08    -4.8 1157.77   -7.73 1228.28   -1.76 1325.07   -1.96    1395     2.6
  1692.8    1.47    1910     2.6    2030     2.6 2057.09     .55 2123.53   -1.77
 2278.22    -.55 2418.97   -6.88 2491.35   -6.63  2536.7    8.23 2546.68    8.58
#Mann= 7 ,-1 , 0
       0    .055       0 1093.58   .0285       0    1395    .035       0
  1692.8    .035       0    1910    .035       0 2057.09   .0285       0
  2536.7    .055       0
Levee=-1,914.75,7.32,0,,,Levee 9,
Bank Sta=1093.58,2536.7
XS Rating Curve= 0 ,0
Exp/Cntr(USF)=0.5,0.3
Exp/Cntr=0.3,0.1

Type RM Length L Ch R = 1 ,14115.58,502.3,502.01,505.04
XS GIS Cut Line= 2
381171.5856811245906916.59590779381701.5223553145904581.73902776
#Sta/Elev= 30
   54.99    8.78   74.98    3.46  164.96    1.37  219.95    3.01  279.94    1.43
  309.93    3.13  544.88    1.31  719.84    2.73  744.83    4.34   904.8    2.09
 1134.75    3.99 1154.74    1.95 1161.28   -2.87 1243.36    -4.9 1293.14   -2.61
 1303.42     .63    1350     2.5 1639.63    1.58    1720     2.5 1964.56    1.17
    2040     2.5    2150     2.5 2164.96    -.26 2265.42   -2.31 2316.27   -7.28
 2366.56      -9 2407.79   -7.72 2440.92    1.01 2447.58    6.89 2449.21    6.88
#Mann= 9 ,-1 , 0
   54.99    .055       0 1134.75   .0285       0    1350    .035       0
 1639.63   .0285       0    1720    .035       0 1964.56   .0285       0
    2040    .035       0 2164.96    .025       0 2447.58    .055       0
Levee=-1,1110.77,3.98,0,,,Levee 9,
Bank Sta=1134.75,2447.58
XS Rating Curve= 0 ,0
Exp/Cntr(USF)=0.5,0.3
Exp/Cntr=0.3,0.1

Type RM Length L Ch R = 1 ,13613.57,343.57,506.15,654.42
XS GIS Cut Line= 2
     381642.5406    5907109.1877382196.5057057055904668.46351006
#Sta/Elev= 30
       0    9.81       5   10.13   24.98    2.32  319.72    4.44   339.7    1.33
  494.57    2.79  519.54    1.51  584.49    2.52  714.37    1.51 1191.27    2.72
 1202.68   -2.07 1477.47     .79 1765.13    -.96 1917.23     .63 2112.32   -1.86
 2173.55   -1.07 2179.47     .17 2223.55    -.76 2254.31   -4.09 2264.64   -3.26
 2295.33   -5.97 2325.51   -5.56 2348.79   -7.63 2375.13   -7.27 2395.23   -5.32
 2434.35   -6.28 2444.49   -4.92 2459.76     .98 2467.58    7.34  2502.8    7.82
#Mann= 3 , 0 , 0
       0    .055       0 1191.27   .0285       0 2467.58    .055       0
Levee=-1,1176.1,2.87,0,,,Levee 9,
Bank Sta=1191.27,2467.58
XS Rating Curve= 0 ,0
Exp/Cntr(USF)=0.5,0.3
Exp/Cntr=0.3,0.1

Type RM Length L Ch R = 1 ,13107.42,506.78,506.93,512.59
XS GIS Cut Line= 2
     381956.6837    5907185.7673382774.003128878 5904735.0743965
#Sta/Elev= 30
       0    2.44   19.99    1.75   479.7    3.13  624.61    1.39  779.52    2.81
  894.44    2.03 1069.33    2.86 1084.16    -.08 1273.51   -1.81 1325.72    -.61
    1350     2.4    1470     2.4 1494.07       1    1800     2.4 1829.23    -.12
 1846.97   -1.01 1985.46   -1.03 2015.23     .21    2030     2.4    2120     2.4
 2139.19      .2 2219.94   -5.03 2249.62   -5.63 2320.98   -5.17 2361.43   -3.12
 2492.91   -3.79 2525.24    -.59 2533.97    3.81 2548.41    7.89 2583.39    8.22
#Mann= 7 ,-1 , 0
       0    .055       0 1069.33   .0285       0    1350    .035       0
 1829.23   .0285       0    2030    .035       0 2139.19   .0285       0
 2548.41    .055       0
Levee=-1,1062.85,2.85,0,,,Levee 9,
Bank Sta=1069.33,2548.41
XS Rating Curve= 0 ,0
Exp/Cntr(USF)=0.5,0.3
Exp/Cntr=0.3,0.1

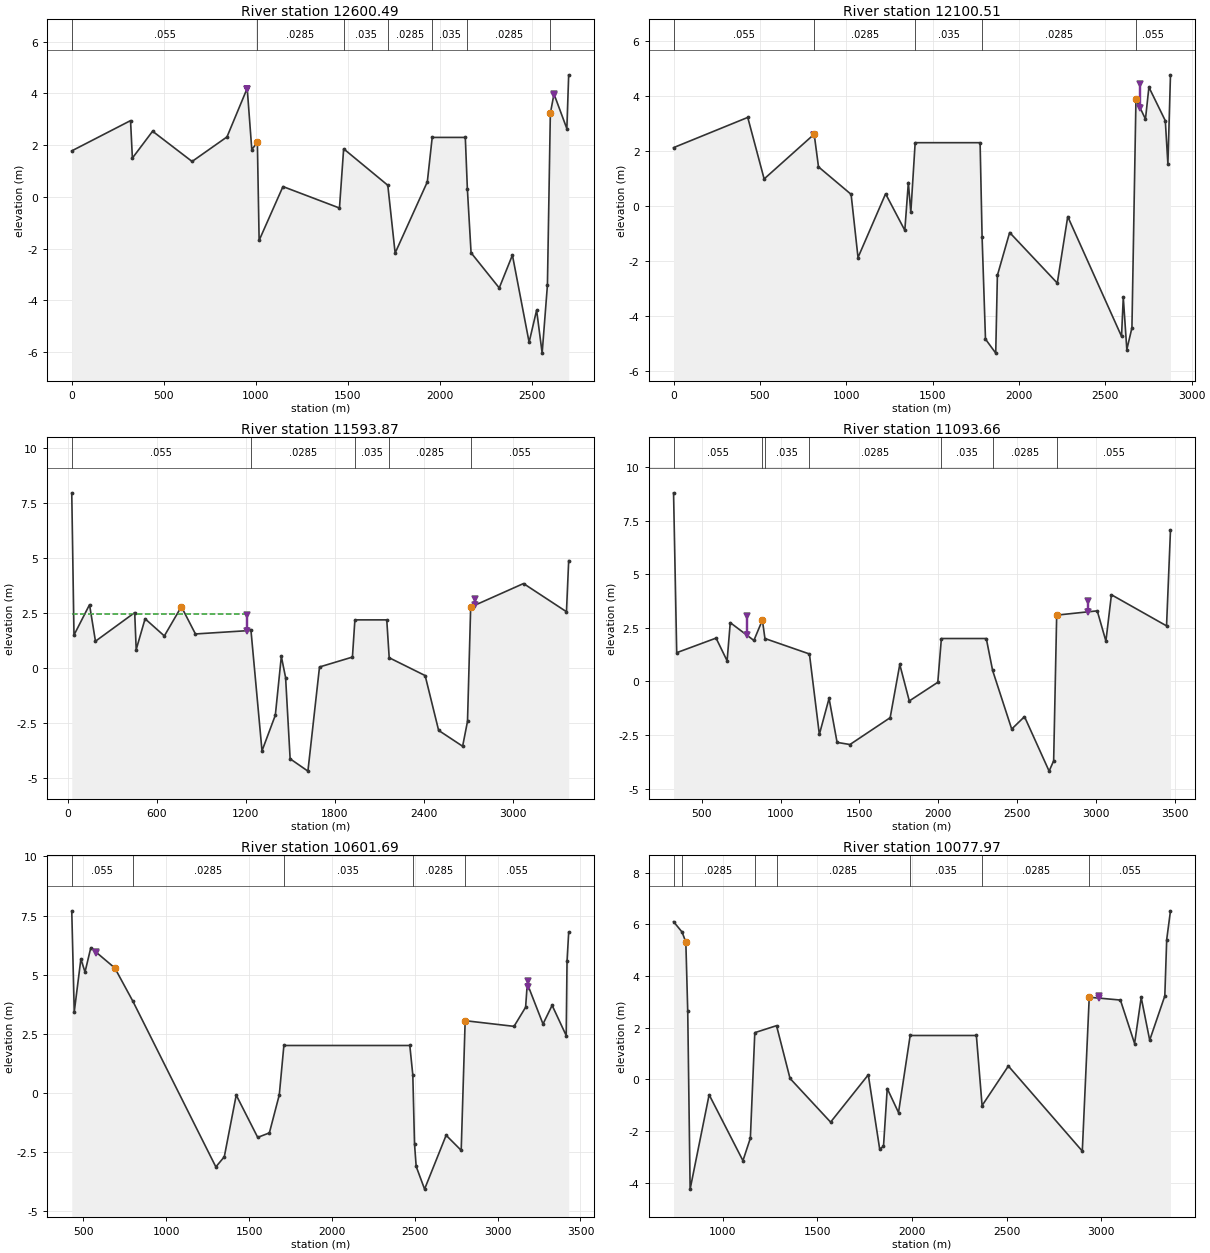
Type RM Length L Ch R = 1 ,12600.49,374.32,499.98,635.01
XS GIS Cut Line= 2
     382438.0603    5907344.0193383292.9487421035904780.67768102
#Sta/Elev= 30
       0    1.78  319.66    2.95  329.65     1.5  439.54    2.54  654.31    1.37
  844.11    2.32     954     4.2  978.97    1.83 1009.25    2.11 1018.85   -1.68
 1148.45      .4  1455.7    -.43 1478.45    1.86 1718.56     .45 1758.41   -2.17
 1933.41     .58    1960     2.3    2140     2.3 2151.17     .32 2171.34   -2.16
 2324.57   -3.52 2396.18   -2.25 2486.94   -5.62 2527.74   -4.38 2557.87   -6.04
 2586.54   -3.41 2602.46    3.23 2622.24    3.98 2692.17    2.64 2702.16    4.72
#Mann= 7 ,-1 , 0
       0    .055       0 1009.25   .0285       0 1478.45    .035       0
 1718.56   .0285       0    1960    .035       0 2151.17   .0285       0
 2602.46    .055       0
Levee=-1,953.33,4.17,-1,2623.52,3.97,Levee 9,Levee 11
Bank Sta=1009.25,2602.46
XS Rating Curve= 0 ,0
Exp/Cntr(USF)=0.5,0.3
Exp/Cntr=0.3,0.1

Type RM Length L Ch R = 1 ,12100.51,507.84,506.64,517.95
XS GIS Cut Line= 2
     382766.0584    5907486.1563383882.9724362735904834.38275725
#Sta/Elev= 30
       0    2.12  429.61    3.22  524.53     .98  814.27    2.61  839.24    1.42
 1028.06     .42  1068.1   -1.88 1227.78     .44  1339.1    -.89 1359.59     .85
 1373.84    -.24    1399     2.3    1775     2.3 1786.65   -1.15 1806.19   -4.85
  1865.5   -5.36 1875.11   -2.53 1946.11    -.97 2221.91   -2.81 2282.48    -.39
 2593.96   -4.75  2604.1   -3.33 2624.62   -5.23 2654.18   -4.44 2677.52    3.88
 2732.54    3.16 2752.52    4.32 2847.44     3.1 2862.43    1.52 2877.41    4.77
#Mann= 5 ,-1 , 0
       0    .055       0  814.27   .0285       0    1399    .035       0
 1786.65   .0285       0 2677.52    .055       0
Levee=-1,814.65,2.59,-1,2700.68,4.44,Levee 9,Levee 11
Bank Sta=814.27,2677.52
XS Rating Curve= 0 ,0
Exp/Cntr(USF)=0.5,0.3
Exp/Cntr=0.3,0.1

Type RM Length L Ch R = 1 ,11593.87,500.02,500.21,510.72
XS GIS Cut Line= 2
 383237.132849855907671.67422207384538.3860898175904582.24324925
#Sta/Elev= 30
   24.98    7.97   39.97    1.51  144.88    2.89  184.85    1.23  449.63    2.53
  459.63     .85  519.58    2.25  649.47    1.47  764.38     2.8   859.3    1.56
 1233.97    1.72 1308.37   -3.75 1398.27   -2.13 1438.68     .54 1467.52    -.42
 1498.12   -4.11 1618.06   -4.67 1696.26     .06 1918.41     .51    1935     2.2
    2150     2.2 2166.39     .48 2408.88    -.33 2499.89   -2.82 2661.77   -3.54
 2694.65   -2.41 2716.07    2.78  3072.5    3.85 3362.26    2.57 3377.25    4.89
#Mann= 5 ,-1 , 0
   24.98    .055       0 1233.97   .0285       0    1935    .035       0
 2166.39   .0285       0 2716.07    .055       0
Levee=-1,1209.75,2.42,-1,2742.75,3.17,Levee 9,Levee 11
#XS Ineff= 2 , 0
         1208.84    2.45
Permanent Ineff=
       F       F
Bank Sta=764.38,2716.07
XS Rating Curve= 0 ,0
Exp/Cntr(USF)=0.5,0.3
Exp/Cntr=0.3,0.1

Type RM Length L Ch R = 1 ,11093.66,491.8,491.97,502.32
XS GIS Cut Line= 2
383807.9580584745907604.52322911385032.3599334045904697.55254782
#Sta/Elev= 30
  319.93    8.79  339.93    1.34  589.87    2.02  659.85     .96  679.85    2.74
  829.82    1.91  883.79    2.86     900       2 1182.45    1.28 1245.39   -2.47
 1307.02    -.79 1357.95   -2.84 1439.62   -2.94 1694.85   -1.69 1755.94     .79
  1816.3    -.91 1997.19    -.04    2020       2    2305       2 2345.31     .51
 2466.34   -2.22 2547.56   -1.64 2703.86   -4.18 2732.63    -3.7 2751.84    3.09
 3009.34    3.29 3064.32    1.88 3099.31    4.04 3449.24    2.59 3474.23    7.05
#Mann= 7 ,-1 , 0
  319.93    .055       0  883.79   .0285       0     900    .035       0
 1182.45   .0285       0    2020    .035       0 2345.31   .0285       0
 2751.84    .055       0
Levee=-1,787.18,3.03,-1,2949.6,3.73,Levee 9,Levee 11
Bank Sta=883.79,2751.84
XS Rating Curve= 0 ,0
Exp/Cntr(USF)=0.5,0.3
Exp/Cntr=0.3,0.1

Type RM Length L Ch R = 1 ,10601.69,526.02,523.72,530.89
XS GIS Cut Line= 2
384301.0055540255907700.86502134385465.0994229265904937.07748273
#Sta/Elev= 30
  429.85     7.7  444.84    3.42  484.83    5.66  509.82    5.11  544.81    6.14
  689.76    5.28  798.93    3.87 1299.47   -3.14 1350.44   -2.71 1422.37     -.1
 1552.04   -1.89 1622.46    -1.7 1682.26    -.09    1710       2    2470       2
 2488.12     .75 2498.41   -2.17  2508.4   -3.12 2559.13   -4.08  2689.2    -1.8
 2780.11   -2.44 2804.01    3.05 3098.91    2.81 3168.89    3.62 3178.88    4.62
 3273.85    2.91 3328.83     3.7  3413.8    2.42  3418.8    5.56  3428.8    6.79
#Mann= 5 ,-1 , 0
  429.85    .055       0  798.93   .0285       0    1710    .035       0
 2488.12   .0285       0 2804.01    .055       0
Levee=-1,575.61,5.93,-1,3186.06,4.74,Levee 9,Levee 11
Bank Sta=689.76,2804.01
XS Rating Curve= 0 ,0
Exp/Cntr(USF)=0.5,0.3
Exp/Cntr=0.3,0.1

Type RM Length L Ch R = 1 ,10077.97,521.17,511.58,513.31
XS GIS Cut Line= 2
384898.0292449925907629.68823968 385917.752832965905208.66400365
#Sta/Elev= 30
  739.16     6.1  784.11     5.7  804.09    5.31  814.08    2.64  826.78   -4.24
  927.22    -.59 1105.96   -3.14 1145.18   -2.27 1168.67    1.81 1283.54    2.08
 1354.91     .04 1569.39   -1.65 1768.62     .18 1828.84   -2.69 1849.01   -2.59
 1868.77    -.35 1928.43   -1.28    1990     1.7    2340     1.7 2370.21   -1.01
 2509.08     .52 2900.01   -2.77 2936.67    3.18 3101.48    3.07  3176.4    1.39
 3211.36    3.17 3256.31    1.52 3336.22    3.23 3346.21    5.41 3366.18    6.52
#Mann= 7 ,-1 , 0
  739.16    .055       0  784.11   .0285       0 1168.67    .035       0
 1283.54   .0285       0    1990    .035       0 2370.21   .0285       0
 2936.67    .055       0
Levee=0,,,-1,2986.93,3.24,,Levee 11
Bank Sta=804.09,2936.67
XS Rating Curve= 0 ,0
Exp/Cntr(USF)=0.5,0.3
Exp/Cntr=0.3,0.1

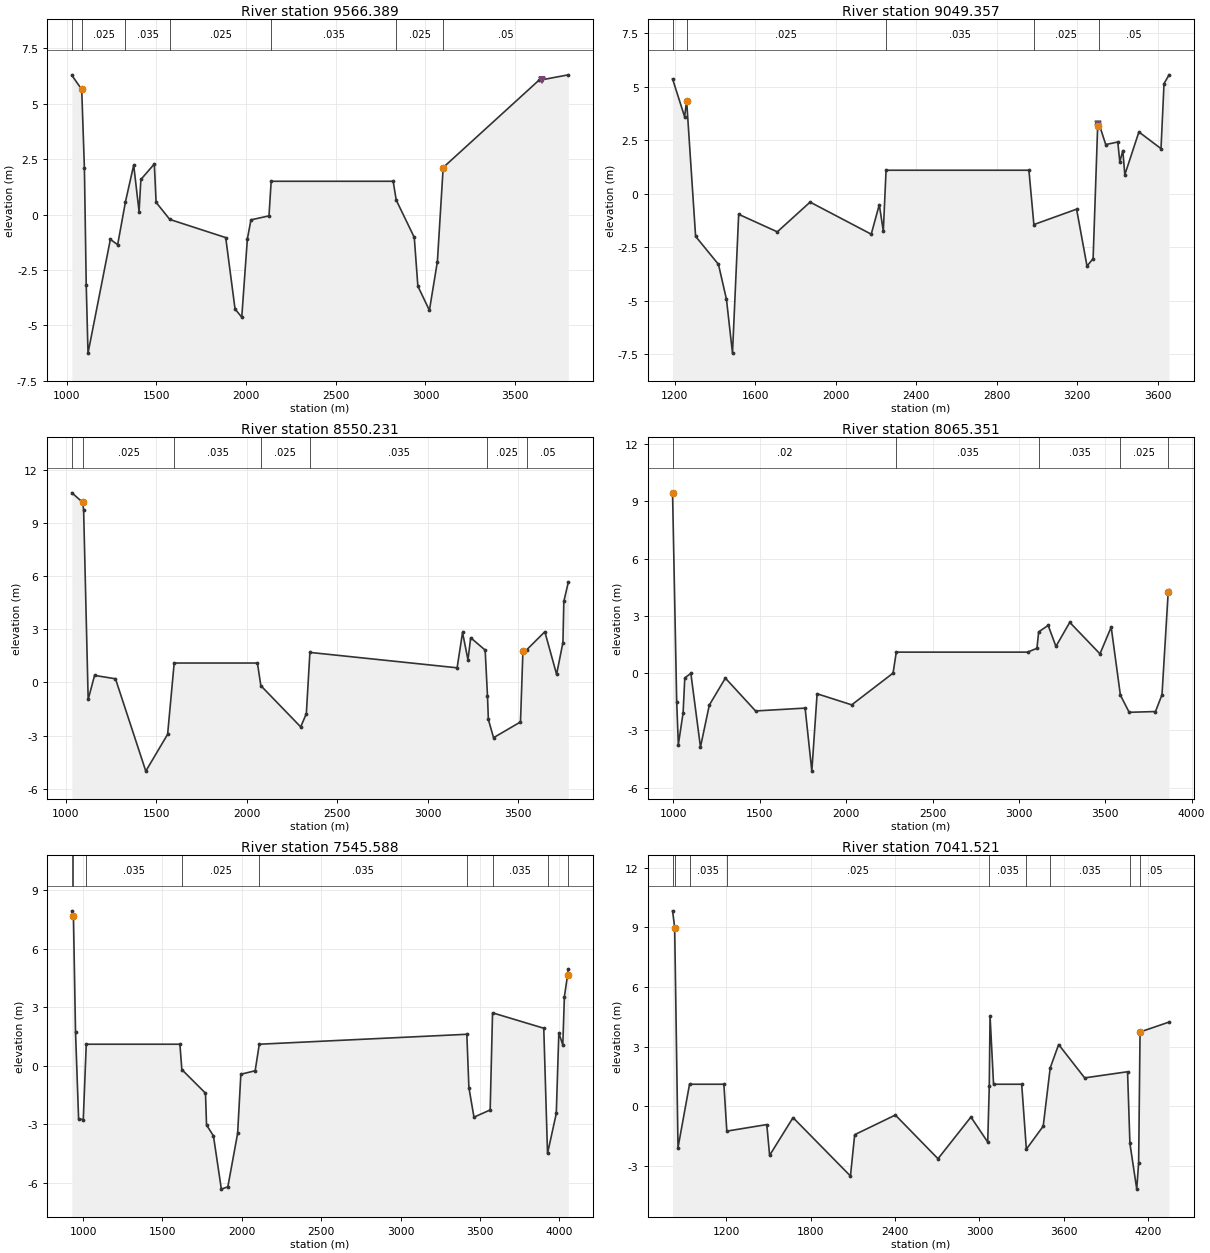
Type RM Length L Ch R = 1 ,9566.389,526.44,517.03,518.5
XS GIS Cut Line= 2
385449.7997380945907631.53848298386524.0371976565905081.08760957
#Sta/Elev= 30
 1029.06    6.28 1084.01    5.64 1098.99    2.08 1109.18    -3.2 1119.08   -6.25
 1243.67   -1.12 1284.32   -1.36 1327.92     .58 1373.74    2.23 1403.71     .13
  1413.7    1.58 1488.64    2.28 1498.63     .55 1574.67    -.22 1886.65   -1.04
 1938.64   -4.26 1976.05   -4.63 2007.33    -1.1 2027.41    -.24 2127.86    -.06
    2140     1.5    2820     1.5 2837.14     .65 2937.68   -1.03 2957.71   -3.23
 3022.05   -4.32 3066.55   -2.12 3098.76    2.12 3631.68    6.05 3796.52     6.3
#Mann= 7 ,-1 , 0
 1029.06    .055       0 1084.01    .025       0 1327.92    .035       0
 1574.67    .025       0    2140    .035       0 2837.14    .025       0
 3098.76     .05       0
Levee=-1,992.53,6.21,-1,3649.66,6.06,Levee 12,Levee 11
Bank Sta=1084.01,3098.76
XS Rating Curve= 0 ,0
Exp/Cntr(USF)=0.5,0.3
Exp/Cntr=0.3,0.1

Type RM Length L Ch R = 1 ,9049.357,354.9,499.13,661.51
XS GIS Cut Line= 2
 385939.925172245907792.99225504 386897.77358476 5905518.8719472
#Sta/Elev= 30
 1188.85    5.37 1248.79     3.6 1258.78    4.35 1303.36   -1.99 1416.97    -3.3
 1456.65   -4.93 1486.76   -7.45 1517.45    -.96 1709.48   -1.78  1872.4    -.39
 2176.28   -1.89 2216.36    -.51 2236.34   -1.75    2250     1.1    2960     1.1
 2984.65   -1.44 3196.95    -.72 3248.71   -3.38 3279.04   -3.03 3301.79    3.19
 3306.79    3.32 3341.76     2.3  3401.7    2.42 3411.69    1.49 3426.67    2.02
 3436.66     .89 3506.59    2.89 3616.49    2.11 3631.47    5.15 3656.45    5.56
#Mann= 5 ,-1 , 0
 1188.85    .055       0 1258.78    .025       0    2250    .035       0
 2984.65    .025       0 3306.79     .05       0
Levee=0,,,-1,3304.29,3.14,,Levee 11
Bank Sta=1258.78,3301.79
XS Rating Curve= 0 ,0
Exp/Cntr(USF)=0.5,0.3
Exp/Cntr=0.3,0.1

Type RM Length L Ch R = 1 ,8550.231,401.22,484.88,570.88
XS GIS Cut Line= 2
 386223.317029655908162.16379178387469.8446558355905717.89075788
#Sta/Elev= 30
 1034.53   10.72  1094.5   10.18  1099.5    9.75 1124.65    -.96    1160      .4
 1275.53     .21 1443.08   -5.01 1563.68   -2.93    1600     1.1    2060     1.1
 2078.92    -.18 2299.18   -2.51 2330.35   -1.76    2350     1.7 3163.57     .83
 3193.56    2.83 3223.54    1.28 3238.54    2.53 3318.57    1.83 3331.32    -.74
 3336.26   -2.09 3364.92   -3.12 3513.83   -2.23  3527.3    1.78  3548.4    1.85
 3648.35    2.87 3713.32     .46 3748.31    2.26 3753.31    4.58  3778.3    5.68
#Mann= 7 ,-1 , 0
 1034.53    .055       0  1094.5    .025       0    1600    .035       0
 2078.92    .025       0    2350    .035       0 3331.32    .025       0
  3548.4     .05       0
Bank Sta=1094.5,3527.3
XS Rating Curve= 0 ,0
Exp/Cntr(USF)=0.5,0.3
Exp/Cntr=0.3,0.1

Type RM Length L Ch R = 1 ,8065.351,440.96,519.76,595.84
XS GIS Cut Line= 2
386562.6949334715908436.15059991387968.2569076065905928.98040802
#Sta/Elev= 30
  994.76    9.44 1018.68    -1.5 1028.28   -3.74 1055.78   -2.08 1065.55    -.25
 1100.71    -.01 1156.31   -3.87 1207.61   -1.67 1300.48    -.26 1475.35   -1.98
 1762.15   -1.83 1801.06   -5.13 1831.54   -1.08 2031.91   -1.66 2271.35    .002
    2290     1.1    3050     1.1 3104.25     1.3 3114.25    2.16 3169.23     2.5
 3214.22     1.4  3294.2    2.66 3469.16    1.01 3534.14    2.41 3587.32   -1.15
 3638.18   -2.05 3790.57   -2.01 3828.24   -1.13 3864.06    4.23 3869.06    4.33
#Mann= 5 ,-1 , 0
  994.76     .02       0    2290    .035       0 3114.25    .035       0
 3587.32    .025       0 3864.06     .05       0
Bank Sta=994.76,3864.06
XS Rating Curve= 0 ,0
Exp/Cntr(USF)=0.5,0.3
Exp/Cntr=0.3,0.1

Type RM Length L Ch R = 1 ,7545.588,500.9,504.07,503.17
XS GIS Cut Line= 2
386910.6886386165908760.28079192388532.2559101445906085.77140968
#Sta/Elev= 30
  929.32    7.94  939.31    7.65  952.29    1.75  971.85   -2.74 1001.24   -2.76
    1020     1.1    1610     1.1 1622.14     -.2 1771.09   -1.41 1777.66   -3.04
 1821.25    -3.6 1871.01   -6.33 1911.96   -6.21 1973.58   -3.47 1993.86    -.44
 2084.04    -.26    2110     1.1 3417.49    1.61 3430.48   -1.12 3462.45   -2.64
 3564.48   -2.27 3579.49    2.71 3902.13    1.92 3925.84    -4.5 3980.98   -2.45
 3997.06    1.68 4022.05    1.06 4032.04    3.54 4052.02    4.64 4057.02    4.96
#Mann= 9 ,-1 , 0
  929.32    .055       0  939.31    .025       0    1020    .035       0
 1622.14    .025       0    2110    .035       0 3417.49    .025       0
 3579.49    .035       0 3925.84    .025       0 4052.02     .05       0
Bank Sta=939.31,4052.02
XS Rating Curve= 0 ,0
Exp/Cntr(USF)=0.5,0.3
Exp/Cntr=0.3,0.1

Type RM Length L Ch R = 1 ,7041.521,669.66,508.05,362.61
XS GIS Cut Line= 2
387268.1470556665909134.01635898389096.9485152045906117.70818616
#Sta/Elev= 30
   819.4    9.83  834.39    8.99  858.12   -2.09     940     1.1    1184     1.1
  1204.9   -1.26 1488.89    -.93 1508.96   -2.48 1675.45    -.58  2083.3   -3.52
 2113.31   -1.44 2402.29    -.45 2705.27   -2.65 2939.28    -.55 3058.58   -1.81
 3069.58       1  3075.1    4.54    3100     1.1    3300     1.1 3333.08   -2.17
 3452.88   -1.01 3502.45    1.92  3562.4     3.1 3747.27    1.42 4052.05    1.73
 4068.84   -1.88 4117.36   -4.18  4130.8   -2.84 4140.89    3.73 4346.84    4.23
#Mann= 9 ,-1 , 0
   819.4    .055       0  834.39    .025       0     940    .035       0
  1204.9    .025       0 3069.58    .035       0 3333.08    .025       0
 3502.45    .035       0 4068.84    .025       0 4140.89     .05       0
Bank Sta=834.39,4140.89
XS Rating Curve= 0 ,0
Exp/Cntr(USF)=0.5,0.3
Exp/Cntr=0.3,0.1

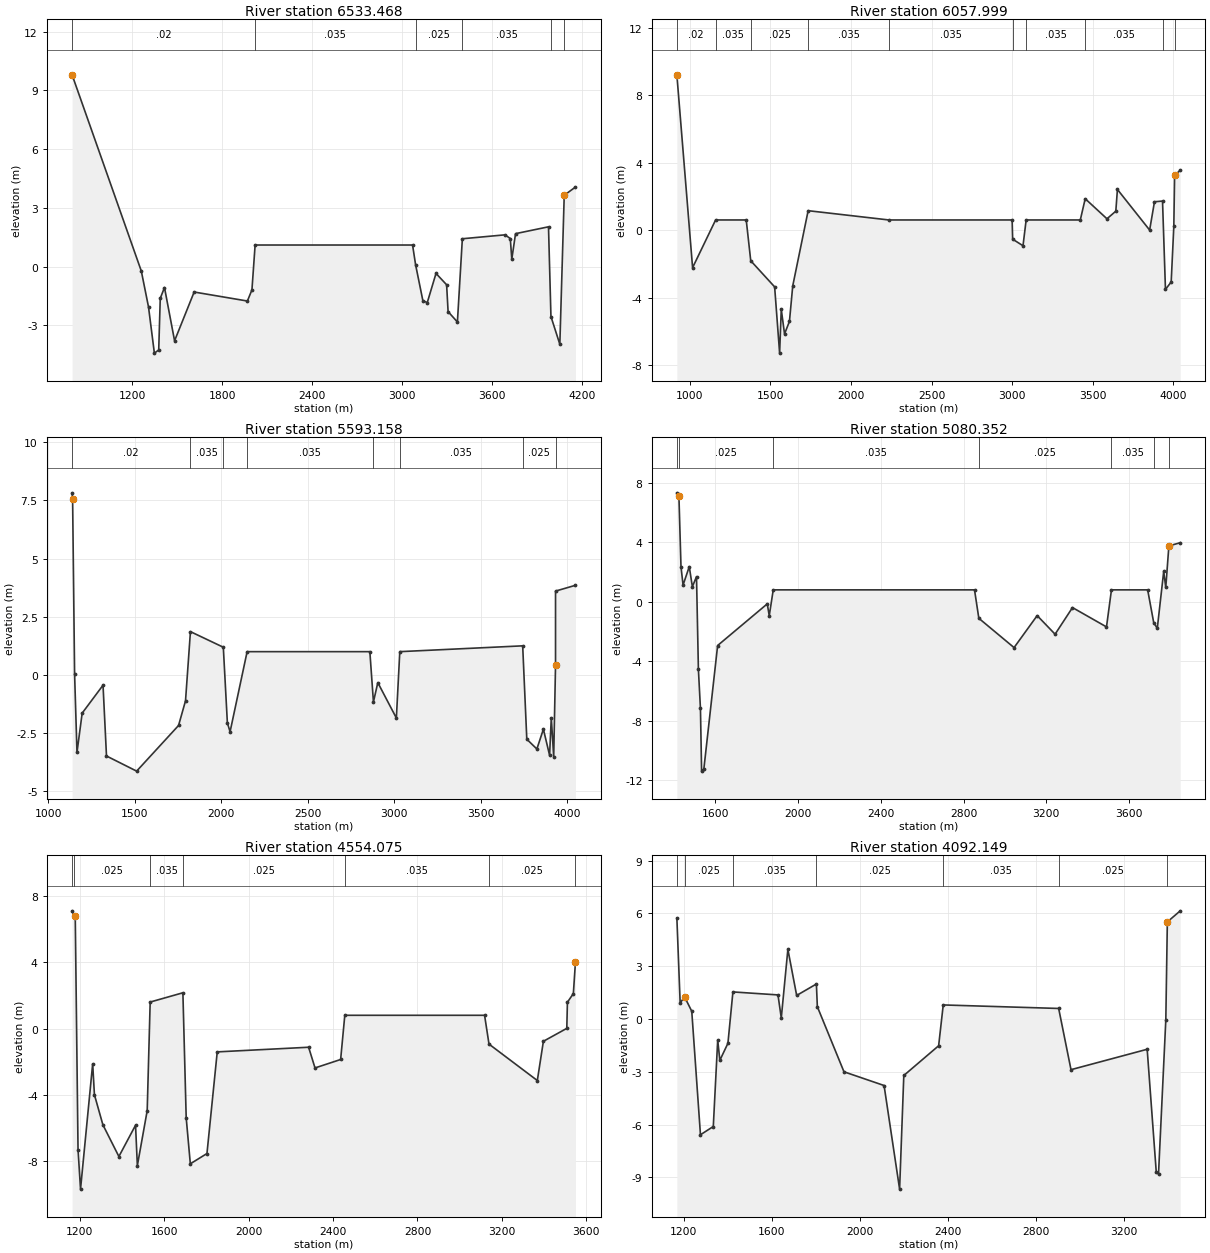
Type RM Length L Ch R = 1 ,6533.468,735.32,475.47,238.27
XS GIS Cut Line= 2
387805.7468626965909456.11270313389352.748295061 5906476.7372939
#Sta/Elev= 30
  799.33    9.79 1261.04    -.23 1308.95   -2.06 1348.12   -4.42 1377.09   -4.26
 1387.38   -1.62 1415.61   -1.07 1482.83   -3.79 1613.31    -1.3 1968.46   -1.76
  1998.8   -1.19    2020     1.1    3070     1.1 3090.27     .09 3138.69   -1.74
 3167.99   -1.84 3226.33    -.35 3297.14    -.93 3306.89    -2.3 3369.07   -2.83
 3402.04    1.42  3686.8    1.62 3721.77    1.43 3731.76     .38 3756.73    1.68
 3976.54    2.03 3992.85   -2.55 4052.16   -3.97 4081.45    3.64 4156.39    4.06
#Mann= 6 ,-1 , 0
  799.33     .02       0    2020    .035       0 3090.27    .025       0
 3402.04    .035       0 3992.85    .025       0 4081.45     .05       0
Bank Sta=799.33,4081.45
XS Rating Curve= 0 ,0
Exp/Cntr(USF)=0.5,0.3
Exp/Cntr=0.3,0.1

Type RM Length L Ch R = 1 ,6057.999,902.53,464.84,160.09
XS GIS Cut Line= 2
388461.2716433575909637.87214471389588.5124833875906724.74443417
#Sta/Elev= 30
  919.58    9.21 1017.16   -2.23    1160      .6    1350      .6 1378.03   -1.82
 1526.29   -3.37 1557.22    -7.3  1567.4    -4.7 1587.69   -6.16 1618.16   -5.42
 1638.63   -3.31 1734.21    1.15    2235      .6    3000      .6 3003.22    -.54
 3067.45    -.93    3087      .6    3423      .6 3453.43    1.86 3588.37     .67
 3643.35    1.12 3653.34    2.41 3853.26       0 3883.24    1.68 3933.22    1.72
 3951.43   -3.52 3986.95   -3.08  4003.3     .22 4008.27    3.25 4043.17    3.55
#Mann= 10 ,-1 , 0
  919.58     .02       0    1160    .035       0 1378.03    .025       0
 1734.21    .035       0    2235    .035       0 3003.22    .025       0
    3087    .035       0 3453.43    .035       0 3933.22    .025       0
 4008.27     .05       0
Bank Sta=919.58,4008.27
XS Rating Curve= 0 ,0
Exp/Cntr(USF)=0.5,0.3
Exp/Cntr=0.3,0.1

Type RM Length L Ch R = 1 ,5593.158,526.82,512.81,384.54
XS GIS Cut Line= 2
389250.1617883315909671.42304574 389755.785370025906807.62898116
#Sta/Elev= 30
 1138.77    7.82 1141.74    7.57 1153.27     .04 1167.07   -3.33 1197.04   -1.64
 1317.54    -.44 1337.52   -3.48 1511.71   -4.13 1753.84   -2.17 1794.09   -1.11
 1822.49    1.86 2012.44    1.19  2035.9   -2.06 2051.49   -2.44    2150       1
    2859       1  2879.7   -1.16    2905    -.33 3012.18   -1.85    3032       1
 3741.94    1.25 3765.71   -2.76 3823.92   -3.18 3861.54   -2.33 3897.37   -3.45
 3907.15   -1.84 3921.11   -3.51 3931.72     .41 3931.72     3.6 4046.85    3.85
#Mann= 8 ,-1 , 0
 1138.77     .02       0 1822.49    .035       0 2012.44    .025       0
    2150    .035       0  2879.7    .025       0    3032    .035       0
 3741.94    .025       0 3931.72     .05       0
Bank Sta=1141.74,3931.72
XS Rating Curve= 0 ,0
Exp/Cntr(USF)=0.5,0.3
Exp/Cntr=0.3,0.1

Type RM Length L Ch R = 1 ,5080.352,171.62,526.28,896.9
XS GIS Cut Line= 2
389773.3241114275909556.74655967390190.7926560965907159.37884481
#Sta/Elev= 30
 1414.09    7.32 1424.08    7.08 1434.07    2.35 1444.07    1.12 1474.05    2.36
 1489.04    1.01 1509.03    1.69 1518.22   -4.55 1528.07   -7.17 1533.68  -11.38
 1544.53  -11.24 1611.14   -2.94 1851.16    -.14 1860.67    -.94    1880      .8
    2853      .8 2873.86   -1.11 3044.15   -3.08 3155.87    -.93 3242.44   -2.18
 3326.62    -.39    3491   -1.69    3515      .8    3690      .8  3719.2    -1.4
 3736.51   -1.79 3767.56    2.04 3777.56     .96 3792.55    3.75 3847.51    3.97
#Mann= 7 ,-1 , 0
 1414.09    .055       0 1424.08    .025       0    1880    .035       0
 2873.86    .025       0    3515    .035       0  3719.2    .025       0
 3792.55     .05       0
Bank Sta=1424.08,3792.55
XS Rating Curve= 0 ,0
Exp/Cntr(USF)=0.5,0.3
Exp/Cntr=0.3,0.1

Type RM Length L Ch R = 1 ,4554.075,342.12,461.93,591.45
XS GIS Cut Line= 2
390028.8622690035909883.80463814390793.2241185295907625.73349269
#Sta/Elev= 30
 1164.47    7.11 1174.47     6.8 1179.47    6.78 1192.64   -7.31 1204.46    -9.7
    1262   -2.13 1270.28      -4 1310.23   -5.81 1386.11   -7.73 1464.99   -5.84
 1473.59   -8.28 1520.19   -4.96  1534.3     1.6 1689.24    2.16 1704.87   -5.39
 1724.43   -8.17 1803.21   -7.55 1851.89   -1.41 2284.66   -1.13 2314.93   -2.38
 2436.28   -1.87    2456      .8    3118      .8 3138.88    -.94 3367.75   -3.14
 3396.49    -.77 3507.35     .01 3510.28    1.59  3538.4    2.11 3548.39    4.03
#Mann= 7 ,-1 , 0
 1164.47    .055       0 1174.47    .025       0  1534.3    .035       0
 1689.24    .025       0    2456    .035       0 3138.88    .025       0
 3548.39     .05       0
Bank Sta=1179.47,3548.39
XS Rating Curve= 0 ,0
Exp/Cntr(USF)=0.5,0.3
Exp/Cntr=0.3,0.1

Type RM Length L Ch R = 1 ,4092.149,230.75,459.45,666.47
XS GIS Cut Line= 2
390376.2427330745910066.05904151391225.2543586975907941.08811592
#Sta/Elev= 30
 1169.12    5.75 1184.11     .91  1204.1    1.26 1236.84     .44 1276.37   -6.58
 1334.73   -6.11 1354.81   -1.19 1364.47   -2.35 1401.23   -1.38 1423.93    1.54
 1628.78    1.37 1643.77     .06 1673.75    3.96 1713.72    1.34 1803.41    1.99
 1807.73      .7 1928.77      -3 2111.08   -3.78 2181.66   -9.67 2200.76   -3.21
 2359.12   -1.52    2380      .8 2904.74      .6 2960.81   -2.88 3307.09   -1.72
 3348.38    -8.7 3358.62   -8.81 3391.84    -.04 3398.77    5.52 3457.41    6.15
#Mann= 7 ,-1 , 0
 1169.12    .055       0  1204.1    .025       0 1423.93    .035       0
 1803.41    .025       0    2380    .035       0 2904.74    .025       0
 3398.77     .05       0
Bank Sta=1204.1,3398.77
XS Rating Curve= 0 ,0
Exp/Cntr(USF)=0.5,0.3
Exp/Cntr=0.3,0.1

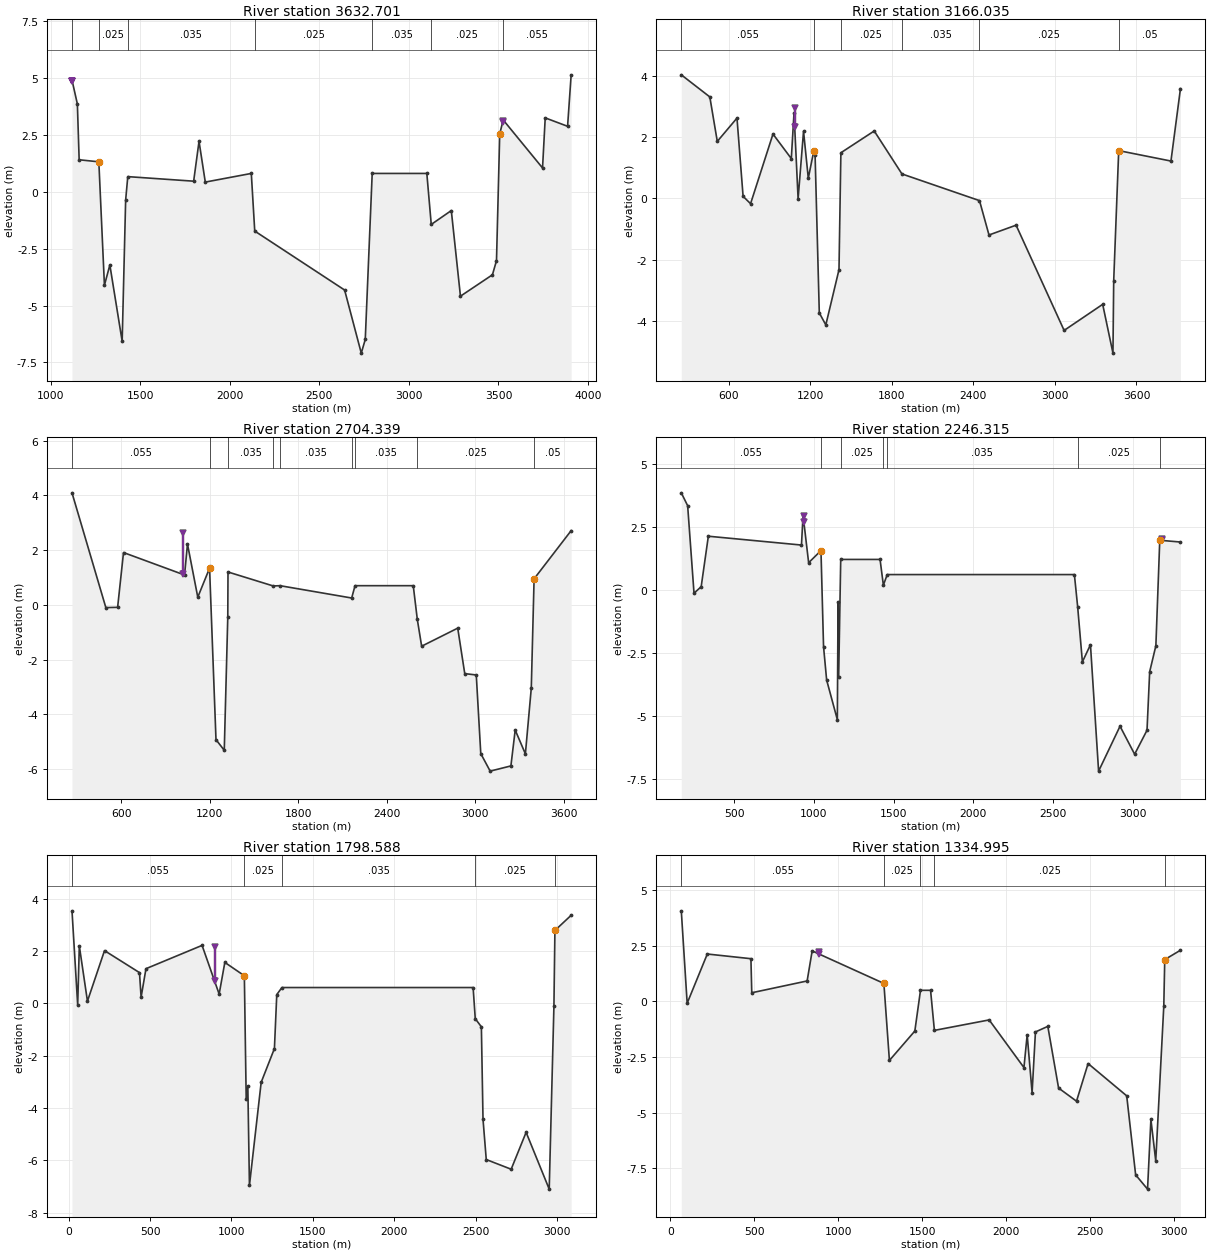
Type RM Length L Ch R = 1 ,3632.701,300.31,466.67,610.79
XS GIS Cut Line= 2
390636.7859122825910279.42911882391933.7067771495907812.47081517
#Sta/Elev= 30
 1118.83     4.9  1148.8    3.85 1158.79     1.4 1268.67    1.31 1299.91   -4.11
  1330.2   -3.22 1398.96   -6.57 1418.39    -.37  1430.3     .66 1798.12     .46
 1828.09    2.21 1863.05     .42    2120      .8 2139.16   -1.73    2641   -4.32
 2733.99   -7.09 2756.27   -6.49    2795      .8    3100      .8 3124.71   -1.44
 3236.67    -.83 3287.74   -4.59 3466.35   -3.65 3489.02   -3.03 3507.02    2.53
 3526.31    3.15 3746.08    1.04 3761.06    3.24 3885.93    2.87 3905.91    5.13
#Mann= 7 ,-1 , 0
 1118.83    .055       0 1268.67    .025       0  1430.3    .035       0
 2139.16    .025       0    2795    .035       0 3124.71    .025       0
 3526.31    .055       0
Levee=-1,1120.1,4.85,-1,3525.2,3.08,Levee 13,Levee 14
Bank Sta=1268.67,3507.02
XS Rating Curve= 0 ,0
Exp/Cntr(USF)=0.5,0.3
Exp/Cntr=0.3,0.1

Type RM Length L Ch R = 1 ,3166.035,68.41,461.7,899.38
XS GIS Cut Line= 2
390483.5749218815911210.51167892392442.0912198995908101.93129383
#Sta/Elev= 30
  249.94    4.03  459.89    3.31  514.87    1.86  659.84    2.62  704.83     .07
  759.82    -.17  924.78     2.1 1059.74     1.3 1079.74    2.79 1109.73    -.01
 1149.72    2.19 1184.71     .66  1224.7    1.54  1234.7    1.42 1265.75   -3.73
 1313.75   -4.12 1410.68   -2.32 1424.65    1.49    1670     2.2    1874      .8
 2444.87    -.07 2514.75   -1.19 2714.23    -.87 3067.77    -4.3 3351.57   -3.45
 3427.21   -5.04 3432.73   -2.68 3469.57    1.56 3854.07    1.22 3924.05    3.58
#Mann= 6 ,-1 , 0
  249.94    .055       0  1224.7    .025       0 1424.65    .025       0
    1874    .035       0 2444.87    .025       0 3469.57     .05       0
Levee=-1,1084.74,2.94,0,,,Levee 13,
Bank Sta=1224.7,3469.57
XS Rating Curve= 0 ,0
Exp/Cntr(USF)=0.5,0.3
Exp/Cntr=0.3,0.1

Type RM Length L Ch R = 1 ,2704.339,128.41,458.02,647.53
XS GIS Cut Line= 5
390546.482932983 5911240.2147802      390827.651     5910815.629
     391054.1582    5910597.9076     392772.7882    5908945.9397
392902.1857969325908821.56116645
#Sta/Elev= 30
  264.61    4.09  494.27     -.1  574.15    -.09  614.09    1.91 1028.19    1.09
 1048.14    2.22 1118.02     .28 1197.98    1.34 1241.56   -4.92 1297.72   -5.31
 1321.59    -.44 1323.08     1.2 1629.91     .69    1676      .7  2162.2     .25
    2185      .7    2580      .7 2607.48    -.53 2636.87   -1.51 2881.73    -.85
 2929.38   -2.51 3007.52   -2.56 3038.08   -5.43 3101.79   -6.07 3242.48   -5.88
 3271.66   -4.57 3340.77   -5.44 3380.81   -3.04 3399.84     .95 3651.36    2.71
#Mann= 9 ,-1 , 0
  264.61    .055       0 1197.98    .025       0 1323.08    .035       0
 1629.91    .025       0    1676    .035       0  2162.2    .025       0
    2185    .035       0 2607.48    .025       0 3399.84     .05       0
Levee=-1,1017.42,2.63,0,,,Levee 13,
Bank Sta=1197.98,3399.84
XS Rating Curve= 0 ,0
Exp/Cntr(USF)=0.5,0.3
Exp/Cntr=0.3,0.1

Type RM Length L Ch R = 1 ,2246.315,201.07,447.73,682.36
XS GIS Cut Line= 5
390602.0439653975911386.35436667     390604.7077    5911382.2168
     391119.4203    5910977.8704     393002.1305    5909498.8561
393064.9786581125909449.48402307
#Sta/Elev= 30
  167.25    3.84  207.15    3.33  247.12    -.14  292.09     .12  337.06    2.12
  921.68    1.77  931.68    2.95  966.67    1.07 1044.13    1.55 1060.28   -2.26
 1079.71   -3.58 1146.87   -5.15 1151.37    -.48 1155.11   -3.44 1168.14     1.2
    1415     1.2 1435.84     .18    1460      .6    2635      .6 2655.37    -.67
 2685.18   -2.86 2735.84   -2.18 2786.97   -7.19 2921.46   -5.41 3013.13   -6.52
 3090.88   -5.57  3107.6   -3.25 3146.49   -2.22 3170.91    1.96 3300.82    1.89
#Mann= 7 ,-1 , 0
  167.25    .055       0 1044.13    .025       0 1168.14    .025       0
 1435.84    .025       0    1460    .035       0 2655.37    .025       0
 3170.91     .05       0
Levee=-1,936.53,2.93,-1,3182.95,2,Levee 13,Levee 15
Bank Sta=1044.13,3170.91
XS Rating Curve= 0 ,0
Exp/Cntr(USF)=0.5,0.3
Exp/Cntr=0.3,0.1

Type RM Length L Ch R = 1 ,1798.588,304.53,463.59,618.77
XS GIS Cut Line= 2
390637.0621078185911589.11775628393271.2730150155910017.30875395
#Sta/Elev= 30
   19.98    3.53   54.96    -.07   64.95    2.19  114.91     .08  219.82    2.01
  434.65    1.17  444.64     .23  474.61    1.32  819.34    2.21  924.25     .35
  959.22    1.56 1079.12    1.05 1090.51   -3.66 1100.51   -3.17 1110.43   -6.96
 1182.54   -3.02 1263.96   -1.73 1278.38     .33    1310      .6    2485      .6
 2498.16    -.59 2535.72     -.9 2545.77   -4.43 2565.72   -5.97 2718.78   -6.34
 2810.65   -4.93 2952.61    -7.1  2981.6    -.11 2987.67    2.78  3087.5    3.36
#Mann= 5 ,-1 , 0
   19.98    .055       0 1079.12    .025       0    1310    .035       0
 2498.16    .025       0 2987.67     .05       0
Levee=-1,896.08,2.13,0,,,Levee 13,
Bank Sta=1079.12,2987.67
XS Rating Curve= 0 ,0
Exp/Cntr(USF)=0.5,0.3
Exp/Cntr=0.3,0.1

Type RM Length L Ch R = 1 ,1334.995,253.1,460.22,659.21
XS GIS Cut Line= 2
 390792.220074915911834.79118767393465.0882618155910531.40471842
#Sta/Elev= 30
   64.97    4.07   99.96    -.08  219.91    2.13  479.79    1.92  484.79     .39
  814.65     .92  844.64    2.27 1271.83     .81 1304.79   -2.65 1456.24   -1.33
    1490      .5    1550      .5 1572.79    -1.3 1899.07    -.83 2106.24   -2.97
 2125.52    -1.5 2154.84    -4.1 2174.77   -1.37 2248.47   -1.12 2312.62   -3.89
 2419.44   -4.48 2488.46   -2.79 2718.44   -4.24 2771.74   -7.79 2842.63   -8.43
 2862.62    -5.3 2891.47   -7.16 2939.42    -.21 2945.11    1.88 3038.69     2.3
#Mann= 5 ,-1 , 0
   64.97    .055       0 1271.83    .025       0    1490    .035       0
 1572.79    .025       0 2945.11     .05       0
Levee=-1,886.75,2.21,0,,,Levee 13,
Bank Sta=1271.83,2945.11
XS Rating Curve= 0 ,0
Exp/Cntr(USF)=0.5,0.3
Exp/Cntr=0.3,0.1