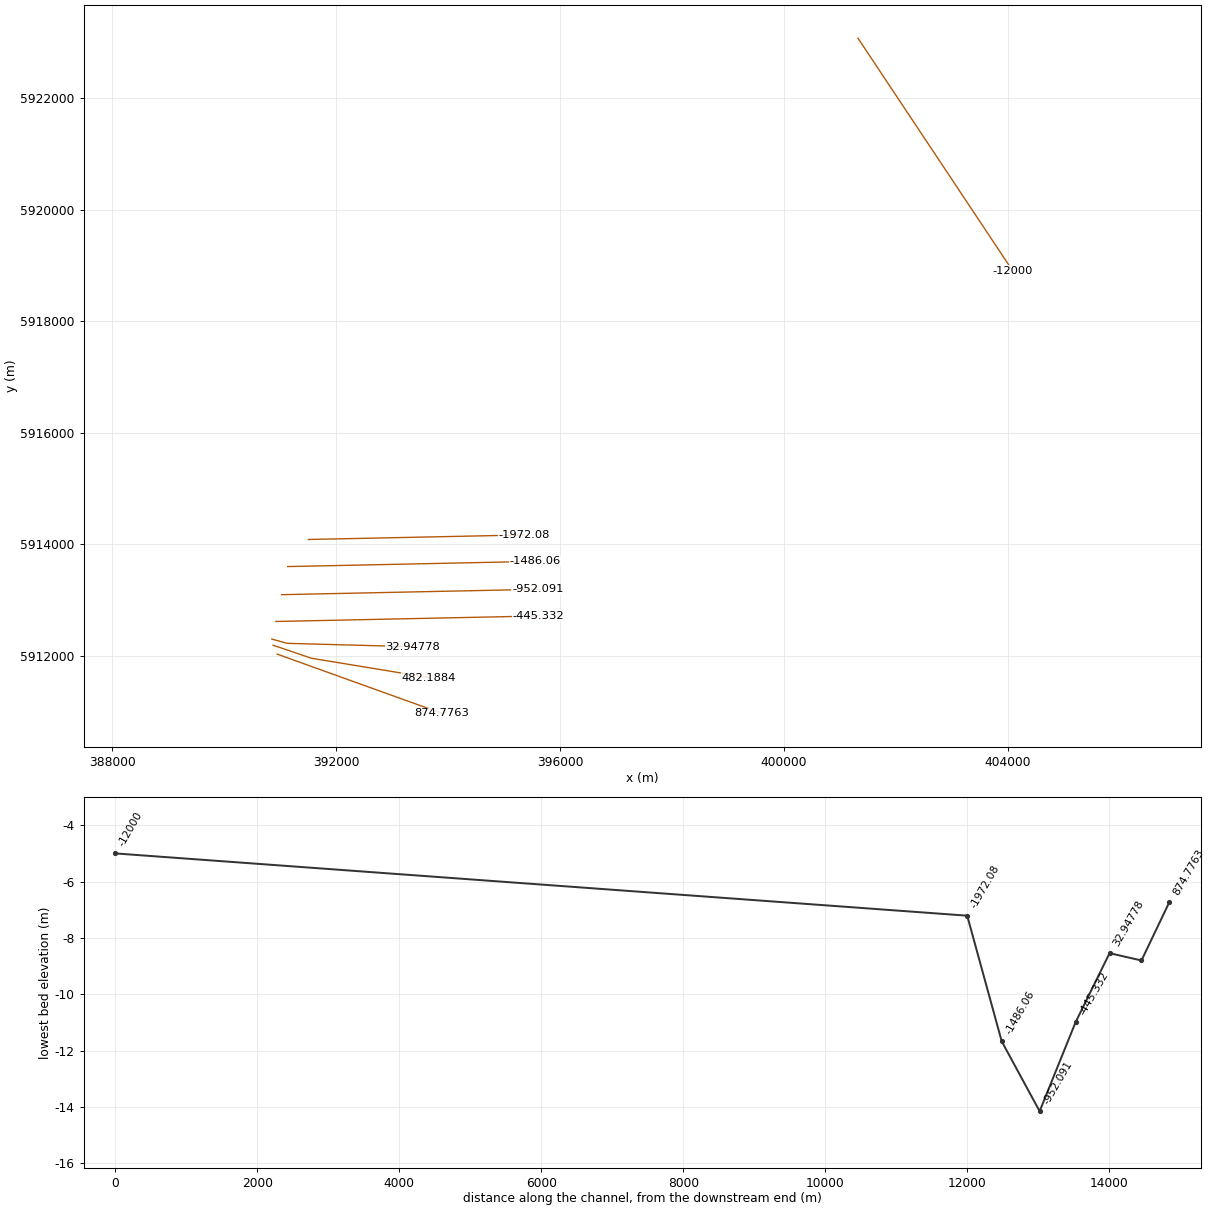
HEC-RAS study Churchill_Forecasting.prj: ChurchillRiver_Forecasting

--- Churchill_Forecasting.g11 (geometry) --- (continued)

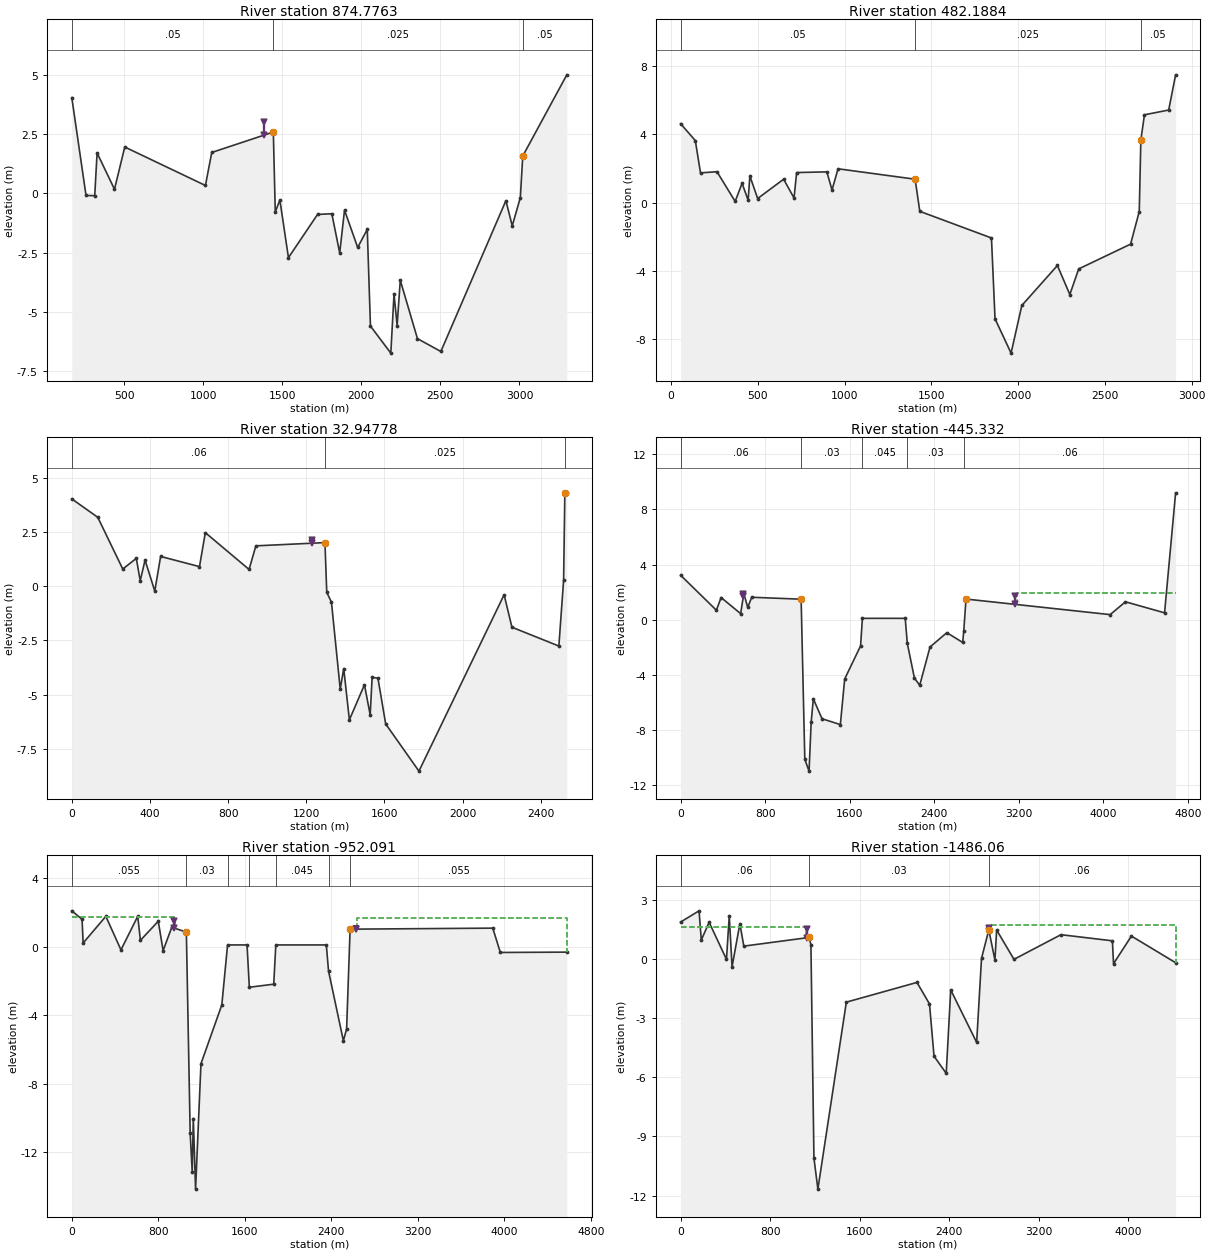
Type RM Length L Ch R = 1 ,874.7763,130.1,392.59,756.18
XS GIS Cut Line= 2
390945.7688758475912033.34841432393889.1190668035910970.79641399
#Sta/Elev= 30
  169.96    4.03  259.94    -.09  314.93     -.1  329.92     1.7   439.9     .17
  504.88    1.95 1014.76     .33 1054.75    1.72 1443.96    2.58 1456.32    -.79
 1485.34    -.28 1539.55   -2.71 1723.42    -.89 1813.77    -.86  1863.6   -2.51
 1894.03    -.71 1977.21   -2.28 2037.84   -1.52 2057.93   -5.59 2186.72   -6.73
 2206.94   -4.24 2226.61   -5.57 2246.48   -3.66 2355.05   -6.12 2503.01   -6.66
 2914.17    -.31 2954.33   -1.37 3005.48    -.18 3020.78    1.57 3299.23    4.99
#Mann= 3 , 0 , 0
  169.96     .05       0 1443.96    .025       0 3020.78     .05       0
Levee=-1,1387.68,3.02,0,,,Levee 13,
Bank Sta=1443.96,3020.78
XS Rating Curve= 0 ,0
Exp/Cntr(USF)=0.5,0.3
Exp/Cntr=0.3,0.1

Type RM Length L Ch R = 1 ,482.1884,112.67,449.24,772.32
XS GIS Cut Line= 6
390873.5266551075912193.57600555      391553.291    5911960.6071
     392048.4026     5911878.808     392049.5722    5911878.6148
     393653.9463    5911613.5507393658.868451062 5911612.7374948
#Sta/Elev= 30
   54.89    4.63  139.72    3.64  169.66    1.75  264.48    1.82  369.27     .08
  409.19    1.14  444.12     .15   454.1    1.57  499.01     .25  648.71    1.38
   708.6     .28  723.57    1.77  897.68    1.81  927.49     .75  962.27    1.99
 1406.43    1.38 1433.33     -.5 1846.32   -2.06 1866.93   -6.79  1959.3    -8.8
 2021.33   -6.01 2226.43   -3.67 2297.97   -5.37 2349.14   -3.87 2648.16   -2.42
 2698.07    -.51 2707.23    3.67 2728.01    5.15 2867.68    5.43 2907.59    7.49
#Mann= 3 , 0 , 0
   54.89     .05       0 1406.43    .025       0 2707.23     .05       0
Bank Sta=1406.43,2707.23
XS Rating Curve= 0 ,0
Exp/Cntr(USF)=0.5,0.3
Exp/Cntr=0.3,0.1

Type RM Length L Ch R = 1 ,32.94778,413.74,478.28,640.54
XS GIS Cut Line= 4
     390848.0599    5912303.9762     391122.9355    5912226.9858
     392022.9791    5912202.7855393370.1307005935912166.56340159
#Sta/Elev= 30
       0    4.04  132.88    3.19  260.85      .8  330.22    1.29  350.12     .26
  374.99    1.21  424.74    -.22  454.58    1.38  653.56     .91  683.41    2.48
  907.26     .78  942.08    1.87 1295.63    2.02 1304.89    -.28 1328.88    -.73
 1373.84   -4.75 1391.75    -3.8 1420.65   -6.17 1497.82   -4.55 1527.11   -5.94
 1537.09   -4.21 1566.68   -4.24 1606.47   -6.36 1776.63   -8.54 2212.53    -.39
 2252.57   -1.89 2492.79   -2.76  2517.1     .29 2523.36    4.32 2533.43    4.31
#Mann= 3 , 0 , 0
       0     .06       0 1295.63    .025       0 2523.36     .06       0
Levee=-1,1229,2.12,0,,,Levee 16,
Bank Sta=1295.63,2523.36
XS Rating Curve= 0 ,0
Exp/Cntr(USF)=0.5,0.3
Exp/Cntr=0.3,0.1

Type RM Length L Ch R = 1 ,-445.332,503.69,506.76,490.08
XS GIS Cut Line= 2
     390922.1354    5912619.2117     395604.1073    5912717.8173
#Sta/Elev= 30
       0    3.23  338.46     .69  383.32    1.61  568.12     .44  598.02    1.91
  635.23     .89  672.78    1.63  1140.3    1.49 1175.05  -10.13 1215.24  -10.99
 1235.39   -7.42 1255.77   -5.75 1338.17   -7.19 1511.34   -7.61 1552.43    -4.3
 1702.69    -1.9    1720      .1    2125      .1 2144.61   -1.71 2211.82   -4.23
 2262.08   -4.76 2359.67   -1.98  2518.8    -.94 2668.69   -1.65 2678.72    -.83
    2700     1.5  4063.6     .37 4208.51     1.3 4578.46      .5 4683.01    9.21
#Mann= 5 ,-1 , 0
       0     .06       0  1140.3     .03       0    1720    .045       0
 2144.61     .03       0 2678.72     .06       0
Levee=-1,594.28,1.9,-1,3167.39,1.69,Levee 16,Levee 17
#XS Ineff= 2 , 0
                         3178.96            1.93
Permanent Ineff=
       F       F
Bank Sta=1140.3,2700
XS Rating Curve= 0 ,0
Exp/Cntr(USF)=0.5,0.3
Exp/Cntr=0.3,0.1

Type RM Length L Ch R = 1 ,-952.091,534.3,533.97,511.38
XS GIS Cut Line= 2
     391024.7287    5913099.8707     395599.7588    5913196.2241
#Sta/Elev= 30
       0    2.09   94.92     1.6  104.91     .21  314.73    1.77  454.61    -.19
  609.47    1.77  634.45     .37  799.31    1.48  844.27    -.23   924.2    1.13
 1059.09     .85  1094.3  -10.87 1113.27  -13.15 1123.35  -10.03 1144.23  -14.15
 1194.17   -6.83 1386.91    -3.4    1440      .1    1620      .1  1641.3   -2.37
 1866.78   -2.19    1886      .1    2353      .1 2373.55   -1.43 2510.54   -5.49
 2540.43   -4.81 2572.78    1.02 3891.62    1.08 3961.56    -.34 4576.02    -.32
#Mann= 7 ,-1 , 0
       0    .055       0 1059.09     .03       0    1440    .045       0
  1641.3     .03       0    1886    .045       0 2373.55     .03       0
 2572.78    .055       0
Levee=-1,942.75,1.5,-1,2629.12,1.05,Levee 16,Levee 17
#XS Ineff= 2 , 0
          952.08    1.72 2638.65            1.66
Permanent Ineff=
       F       F
Bank Sta=1059.09,2572.78
XS Rating Curve= 0 ,0
Exp/Cntr(USF)=0.5,0.3
Exp/Cntr=0.3,0.1

Type RM Length L Ch R = 1 ,-1486.06,487.84,486.02,490.18
XS GIS Cut Line= 2
     391133.8455    5913604.0628     395556.5846    5913697.2088
#Sta/Elev= 30
       0    1.87  164.95    2.44  184.95     .96  254.93    1.86  409.88    -.02
  434.87    2.19  459.87     -.4  529.85    1.79  564.84     .65 1148.59    1.09
 1164.66     .72 1191.67   -10.1 1226.86  -11.67  1481.2   -2.19 2112.22   -1.19
 2224.21   -2.28 2264.84   -4.93  2373.8    -5.8 2413.96   -1.57 2645.68   -4.23
 2689.22     .03 2754.21    1.47 2809.19    -.06 2824.19    1.47 2979.14    -.02
 3399.02    1.23 3858.88     .92 3868.88    -.24 4028.83    1.16 4423.72    -.19
#Mann= 3 , 0 , 0
       0     .06       0 1148.59     .03       0 2754.21     .06       0
Levee=-1,1126.32,1.51,-1,2752.21,1.55,Levee 16,Levee 17
#XS Ineff= 2 , 0
         1119.17    1.64 2755.86            1.71
Permanent Ineff=
       F       F
Bank Sta=1148.59,2754.21
XS Rating Curve= 0 ,0
Exp/Cntr(USF)=0.5,0.3
Exp/Cntr=0.3,0.1

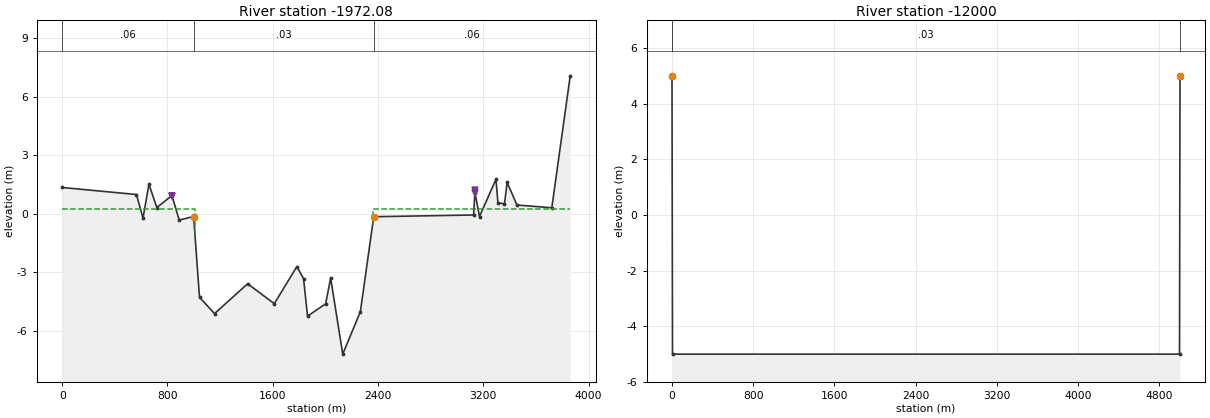
Type RM Length L Ch R = 1 ,-1972.08,12000,12000,12000
XS GIS Cut Line= 2
      391501.249    5914089.8532     395361.2289    5914171.1471
#Sta/Elev= 30
       0    1.34  564.39     .98  614.34    -.23  659.29    1.51  719.22     .31
   834.1     .93  889.04    -.33  998.92    -.15 1043.56   -4.29 1157.89   -5.13
  1409.3    -3.6 1611.97   -4.62  1783.5   -2.72 1834.26   -3.33 1864.56   -5.26
 2002.15   -4.63 2040.17    -3.3 2132.08   -7.21 2266.23   -5.03 2367.45    -.16
 3126.63    -.07 3136.62    1.08 3171.58    -.15 3296.45    1.76 3311.43     .56
 3361.38      .5 3381.36     1.6 3456.28     .44 3720.99      .3 3860.84    7.07
#Mann= 3 , 0 , 0
       0     .06       0  998.92     .03       0 2367.45     .06       0
Levee=-1,835.16,0.88,-1,3137.07,1.19,Levee 16,Levee 17
#XS Ineff= 2 , 0
         1009.87     .26 2358.68             .26
Permanent Ineff=
       F       F
Bank Sta=998.92,2367.45
XS Rating Curve= 0 ,0
Exp/Cntr(USF)=0.5,0.3
Exp/Cntr=0.3,0.1

Type RM Length L Ch R = 1 ,-12000  ,0,0,0
XS GIS Cut Line= 5
401323.5326386675923078.93330051401323.5326386675923078.93330051
 402705.653043435920992.72874756404087.7734481925918906.52419462
404087.7734481925918906.52419462
#Sta/Elev= 4
       0       5       5      -5    5000      -5    5005       5
#Mann= 3 , 0 , 0
       0     .06       0       0     .03       0    5005     .06       0
Bank Sta=0,5005
XS Rating Curve= 0 ,0
Exp/Cntr=0.3,0.1

Chan Stop Cuts=-1
Use User Specified Reach Order=0
Composite Channel Slope=5

--- Churchill_Forecasting.g14 (geometry) ---

Geom Title=Current Conditions - Nalcor LiDAR Clip
Program Version=4.10

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
River Reach=Churchill River ,Main

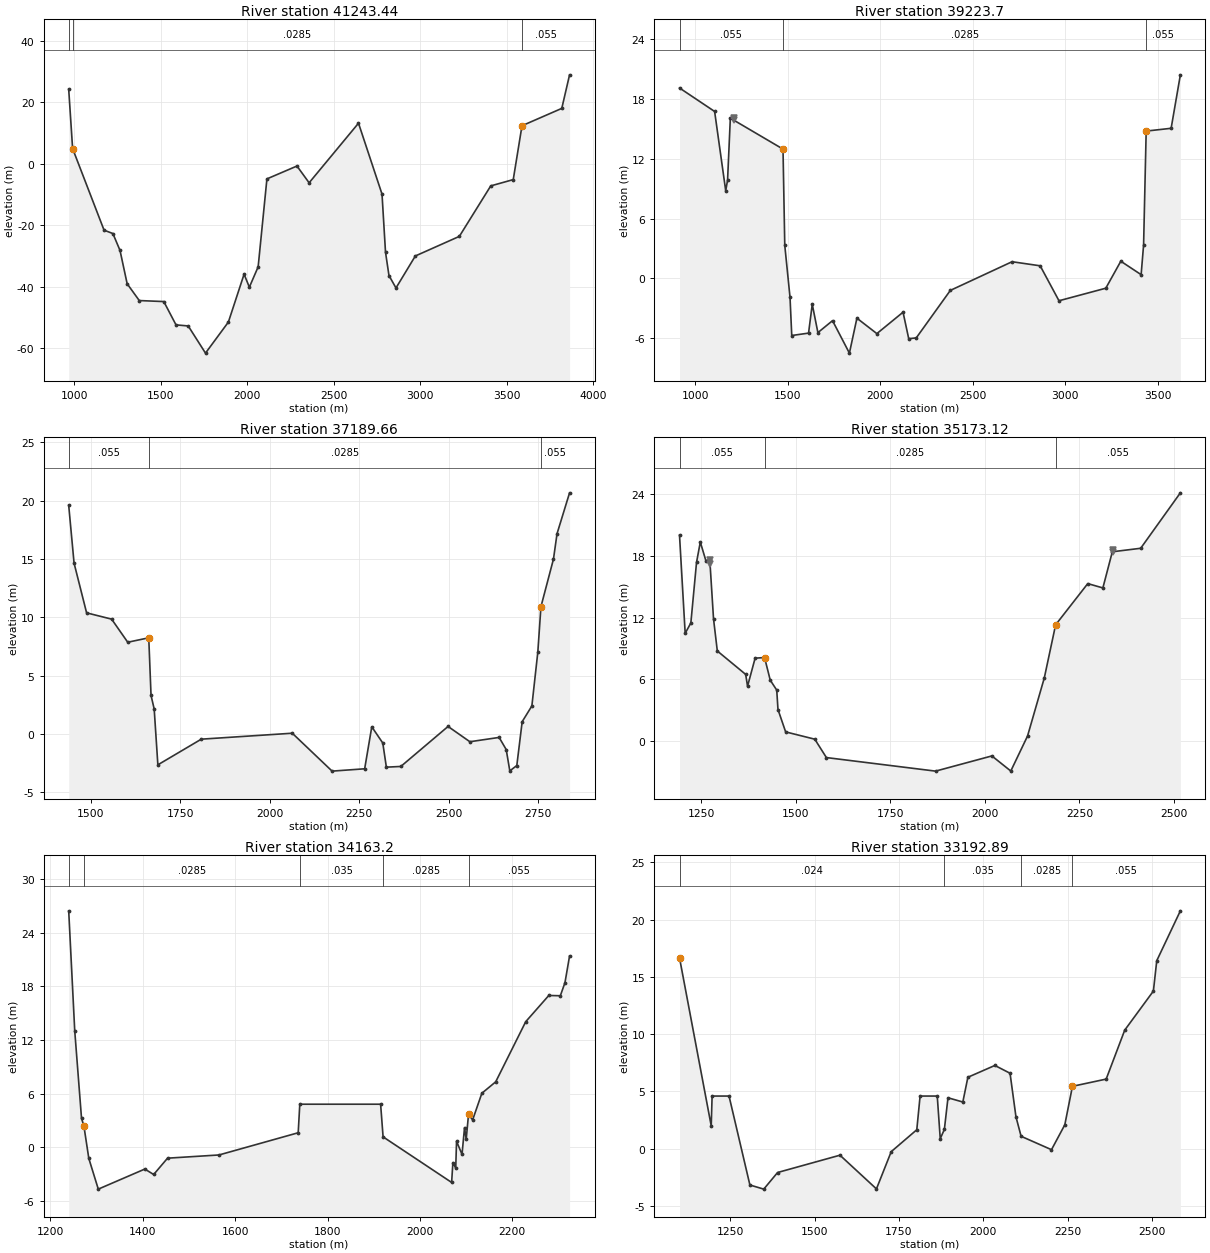
Type RM Length L Ch R = 1 ,41243.44,1199.65,1001.34,790.16
XS GIS Cut Line= 2
355538.233438958 5903210.9299795355305.4634303595900327.36277047
#Sta/Elev= 30
  969.32   24.28  991.86    4.99 1173.44  -21.58 1224.59  -22.69 1265.67  -28.19
 1306.91  -39.04 1376.88  -44.51 1518.59  -44.84  1589.1  -52.43 1659.56  -52.78
 1759.43  -61.63 1891.64  -51.51 1982.31  -35.92 2012.73  -40.16 2063.54  -33.53
 2114.18   -4.89  2287.7     -.7 2357.95   -6.16 2643.14   13.25 2778.97   -9.84
 2799.18  -28.77 2819.15  -36.36 2859.64  -40.41  2971.5  -29.99 3225.62  -23.61
 3407.01   -7.17 3536.99   -5.12 3587.48   12.42 3817.32   18.07 3862.29      29
#Mann= 3 , 0 , 0
  969.32    .055       0  991.86   .0285       0 3587.48    .055       0
Bank Sta=991.86,3587.48
XS Rating Curve= 0 ,0
Exp/Cntr(USF)=0.5,0.3
Exp/Cntr=0.3,0.1

Type RM Length L Ch R = 1 ,39223.7 ,827.11,1029.24,1183.39
XS GIS Cut Line= 2
357556.8319231745902704.63078815357141.5808249635900028.53733652
#Sta/Elev= 30
  914.37   19.11 1104.24   16.75 1164.19    8.79 1174.19    9.85 1189.18   16.08
 1473.98   12.97  1483.5     3.3 1511.85   -1.91 1521.24   -5.75 1612.08   -5.51
 1632.11   -2.62 1662.61   -5.46 1741.73   -4.26 1832.97   -7.52 1873.58   -4.01
  1981.4   -5.56 2123.01   -3.41 2153.71   -6.07 2194.44   -5.99 2378.74   -1.22
 2712.49    1.66 2864.45    1.25 2966.16   -2.26 3219.26      -1 3300.44    1.71
 3410.28     .36 3423.63    3.34 3437.62   14.78 3572.53   15.06 3622.49   20.43
#Mann= 3 , 0 , 0
  914.37    .055       0 1473.98   .0285       0 3437.62    .055       0
Levee=-1,1207.22,16.05,0,,,,
Bank Sta=1473.98,3437.62
XS Rating Curve= 0 ,0
Exp/Cntr(USF)=0.5,0.3
Exp/Cntr=0.3,0.1

Type RM Length L Ch R = 1 ,37189.66,843.23,1008.41,1150.62
XS GIS Cut Line= 2
359179.4351656125901755.21912747359414.2732619825900375.98532351
#Sta/Elev= 30
 1439.07    19.6 1454.06   14.65 1489.04   10.39 1558.99    9.85 1603.96    7.87
 1662.67    8.25 1669.03    3.31 1677.84    2.15 1688.12   -2.64 1809.45    -.44
 2063.59     .07 2174.82   -3.18 2265.79   -2.98 2285.66     .62  2316.4    -.77
 2326.42   -2.84 2366.79   -2.78 2498.76     .65 2559.72    -.66 2641.36    -.29
 2661.18   -1.33 2671.24   -3.16 2690.79    -2.7 2705.79    1.06 2732.86    2.41
 2749.49    7.03 2758.21   10.92 2793.19      15 2803.18   17.18 2838.16   20.68
#Mann= 3 , 0 , 0
 1439.07    .055       0 1662.67   .0285       0 2758.21    .055       0
Bank Sta=1662.67,2758.21
XS Rating Curve= 0 ,0
Exp/Cntr(USF)=0.5,0.3
Exp/Cntr=0.3,0.1

Type RM Length L Ch R = 1 ,35173.12,734.97,1009.92,1301.42
XS GIS Cut Line= 2
360995.0328001215902233.47744978361462.0506267375900995.49208828
#Sta/Elev= 30
 1193.34   20.02 1208.32   10.47  1223.3   11.48 1238.28   17.37 1248.27   19.36
 1263.24   17.51 1273.23   17.69 1283.22   11.87  1293.2    8.75  1368.1    6.47
 1373.09    5.32 1393.06    8.05 1418.03    8.11 1433.01    5.91 1450.19    4.94
 1453.47    3.05 1473.72     .87 1550.69     .16 1581.39   -1.63 1869.74   -2.95
 2018.55   -1.47 2068.51   -2.94 2112.78     .47    2157    6.12 2186.96    11.3
 2271.85   15.31 2311.79   14.89 2336.76   18.41 2411.65   18.75 2516.51   24.15
#Mann= 3 , 0 , 0
 1193.34    .055       0 1418.03   .0285       0 2186.96    .055       0
Levee=-1,1274.11,17.58,-1,2339.14,18.55,,
Bank Sta=1418.03,2186.96
XS Rating Curve= 0 ,0
Exp/Cntr(USF)=0.5,0.3
Exp/Cntr=0.3,0.1

Type RM Length L Ch R = 1 ,34163.2 ,971.99,970.31,998.23
XS GIS Cut Line= 2
361840.6306077325902567.25777953362409.2559906375901643.65944352
#Sta/Elev= 30
 1239.56   26.48 1252.61   13.03 1267.31    3.21 1272.39    2.38  1283.1   -1.28
 1303.62   -4.72 1404.38   -2.47 1423.55   -3.08  1453.6   -1.25    1565    -.89
 1736.52     1.6    1740     4.8    1915     4.8 1920.35    1.14 2068.78   -3.97
  2071.5   -1.75 2077.66   -2.36 2079.42     .65 2091.27    -.83 2096.72    2.18
 2100.31     .86 2105.39    3.67 2114.25    3.04 2134.25    6.03 2164.23    7.31
 2229.21   14.05  2279.2   16.99 2304.19   16.96 2314.18   18.42 2324.18   21.42
#Mann= 5 ,-1 , 0
 1239.56    .055       0 1272.39   .0285       0    1740    .035       0
 1920.35   .0285       0 2105.39    .055       0
Bank Sta=1272.39,2105.39
XS Rating Curve= 0 ,0
Exp/Cntr(USF)=0.5,0.3
Exp/Cntr=0.3,0.1

Type RM Length L Ch R = 1 ,33192.89,1234.76,1006.17,727.63
XS GIS Cut Line= 2
362630.6979425485903133.15579225363408.9064251195901869.13893486
#Sta/Elev= 30
 1099.53   16.66 1193.52       2 1196.11     4.6 1246.29     4.6 1308.13   -3.16
  1349.2   -3.52 1390.19   -2.07 1575.04    -.56 1683.15    -3.5 1726.98    -.25
 1802.73    1.66 1812.54     4.6 1863.37     4.6 1872.25     .88 1884.47    1.69
 1895.18    4.45 1939.17    4.08 1954.16    6.24 2034.12    7.27  2079.1    6.59
 2096.62    2.79 2111.88    1.09 2201.93    -.08 2241.36    2.09 2264.03    5.45
 2363.98    6.08 2418.96   10.35 2503.92   13.76 2513.92   16.41 2583.89   20.76
#Mann= 4 ,-1 , 0
 1099.53    .024       0 1884.47    .035       0 2111.88   .0285       0
 2264.03    .055       0
Bank Sta=1099.53,2264.03
XS Rating Curve= 0 ,0
Exp/Cntr(USF)=0.5,0.3
Exp/Cntr=0.3,0.1

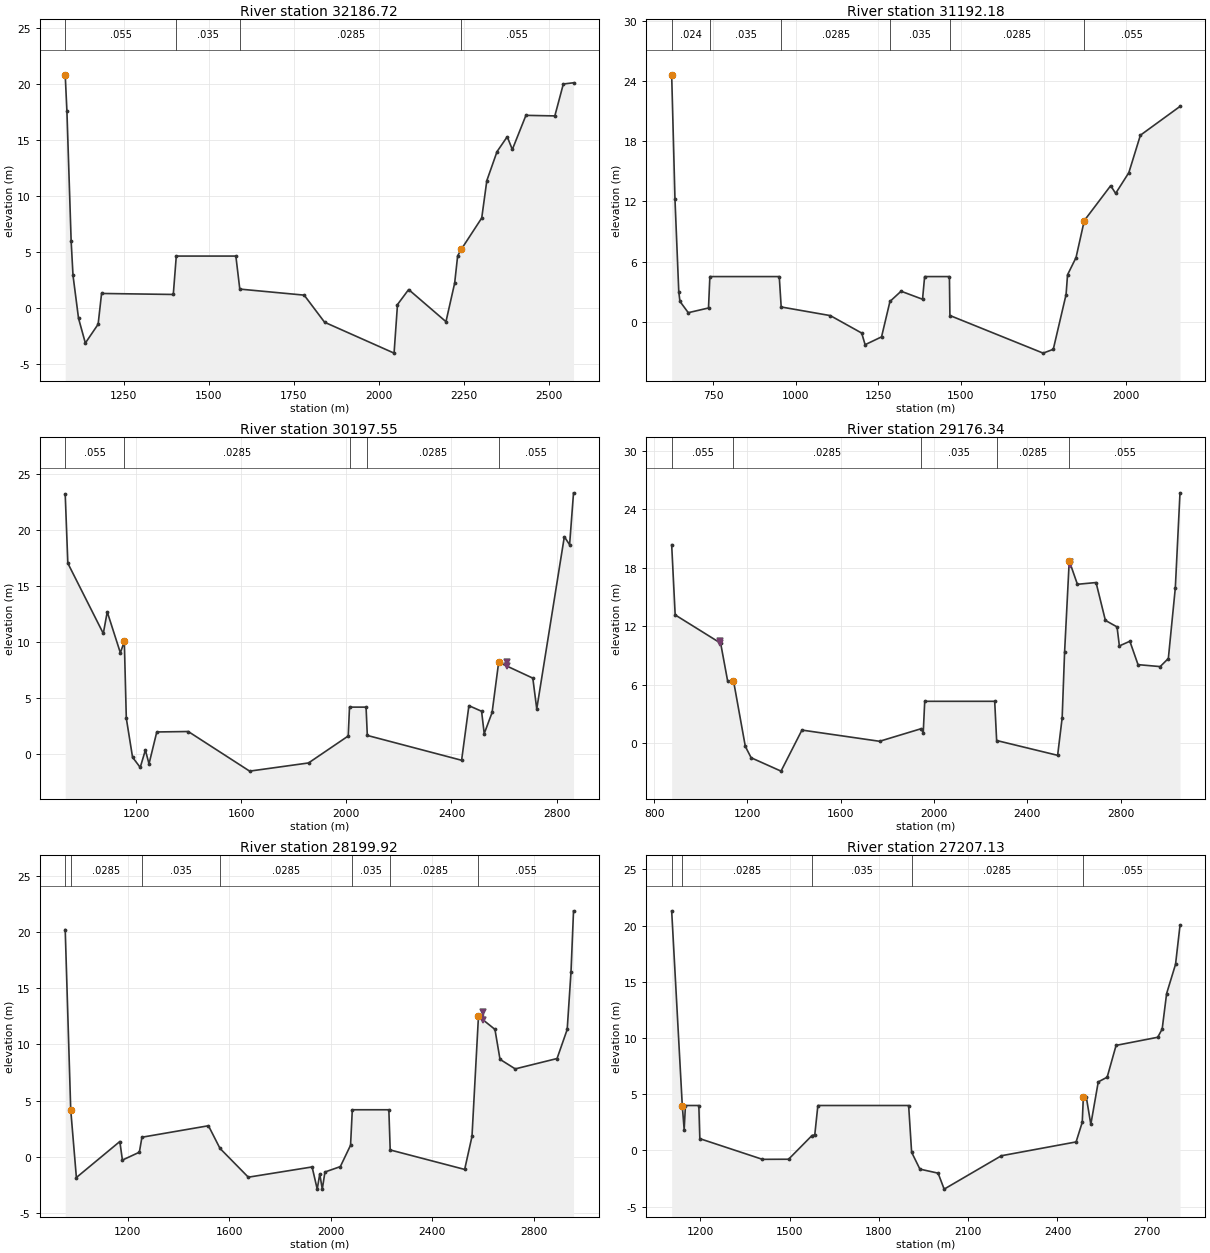
Type RM Length L Ch R = 1 ,32186.72,1219.67,994.54,671.77
XS GIS Cut Line= 2
 363631.709871595903578.71580343364207.1422299995902200.81437446
#Sta/Elev= 30
 1078.71   20.79 1083.71   17.56 1096.16    5.94 1101.62    2.87 1117.85    -.96
 1137.88   -3.17 1175.41   -1.49 1185.54    1.26 1396.22    1.17    1405     4.6
    1580     4.6 1591.57    1.65 1780.72    1.11  1840.6   -1.31 2044.77   -4.07
  2054.8     .27 2087.54    1.61 2197.18   -1.26 2222.78    2.19 2231.52    4.62
 2242.33    5.21 2302.25       8 2317.24   11.34  2347.2   13.93 2377.17   15.26
 2392.15   14.12  2432.1   17.17    2517   17.12 2541.97   19.97 2571.93   20.08
#Mann= 4 ,-1 , 0
 1078.71    .055       0    1405    .035       0 1591.57   .0285       0
 2242.33    .055       0
Bank Sta=1078.71,2242.33
XS Rating Curve= 0 ,0
Exp/Cntr(USF)=0.5,0.3
Exp/Cntr=0.3,0.1

Type RM Length L Ch R = 1 ,31192.18,1034.11,994.63,993.08
XS GIS Cut Line= 2
364659.094328575 5903964.7554875364993.4189005785902463.03305586
#Sta/Elev= 30
  624.39   24.61  634.38    12.2  645.88    2.99   649.4    2.03  674.61      .9
  735.88    1.37     740     4.5     950     4.5  955.84    1.47 1104.56     .61
 1199.53   -1.13 1209.85   -2.29  1259.6   -1.51 1285.02    2.02 1318.71    3.04
 1383.65    2.24    1390     4.5    1465     4.5 1466.49     .62 1748.66   -3.13
 1779.35   -2.75  1818.1    2.71 1822.53    4.68 1848.19    6.39 1873.17   10.08
 1953.09   13.56 1968.08   12.79 2008.04   14.86    2043   18.59 2162.88   21.46
#Mann= 6 ,-1 , 0
  624.39    .024       0     740    .035       0  955.84   .0285       0
 1285.02    .035       0 1466.49   .0285       0 1873.17    .055       0
Bank Sta=624.39,1873.17
XS Rating Curve= 0 ,0
Exp/Cntr(USF)=0.5,0.3
Exp/Cntr=0.3,0.1

Type RM Length L Ch R = 1 ,30197.55,1025.02,1021.21,1018.34
XS GIS Cut Line= 2
 365584.825019185904376.40324965366005.2681428385902487.85265764
#Sta/Elev= 30
  929.89   23.25  939.89   17.06 1074.88   10.78 1089.88   12.71 1139.87    9.05
 1154.87   10.07 1162.47     3.2 1186.24    -.28 1215.43   -1.19 1235.04     .36
 1248.87    -.87 1278.44    1.98 1398.24    2.02 1631.86   -1.52 1855.94    -.79
 2007.11    1.62    2012     4.2    2075     4.2 2079.76    1.67 2438.66    -.55
 2466.46    4.33 2514.71    3.83 2524.71    1.83 2554.71    3.72  2579.7    8.21
 2709.69    6.79 2724.69    4.04 2829.68   19.43 2849.67   18.71 2864.67   23.35
#Mann= 5 ,-1 , 0
  929.89    .055       0 1154.87   .0285       0    2012    .035       0
 2079.76   .0285       0  2579.7    .055       0
Levee=-1,920.97,25.37,-1,2611.08,8.23,,
Bank Sta=1154.87,2579.7
XS Rating Curve= 0 ,0
Exp/Cntr(USF)=0.5,0.3
Exp/Cntr=0.3,0.1

Type RM Length L Ch R = 1 ,29176.34,1138.34,976.42,790.73
XS GIS Cut Line= 2
366575.0504711595904614.59656991367048.7107041215902487.00490546
#Sta/Elev= 30
  874.87   20.36  889.87   13.16 1084.84   10.26 1114.84    6.38 1139.83    6.43
 1190.71    -.33 1215.73   -1.49 1343.76   -2.86 1433.44    1.35 1766.38      .2
 1944.53    1.49 1953.58    1.09    1960     4.3    2260     4.3 2268.33     .28
 2529.83   -1.24 2549.24     2.6 2559.62    9.31 2579.62   18.71 2614.62    16.3
  2694.6   16.48  2734.6    12.6 2784.59   11.93 2794.59    9.98 2839.58   10.46
 2874.58    8.06 2969.56    7.86 3004.56    8.69 3034.56   15.95 3054.55   25.68
#Mann= 5 ,-1 , 0
  874.87    .055       0 1139.83   .0285       0 1944.53    .035       0
 2268.33   .0285       0 2579.62    .055       0
Levee=-1,1080.27,10.49,-1,2581.21,18.28,,
Bank Sta=1139.83,2579.62
XS Rating Curve= 0 ,0
Exp/Cntr(USF)=0.5,0.3
Exp/Cntr=0.3,0.1

Type RM Length L Ch R = 1 ,28199.92,995.41,992.79,993.66
XS GIS Cut Line= 2
367655.3898128915904687.76428615367869.613936821  5902696.538264
#Sta/Elev= 30
   953.9    20.2  975.63     4.2  997.91   -1.82 1169.13    1.38 1179.25    -.27
 1246.03     .43 1256.19    1.76 1518.25    2.78 1563.64     .77 1675.29   -1.79
 1926.58    -.88 1946.78   -2.85 1956.78    -1.5 1966.78   -2.85 1977.19   -1.33
 2037.83    -.85 2078.12    1.05    2085     4.2    2229     4.2 2234.28     .63
 2527.66    -1.1 2556.52    1.83 2582.03   12.51 2646.95   11.34 2666.93    8.68
 2726.86    7.83 2891.66    8.75 2931.62   11.33  2946.6   16.44 2956.59   21.87
#Mann= 7 ,-1 , 0
   953.9    .055       0  975.63   .0285       0 1256.19    .035       0
 1563.64   .0285       0    2085    .035       0 2234.28   .0285       0
 2582.03    .055       0
Levee=0,,,-1,2598.63,12.92,,
Bank Sta=975.63,2582.03
XS Rating Curve= 0 ,0
Exp/Cntr(USF)=0.5,0.3
Exp/Cntr=0.3,0.1

Type RM Length L Ch R = 1 ,27207.13,1086.67,1005.59,915.85
XS GIS Cut Line= 2
 368658.787946125904640.07015667368841.4941561275902941.80450296
#Sta/Elev= 30
 1103.75   21.32 1139.49    3.95 1145.74    1.86    1150       4    1195       4
 1198.36    1.05 1408.78    -.79  1496.6    -.78 1575.28    1.33  1584.6    1.39
    1595       4    1900       4 1910.04    -.16 1937.86   -1.66 1999.01   -2.02
 2019.36   -3.44  2211.6    -.47 2462.69     .76  2483.4    2.51 2486.99    4.74
 2497.17    4.72 2512.16    2.32 2537.13     6.1  2567.1    6.52 2597.06    9.35
  2736.9   10.07 2751.89    10.8 2766.87   13.96 2796.84   16.56 2811.82   20.02
#Mann= 5 ,-1 , 0
 1103.75    .055       0 1139.49   .0285       0 1575.28    .035       0
 1910.04   .0285       0 2486.99    .055       0
Bank Sta=1139.49,2486.99
XS Rating Curve= 0 ,0
Exp/Cntr(USF)=0.5,0.3
Exp/Cntr=0.3,0.1

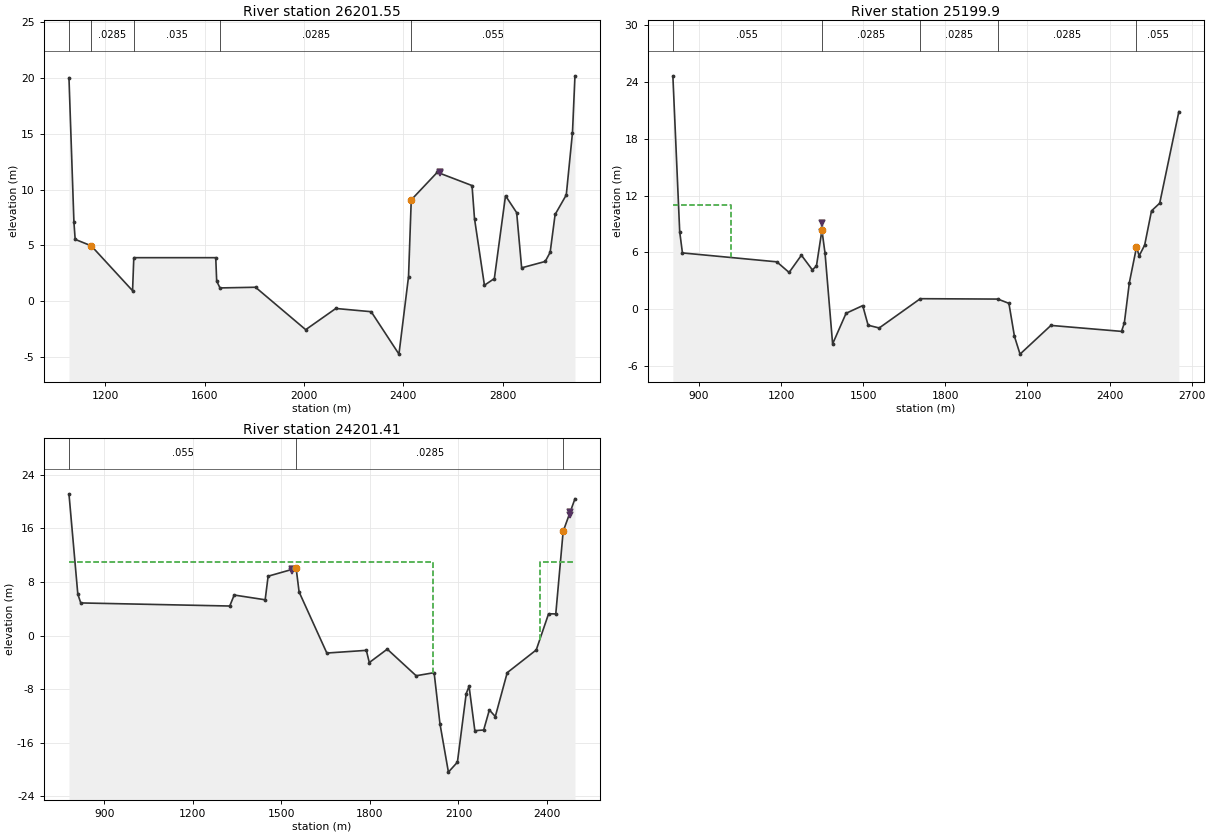
Type RM Length L Ch R = 1 ,26201.55,1068.28,1001.65,945.48
XS GIS Cut Line= 2
369693.6218208885904800.33809111369798.5638235755902765.25934895
#Sta/Elev= 30
 1053.86   20.02 1073.83    7.09 1078.83    5.54 1143.76    4.96    1310     .94
    1315     3.9    1645     3.9 1648.78     1.8 1662.12    1.19 1805.22    1.25
 2007.26   -2.55 2128.61    -.65 2271.01    -.94  2382.8   -4.74 2421.41    2.21
 2432.36    9.08 2537.25   11.55  2677.1   10.36 2687.08     7.4 2727.04    1.43
    2767    2.03 2811.95    9.45  2856.9    7.93 2876.88    2.99 2971.78    3.56
 2991.76    4.38 3011.74    7.77 3056.69    9.52 3081.66    15.1 3091.65   20.19
#Mann= 5 ,-1 , 0
 1053.86    .055       0 1143.76   .0285       0    1315    .035       0
 1662.12   .0285       0 2432.36    .055       0
Levee=0,,,-1,2548.85,11.54,,
Bank Sta=1143.76,2432.36
XS Rating Curve= 0 ,0
Exp/Cntr(USF)=0.5,0.3
Exp/Cntr=0.3,0.1

Type RM Length L Ch R = 1 ,25199.9 ,1065.31,998.49,975.09
XS GIS Cut Line= 2
370718.7755874455905151.77759483370740.4105410685903303.20609274
#Sta/Elev= 30
  804.43   24.63  829.41    8.17   839.4    5.94 1184.16       5 1229.12    3.88
 1274.09     5.7 1314.06    4.15 1329.05    4.57 1349.04    8.34 1360.51    5.88
 1388.08   -3.66 1437.24    -.43 1498.09     .38 1517.74   -1.69 1558.29   -1.98
 1708.49    1.11 1991.75    1.07 2032.18     .62 2052.44   -2.87 2072.87   -4.74
 2185.69   -1.71 2443.79   -2.34 2454.04   -1.42 2472.27    2.81 2498.22    6.52
 2508.21    5.64  2528.2    6.77 2553.18   10.38 2583.16   11.19 2653.11   20.85
#Mann= 5 ,-1 , 0
  804.43    .055       0 1349.04   .0285       0 1708.49   .0285       0
 1991.75   .0285       0 2498.22    .055       0
Levee=-1,1347.83,9.11,0,,,,
#XS Ineff= 2 , 0
       0  1016.5      11               0
Permanent Ineff=
       F       F
Bank Sta=1349.04,2498.22
XS Rating Curve= 0 ,0
Exp/Cntr(USF)=0.5,0.3
Exp/Cntr=0.3,0.1

Type RM Length L Ch R = 1 ,24201.41,139.37,137.37,138.3
XS GIS Cut Line= 2
371755.4124039625905315.34396905371721.1203393415903600.74243302
#Sta/Elev= 30
  779.98   21.17  809.97    6.19  819.97    4.88 1324.96    4.42 1339.96    6.06
 1444.95    5.35 1454.95    8.87 1549.95   10.06 1559.95    6.52 1653.94    -2.6
  1787.9    -2.2  1797.9   -4.02  1858.7   -2.02 1956.68   -5.99 2017.59   -5.53
 2037.37  -13.16 2066.03  -20.38 2096.55  -18.89 2126.27   -8.67 2136.02   -7.56
 2155.63  -14.19 2185.55  -14.09 2204.82   -11.1 2224.98  -12.08 2265.34   -5.53
 2363.69   -2.14 2405.55    3.26 2429.92    3.24 2454.92   15.56 2494.92   20.43
#Mann= 3 , 0 , 0
  779.98    .055       0 1549.95   .0285       0 2454.92    .055       0
Levee=-1,1535.47,9.67,-1,2478.53,18.01,,
#XS Ineff= 2 , 0
       0    2015      11    2375       0      11
Permanent Ineff=
       F       F
Bank Sta=1549.95,2454.92
XS Rating Curve= 0 ,0
Exp/Cntr(USF)=0.5,0.3
Exp/Cntr=0.3,0.1