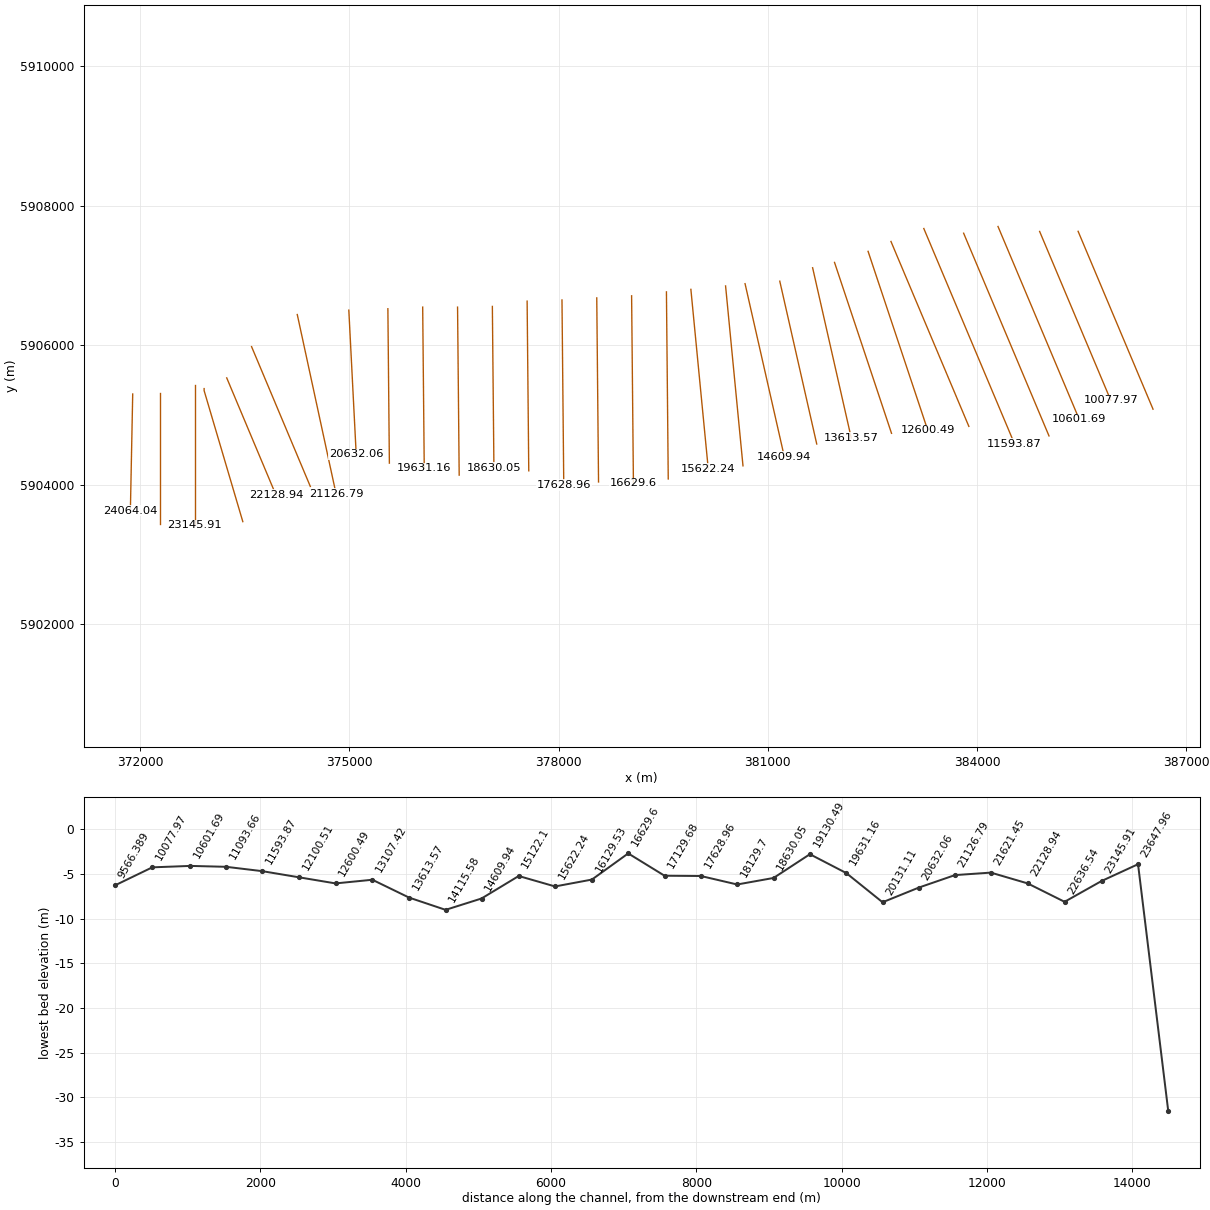
HEC-RAS study Churchill_Forecasting.prj: ChurchillRiver_Forecasting

--- Churchill_Forecasting.g14 (geometry) --- (continued)

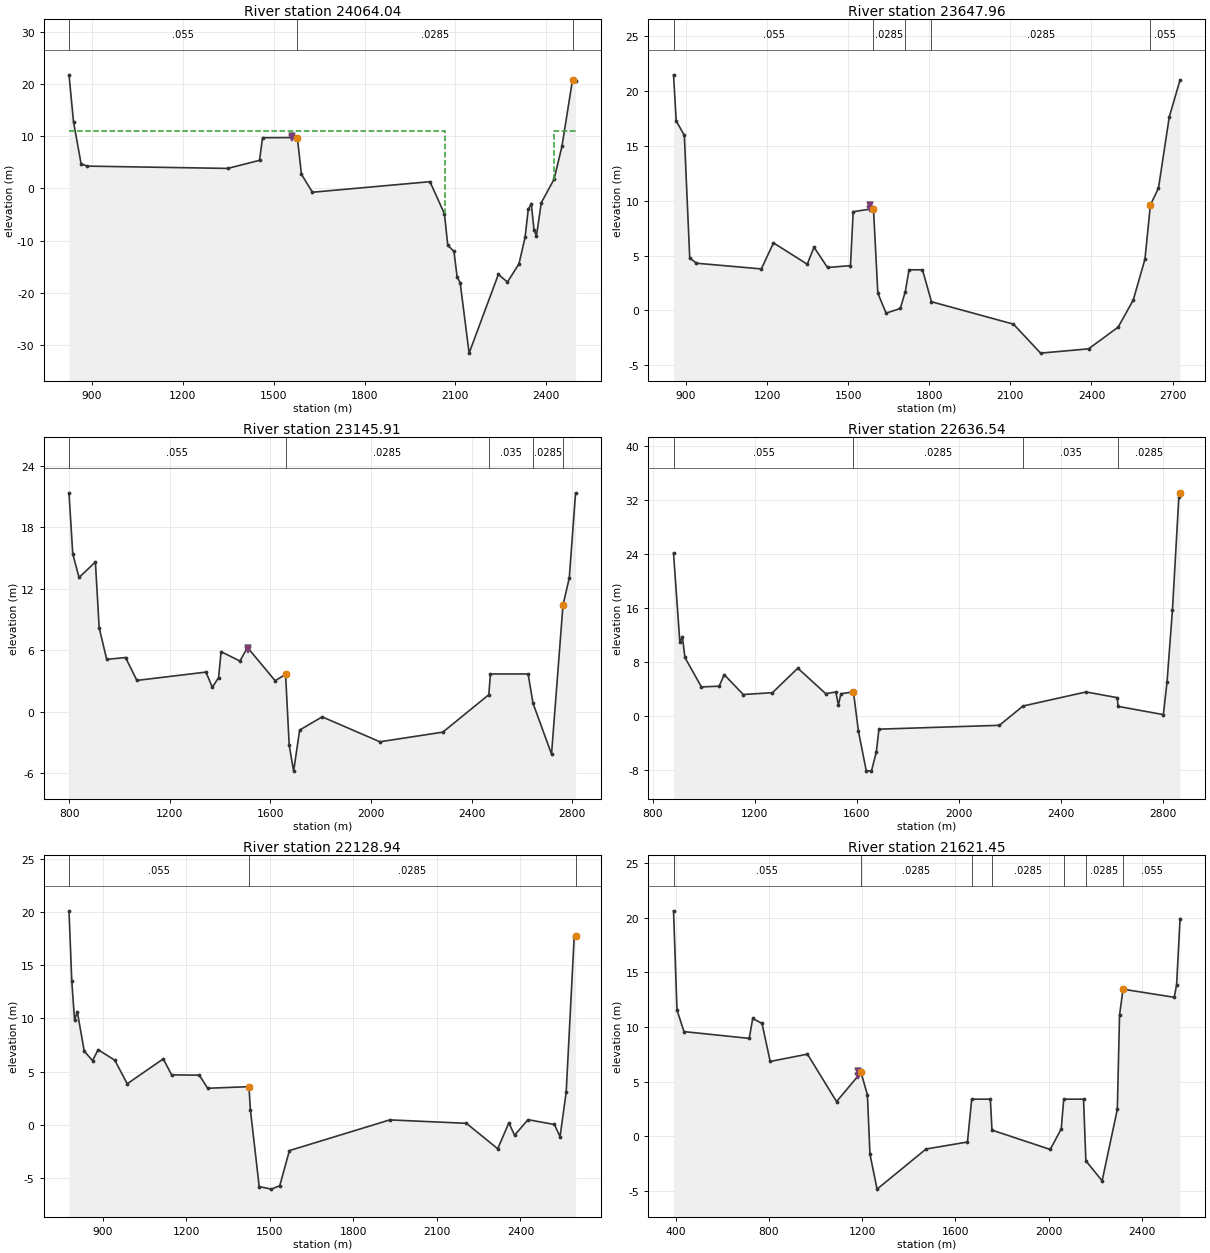
Type RM Length L Ch R = 1 ,24064.04,382.78,416.08,439.98
XS GIS Cut Line= 2
371892.4654726395905298.67045102371859.012873567 5903626.0427694
#Sta/Elev= 30
     824   21.71  838.98   12.71  863.95    4.69  883.93    4.24 1348.36     3.8
 1453.23    5.35 1463.22    9.68 1578.08     9.7 1591.72    2.68 1627.89    -.76
 2016.08    1.26    2064   -4.89 2074.88   -10.9 2095.38  -12.09 2105.74  -16.97
  2115.9  -18.07 2145.42  -31.55 2242.07  -16.48    2272  -17.95 2310.14  -14.46
 2330.35   -9.37 2340.73   -4.01 2350.89   -3.02 2359.92   -8.04 2367.92   -9.09
 2383.75   -2.76 2425.77     1.7 2452.02    8.01 2486.98    20.8 2496.96   20.51
#Mann= 3 , 0 , 0
     824    .055       0 1578.08   .0285       0 2486.98    .055       0
Levee=-1,1561.61,10.08,0,,,,
#XS Ineff= 2 , 0
       0    2065      11    2425       0      11
Permanent Ineff=
       F       F
Bank Sta=1578.08,2486.98
XS Rating Curve= 0 ,0
Exp/Cntr(USF)=0.5,0.3
Exp/Cntr=0.3,0.1

Type RM Length L Ch R = 1 ,23647.96,505.71,502.05,500
XS GIS Cut Line= 2
     372282.06125905313.54542197     372282.06125903440.10480742
#Sta/Elev= 30
  854.29   21.46  864.28   17.26  894.26   15.95  914.24    4.78  939.22     4.3
 1179.02    3.78 1223.98    6.15 1348.88    4.21 1373.86    5.76 1423.82    3.91
 1508.75    4.08 1518.74    8.99 1593.68    9.28 1609.95    1.57 1640.47    -.25
 1693.16     .18 1711.32     1.7 1725.24     3.7    1775     3.7 1808.29     .79
 2111.44   -1.25 2211.82   -3.89 2389.29    -3.5 2498.71   -1.52 2554.27     .93
 2597.84    4.67 2617.83    9.59  2647.8   11.14 2687.77   17.63 2727.73      21
#Mann= 5 ,-1 , 0
  854.29    .055       0 1593.68   .0285       0 1711.32    .035       0
 1808.29   .0285       0 2617.83    .055       0
Levee=-1,1580.58,9.6,0,,,,
Bank Sta=1593.68,2617.83
XS Rating Curve= 0 ,0
Exp/Cntr(USF)=0.5,0.3
Exp/Cntr=0.3,0.1

Type RM Length L Ch R = 1 ,23145.91,131.3,509.36,874.95
XS GIS Cut Line= 2
     372782.06125905431.07412441     372782.06125903417.07729258
#Sta/Elev= 30
   799.6   21.35   814.6   15.39  839.59    13.1  904.55   14.61  919.55     8.2
  949.53    5.12 1024.49     5.3 1069.47    3.07 1344.34    3.88 1369.33     2.4
 1394.31    3.34 1404.31    5.87 1479.27    4.96 1509.26    6.28  1619.2    3.04
 1660.71    3.66 1675.14   -3.25 1692.71   -5.77 1716.64   -1.77 1806.09    -.48
 2035.59   -2.91 2285.98   -1.97 2468.83    1.68    2475     3.7    2625     3.7
 2644.58     .83 2718.07   -4.11 2763.64   10.41 2788.63   13.05 2813.61   21.34
#Mann= 5 ,-1 , 0
   799.6    .055       0 1660.71   .0285       0 2468.83    .035       0
 2644.58   .0285       0 2763.64    .055       0
Levee=-1,1510.89,6.06,0,,,,
Bank Sta=1660.71,2763.64
XS Rating Curve= 0 ,0
Exp/Cntr(USF)=0.5,0.3
Exp/Cntr=0.3,0.1

Type RM Length L Ch R = 1 ,22636.54,243.38,507.6,678.94
XS GIS Cut Line= 4
372916.4242078555905376.27542926     372916.6397     5905346.413
     373087.2052     5904768.912373471.271045858 5903468.5408028
#Sta/Elev= 30
  880.88   24.09  905.77   10.93  915.72   11.74  925.67    8.69  990.37    4.34
 1060.04    4.45 1079.95    6.15  1154.6    3.22 1269.06    3.49 1368.59    7.11
 1478.07    3.35 1517.89    3.59 1527.86    1.66 1537.83    3.34 1586.97     3.6
 1606.58   -2.22 1637.13   -8.02 1657.57    -8.1 1676.97   -5.22 1686.98    -1.9
 2159.79   -1.33 2252.46    1.52    2500     3.6 2622.79    2.75 2625.08    1.47
 2803.23     .25 2817.65    5.09 2838.89   15.76 2863.82   32.34  2868.8   33.02
#Mann= 4 ,-1 , 0
  880.88    .055       0 1586.97   .0285       0 2252.46    .035       0
 2625.08   .0285       0
Bank Sta=1586.97,2868.8
XS Rating Curve= 0 ,0
Exp/Cntr(USF)=0.5,0.3
Exp/Cntr=0.3,0.1

Type RM Length L Ch R = 1 ,22128.94,396.14,507.49,502.51
XS GIS Cut Line= 3
373240.6307513125905529.90934562     373431.5829    5905075.4949
373945.2745325865903853.04771136
#Sta/Elev= 30
  778.94   20.09   788.9   13.52  798.86    9.84  808.82   10.62  833.71    6.91
  863.58    6.02   883.5    7.05  943.25    6.07  988.05    3.85  1117.5    6.19
 1147.38    4.69 1246.95    4.66 1276.83    3.43 1425.21    3.58 1430.28     1.4
 1461.91    -5.8 1505.84   -6.04 1535.65   -5.72 1570.49   -2.42  1930.8     .46
 2205.89     .14 2318.46   -2.25 2358.41     .19 2378.68    -.98 2427.21     .48
 2521.75     .03 2542.19   -1.11 2564.25    3.09 2592.85   17.62 2597.83   17.77
#Mann= 3 , 0 , 0
  778.94    .055       0 1425.21   .0285       0 2597.83    .055       0
Bank Sta=1425.21,2597.83
XS Rating Curve= 0 ,0
Exp/Cntr(USF)=0.5,0.3
Exp/Cntr=0.3,0.1

Type RM Length L Ch R = 1 ,21621.45,766.04,494.66,174.79
XS GIS Cut Line= 2
373596.8752581445905977.88533643374439.3020494875903973.13768515
#Sta/Elev= 30
  389.92   20.63  404.92   11.54  434.91    9.58  714.86    8.96  729.85   10.78
  769.85   10.33  804.84    6.85  964.81    7.52 1089.78    3.18 1194.76    5.84
 1222.12    3.81 1233.22   -1.64 1263.68   -4.83    1474   -1.16 1651.68    -.52
    1670     3.4    1750     3.4    1757     .57 2006.95    -1.2 2054.33     .68
    2065     3.4    2150     3.4 2160.08   -2.24 2229.83   -4.07 2295.08    2.47
 2304.54   11.08 2319.53   13.46 2539.49   12.72 2549.49   13.87 2564.48   19.92
#Mann= 7 ,-1 , 0
  389.92    .055       0 1194.76   .0285       0    1670    .035       0
    1757   .0285       0    2065    .035       0 2160.08   .0285       0
 2319.53    .055       0
Levee=-1,1182.33,6.02,0,,,,
Bank Sta=1194.76,2319.53
XS Rating Curve= 0 ,0
Exp/Cntr(USF)=0.5,0.3
Exp/Cntr=0.3,0.1

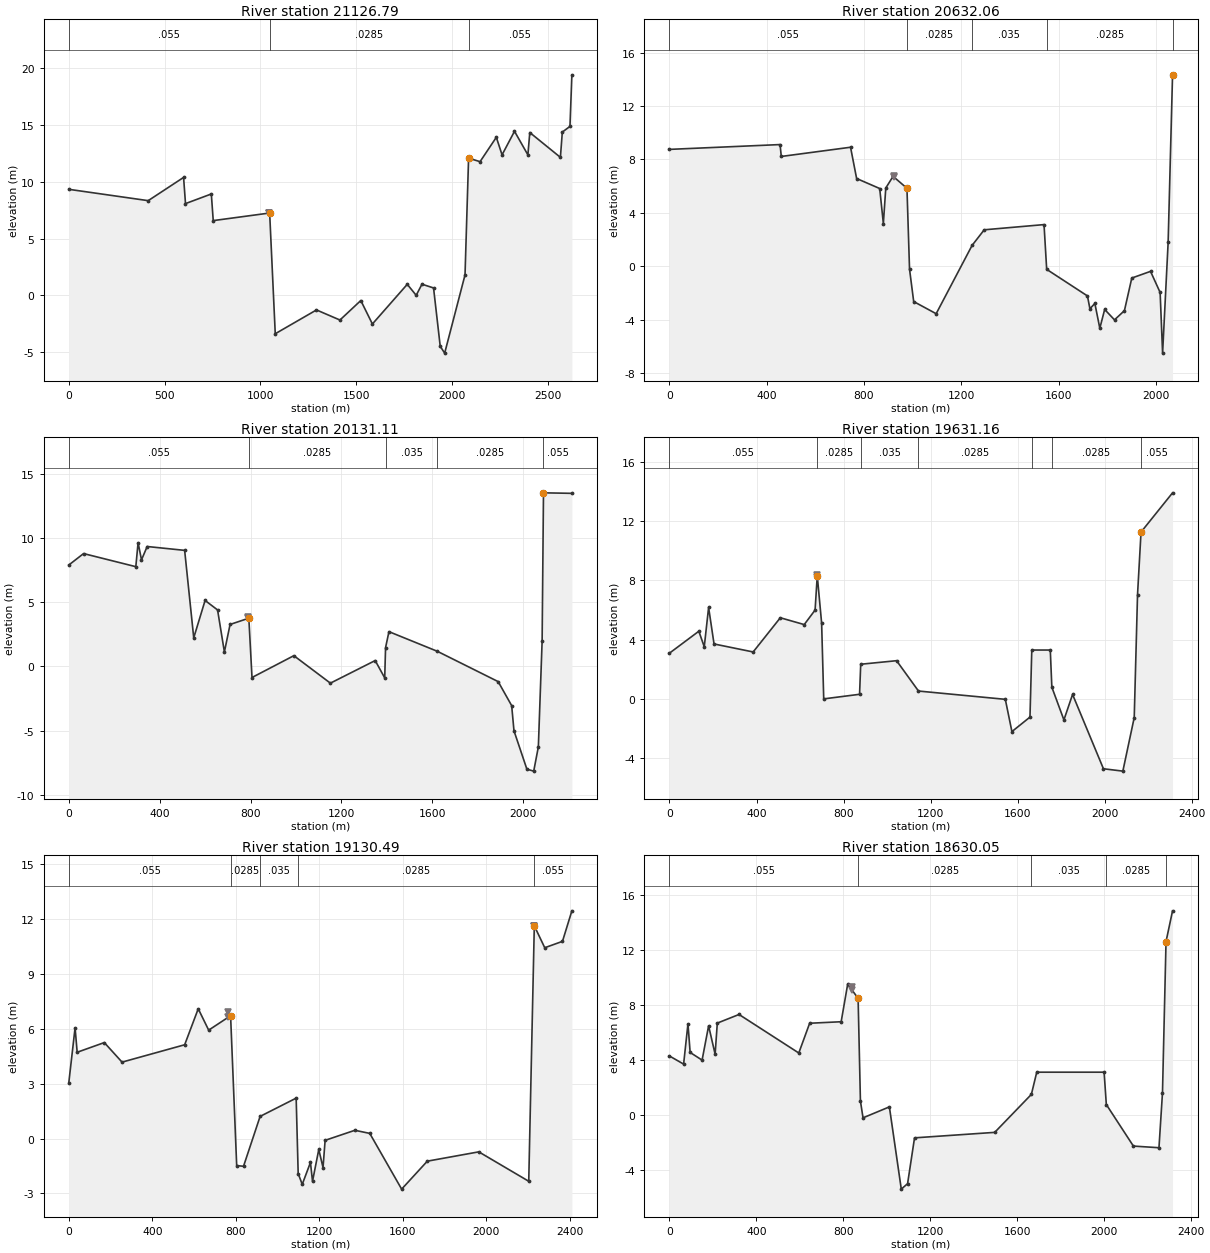
Type RM Length L Ch R = 1 ,21126.79,703.23,494.73,214.27
XS GIS Cut Line= 2
     374252.2828    5906438.1996 374807.811066495903870.93978839
#Sta/Elev= 30
       0    9.34  414.48    8.34  599.24   10.39  609.23    8.08  744.06    8.93
  754.05    6.58 1048.67    7.25 1077.89    -3.4 1293.16    -1.3 1415.66   -2.19
 1524.56    -.47 1585.12   -2.54 1767.15     .96 1813.76    -.01 1843.93     .97
 1904.42     .64 1939.28   -4.51 1962.48   -5.11 2068.74    1.79 2087.36   12.09
 2147.28   11.78 2232.18   13.93 2262.14   12.38 2327.06   14.46 2396.97   12.38
 2406.95   14.35 2566.75   12.16 2576.74   14.39 2616.69   14.89 2626.67   19.44
#Mann= 3 , 0 , 0
       0    .055       0 1048.67   .0285       0 2087.36    .055       0
Levee=-1,1047.6,7.25,0,,,,
Bank Sta=1048.67,2087.36
XS Rating Curve= 0 ,0
Exp/Cntr(USF)=0.5,0.3
Exp/Cntr=0.3,0.1

Type RM Length L Ch R = 1 ,20632.06,553.47,500.95,431.9
XS GIS Cut Line= 2
     374991.4999    5906501.4228 375097.32182344 5904435.6962342
#Sta/Elev= 30
       0    8.75  454.66    9.11  459.66    8.22  744.44    8.91  769.42    6.57
  864.35    5.82  879.34     3.2  889.33    5.86  919.31    6.73  976.39    5.84
  986.99    -.22 1004.09   -2.64 1096.46   -3.55 1244.07    1.56 1294.03    2.73
    1540    3.12  1550.9    -.23 1718.55   -2.22 1728.63   -3.18    1749   -2.78
 1769.37   -4.64 1789.32   -3.23 1829.76   -4.01 1870.57   -3.32 1900.85    -.88
 1977.94    -.38 2017.35   -1.96 2027.51    -6.5 2050.31    1.79 2068.45   14.33
#Mann= 5 ,-1 , 0
       0    .055       0  976.39   .0285       0 1244.07    .035       0
  1550.9   .0285       0 2068.45    .055       0
Levee=-1,921.28,6.75,0,,,,
Bank Sta=976.39,2068.45
XS Rating Curve= 0 ,0
Exp/Cntr(USF)=0.5,0.3
Exp/Cntr=0.3,0.1

Type RM Length L Ch R = 1 ,20131.11,499.39,499.95,502.28
XS GIS Cut Line= 2
     375551.6424    5906521.4517375573.0191005335904307.35535739
#Sta/Elev= 30
       0     7.9   64.98    8.79  294.89    7.77  304.89    9.64  319.88     8.3
  344.87    9.34  509.81    9.04   549.8    2.23  599.78    5.14  654.76     4.4
  684.75    1.13  709.74    3.27  792.33    3.76  806.26    -.86  990.52     .84
 1151.27    -1.3 1348.47     .46 1390.41    -.89 1394.16    1.47 1409.06    2.71
 1622.04    1.18 1889.71   -1.18 1949.18   -3.05 1959.34   -5.01 2016.18      -8
 2046.25   -8.15 2066.62   -6.26 2083.22    1.97 2089.23   13.52 2214.18   13.48
#Mann= 5 ,-1 , 0
       0    .055       0  792.33   .0285       0 1394.16    .035       0
 1622.04   .0285       0 2089.23    .055       0
Levee=-1,789.71,3.85,0,,,,
Bank Sta=792.33,2089.23
XS Rating Curve= 0 ,0
Exp/Cntr(USF)=0.5,0.3
Exp/Cntr=0.3,0.1

Type RM Length L Ch R = 1 ,19631.16,500,500.67,502.47
XS GIS Cut Line= 2
     376050.8276    5906544.7603 376073.147579075904232.96529177
#Sta/Elev= 30
       0    3.09  134.82    4.57  159.79    3.52  179.76    6.18  204.73    3.71
  384.49    3.17  509.32    5.48  619.17    5.02   669.1       6  679.09    8.32
  699.15    5.12   708.8       0  873.51     .31  878.82    2.34  1043.6    2.58
 1144.33     .53 1543.37    -.03 1573.65   -2.21 1656.69   -1.23    1665     3.3
    1750     3.3  1757.2     .79 1812.65   -1.42 1852.44      .3 1994.27   -4.72
 2083.53   -4.88  2135.8   -1.26    2151    7.05  2167.1   11.27 2311.91   13.92
#Mann= 7 ,-1 , 0
       0    .055       0  679.09   .0285       0  878.82    .035       0
 1144.33   .0285       0    1665    .035       0  1757.2   .0285       0
  2167.1    .055       0
Levee=-1,679.53,8.39,0,,,,
Bank Sta=679.09,2167.1
XS Rating Curve= 0 ,0
Exp/Cntr(USF)=0.5,0.3
Exp/Cntr=0.3,0.1

Type RM Length L Ch R = 1 ,19130.49,499.21,500.44,499.99
XS GIS Cut Line= 2
     376550.8517    5906544.6705376574.1121869635904135.46357957
#Sta/Elev= 30
       0    3.06   29.99    6.06   39.99    4.72  169.95    5.25  254.93    4.18
  554.84    5.13  619.82     7.1  669.81    5.93  774.78    6.72  803.99   -1.48
  836.72   -1.52  916.14    1.21 1088.83    2.21 1098.51   -1.92 1117.95   -2.51
 1157.24   -1.31 1167.17   -2.34 1197.14     -.6 1217.48   -1.59 1227.52     -.1
 1369.98     .45 1441.29     .28 1593.99   -2.77 1716.95   -1.24 1963.51    -.73
 2202.71   -2.34 2229.37   11.64 2279.35   10.44 2364.33   10.79 2409.31   12.46
#Mann= 5 ,-1 , 0
       0    .055       0  774.78   .0285       0  916.14    .035       0
 1098.51   .0285       0 2229.37    .055       0
Levee=-1,764.47,6.93,-1,2230.24,11.65,,
Bank Sta=774.78,2229.37
XS Rating Curve= 0 ,0
Exp/Cntr(USF)=0.5,0.3
Exp/Cntr=0.3,0.1

Type RM Length L Ch R = 1 ,18630.05,499.27,500.35,499.48
XS GIS Cut Line= 2
     377049.9631    5906554.4619377072.3123497025904239.62897053
#Sta/Elev= 30
       0    4.28      65    3.69      85    6.63      95    4.54     150    3.98
     180    6.48  209.99    4.41  219.99    6.68  319.99    7.31  594.99     4.5
  644.98    6.67  789.98    6.78  819.98    9.52  867.93    8.49  878.61       1
  890.58    -.23 1011.88     .57 1066.66   -5.43 1095.67   -5.03 1127.61   -1.69
 1496.55   -1.29 1665.28    1.48    1690     3.1    2000     3.1 2010.17     .74
 2134.75   -2.29 2252.45   -2.41 2268.63     1.6 2284.94   12.63 2314.94   14.87
#Mann= 5 ,-1 , 0
       0    .055       0  867.93   .0285       0 1665.28    .035       0
 2010.17   .0285       0 2284.94    .055       0
Levee=-1,840.7,9.28,-1,2315.18,14.78,,
Bank Sta=867.93,2284.94
XS Rating Curve= 0 ,0
Exp/Cntr(USF)=0.5,0.3
Exp/Cntr=0.3,0.1

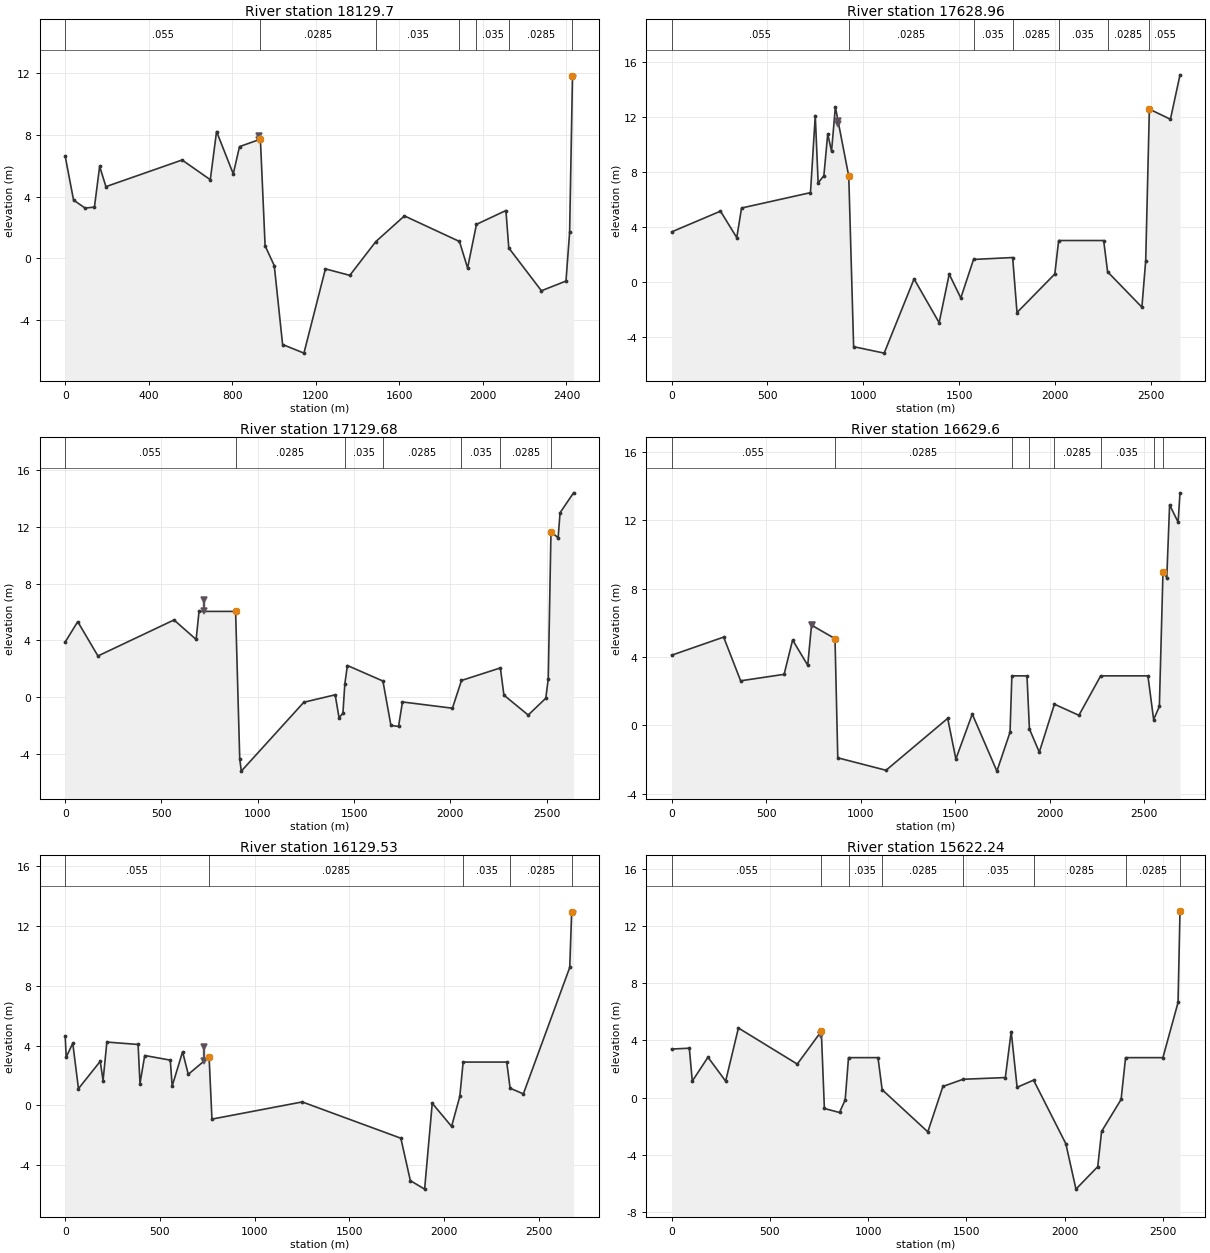
Type RM Length L Ch R = 1 ,18129.7 ,500.09,500.74,500.29
XS GIS Cut Line= 2
     377548.4327    5906630.7123377571.9285976455904197.11987968
#Sta/Elev= 30
       0    6.62   39.98    3.78   94.95    3.26  139.93    3.32  164.91    5.97
   194.9    4.65   559.7    6.38  694.63     5.1  724.61    8.23  804.57    5.48
  834.55    7.25   934.5    7.73  957.07     .81 1000.93    -.48 1040.81    -5.6
 1142.98   -6.16 1245.83    -.69 1362.59   -1.11 1486.97    1.08 1624.13    2.75
 1887.51    1.09 1926.48    -.63 1968.94     2.2    2110     3.1 2123.73     .67
 2279.93   -2.11 2397.59   -1.48 2414.96    1.69  2428.7   11.82  2433.7   11.91
#Mann= 7 ,-1 , 0
       0    .055       0   934.5   .0285       0 1486.97    .035       0
 1887.51   .0285       0 1968.94    .035       0 2123.73   .0285       0
  2428.7    .055       0
Levee=-1,927.82,7.91,0,,,,
Bank Sta=934.5,2428.7
XS Rating Curve= 0 ,0
Exp/Cntr(USF)=0.5,0.3
Exp/Cntr=0.3,0.1

Type RM Length L Ch R = 1 ,17628.96,499.07,499.28,499.22
XS GIS Cut Line= 2
     378048.2954    5906647.3491378073.9129169475903994.00978334
#Sta/Elev= 30
       0    3.63  254.85    5.14   339.8    3.21  364.79    5.37  724.58    6.49
  749.56   12.11  764.56     7.2  794.54    7.73  814.53   10.77  834.51    9.51
   854.5   12.73  924.46    7.68  949.78   -4.74 1109.22   -5.21 1265.31      .2
 1396.14   -2.99 1448.73     .55 1509.21   -1.19 1575.77    1.62 1779.93    1.76
 1802.66   -2.25 2000.01     .56    2020       3    2255       3 2275.54     .72
 2454.56   -1.86 2474.45    1.53 2493.55   12.58 2603.49   11.84 2653.46   15.08
#Mann= 7 ,-1 , 0
       0    .055       0  924.46   .0285       0 1575.77    .035       0
 1779.93   .0285       0    2020    .035       0 2275.54   .0285       0
 2493.55    .055       0
Levee=-1,869.01,11.53,0,,,,
Bank Sta=924.46,2493.55
XS Rating Curve= 0 ,0
Exp/Cntr(USF)=0.5,0.3
Exp/Cntr=0.3,0.1

Type RM Length L Ch R = 1 ,17129.68,501.79,500.08,500.22
XS GIS Cut Line= 2
     378547.0115    5906676.9166378572.495428576 5904037.4062686
#Sta/Elev= 30
       0    3.89   64.99    5.32  169.98    2.91  564.92    5.44  679.91    4.07
   694.9    6.04  884.88    6.04   906.3   -4.32  914.46   -5.18  1239.2    -.34
 1401.87     .18 1421.92   -1.42  1442.1   -1.12 1451.88     .93 1465.35    2.24
  1649.8    1.15 1691.46   -1.97 1730.99   -2.04 1751.29    -.32 2010.74    -.76
 2057.86    1.19 2259.69    2.07 2278.11     .16 2404.22   -1.24 2495.55    -.06
 2508.36    1.31 2522.55   11.64 2559.65   11.21 2569.64   12.97 2639.63   14.37
#Mann= 7 ,-1 , 0
       0    .055       0  884.88   .0285       0 1451.88    .035       0
  1649.8   .0285       0 2057.86    .035       0 2259.69   .0285       0
 2522.55    .055       0
Levee=-1,723.09,6.86,0,,,,
Bank Sta=884.88,2522.55
XS Rating Curve= 0 ,0
Exp/Cntr(USF)=0.5,0.3
Exp/Cntr=0.3,0.1

Type RM Length L Ch R = 1 ,16629.6 ,502.37,500.06,500.22
XS GIS Cut Line= 2
     379046.7455     5906706.877 379072.712500435904017.34020981
#Sta/Elev= 30
       0    4.11  274.97    5.17  364.95    2.61  594.93    2.99  639.92       5
  719.91    3.52  739.91    5.87  864.24    5.08  878.88    -1.9 1134.19   -2.63
 1460.43     .41 1503.75   -1.97 1590.51     .66 1720.87   -2.68  1790.4     -.4
    1800     2.9    1880     2.9 1892.95    -.21 1945.19   -1.57 2025.18    1.24
 2154.73     .59    2270     2.9    2520     2.9 2550.13     .34 2580.46    1.11
 2599.67    9.01 2619.67    8.66 2634.67   12.92 2679.66    11.9 2689.66   13.62
#Mann= 8 ,-1 , 0
       0    .055       0  864.24   .0285       0    1800    .035       0
 1892.95   .0285       0 2025.18   .0285       0    2270    .035       0
 2550.13   .0285       0 2599.67    .055       0
Levee=-1,740.51,5.87,0,,,,
Bank Sta=864.24,2599.67
XS Rating Curve= 0 ,0
Exp/Cntr(USF)=0.5,0.3
Exp/Cntr=0.3,0.1

Type RM Length L Ch R = 1 ,16129.53,375.92,507.29,629.41
XS GIS Cut Line= 2
     379546.2263    5906763.0699379572.1249567725904080.60585703
#Sta/Elev= 30
       0    4.65       5    3.23   39.96    4.16   69.94    1.12  184.83    2.95
  199.82    1.66   219.8    4.24  384.66    4.08  394.65    1.46  419.63    3.34
  554.51    3.03   564.5    1.29  619.45    3.59  649.42    2.08  759.32    3.25
  774.41    -.92 1250.86     .23 1771.25    -2.2  1821.4   -5.04  1896.7   -5.61
 1936.96     .14 2039.01   -1.41 2082.48      .6    2100     2.9    2330     2.9
  2347.9    1.15 2417.84     .77 2662.62    9.24 2672.61   12.93  2682.6   13.03
#Mann= 5 ,-1 , 0
       0    .055       0  759.32   .0285       0    2100    .035       0
  2347.9   .0285       0 2672.61    .055       0
Levee=-1,733.98,3.89,0,,,,
Bank Sta=759.32,2672.61
XS Rating Curve= 0 ,0
Exp/Cntr(USF)=0.5,0.3
Exp/Cntr=0.3,0.1

Type RM Length L Ch R = 1 ,15622.24,502.11,500.14,501.46
XS GIS Cut Line= 2
     379896.7436    5906799.3701380146.0105672965904224.39180596
#Sta/Elev= 30
       0     3.4    89.9    3.46  104.88    1.16  184.79    2.83  274.68    1.16
  339.61    4.87  639.26    2.35  761.59    4.64  777.19    -.75  854.15   -1.03
  883.03    -.15     900     2.8    1050     2.8  1071.2     .56 1303.56   -2.38
  1380.4     .79 1483.28    1.29 1698.04    1.41    1728    4.62 1757.97     .73
 1841.84    1.23 2006.04   -3.21 2057.52   -6.38 2168.37   -4.81 2187.98   -2.35
 2287.24    -.12    2310     2.8    2500     2.8 2577.02    6.65 2587.01   13.05
#Mann= 8 ,-1 , 0
       0    .055       0  761.59   .0285       0     900    .035       0
  1071.2   .0285       0 1483.28    .035       0 1841.84   .0285       0
    2310   .0285       0 2587.01    .055       0
Levee=-1,762.29,4.39,0,,,,
Bank Sta=761.59,2587.01
XS Rating Curve= 0 ,0
Exp/Cntr(USF)=0.5,0.3
Exp/Cntr=0.3,0.1

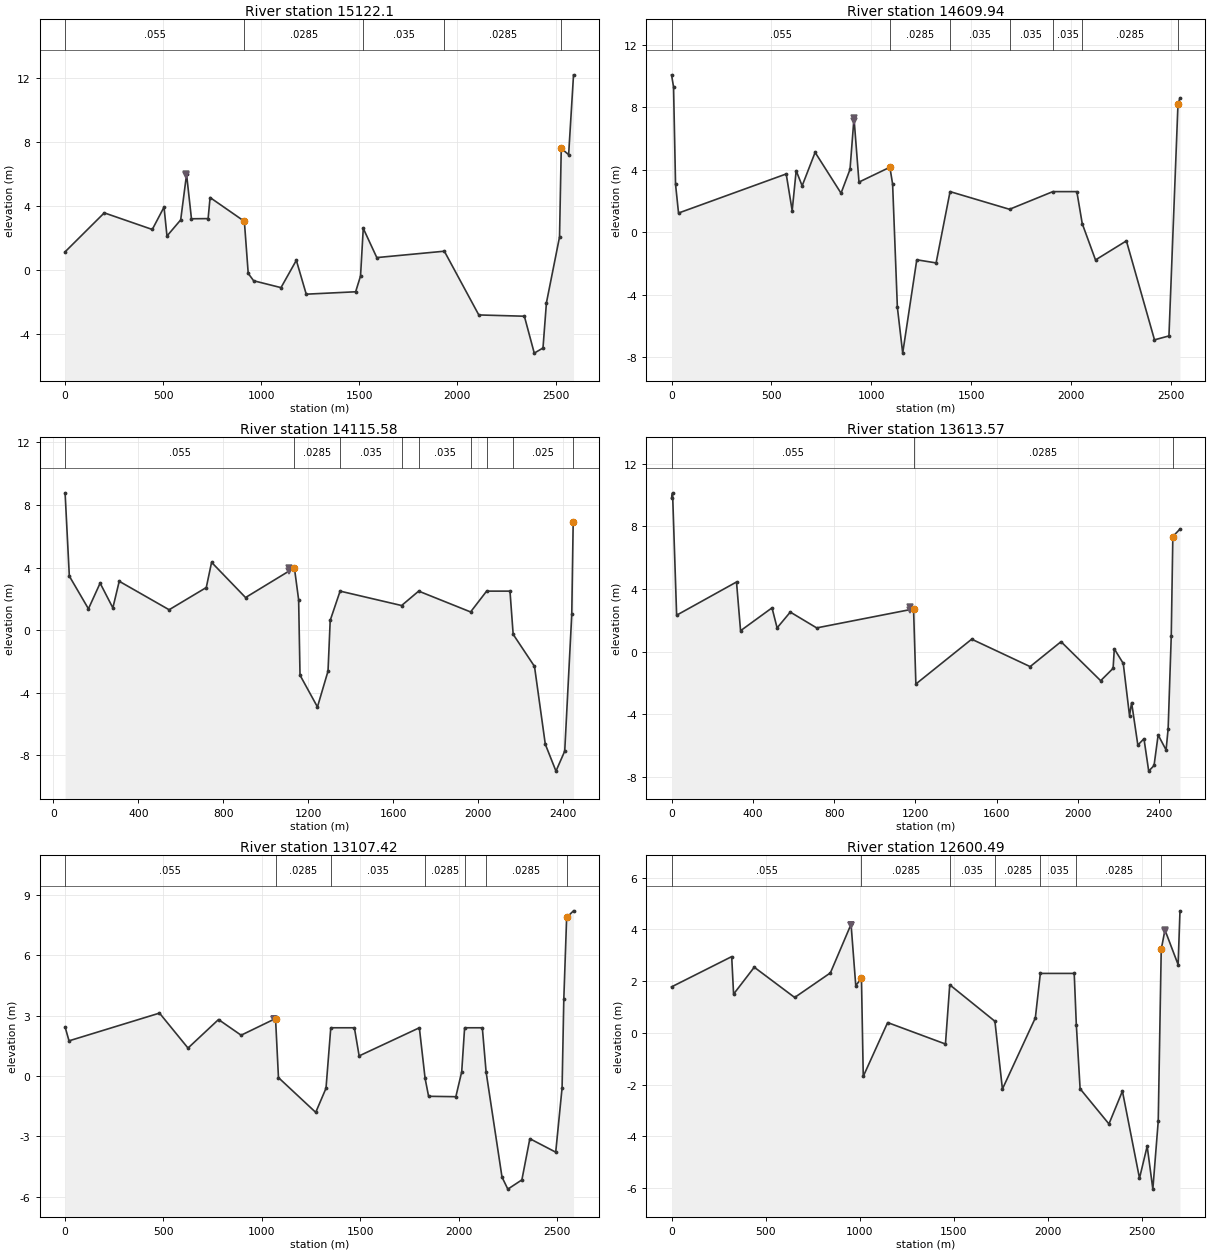
Type RM Length L Ch R = 1 ,15122.1 ,308.62,512.16,677.55
XS GIS Cut Line= 2
     380394.3265    5906848.4833380644.0627147735904268.65853826
#Sta/Elev= 30
       0    1.13  199.76    3.57  444.47    2.53  504.39    3.93  519.38    2.12
  589.29    3.13  619.26    5.98  644.23     3.2  729.12    3.21  739.11    4.53
   913.9    3.04  933.55    -.22  961.21    -.68 1100.61   -1.11 1178.85      .6
 1229.26   -1.52 1481.17   -1.37 1506.16    -.38    1520     2.6 1589.05     .77
 1933.31    1.17    2109   -2.82  2341.3    -2.9 2391.73   -5.21 2436.22   -4.89
 2453.74   -2.06 2520.54    2.06 2529.34    7.61 2566.92    7.21 2591.89   12.21
#Mann= 5 ,-1 , 0
       0    .055       0   913.9   .0285       0    1520    .035       0
 1933.31   .0285       0 2529.34    .055       0
Levee=-1,618.54,5.99,0,,,,
Bank Sta=913.9,2529.34
XS Rating Curve= 0 ,0
Exp/Cntr(USF)=0.5,0.3
Exp/Cntr=0.3,0.1

Type RM Length L Ch R = 1 ,14609.94,493.61,494.36,496.64
XS GIS Cut Line= 2
     380673.5607    5906880.9974381237.2363106745904397.48940654
#Sta/Elev= 30
       0   10.07    9.99    9.29   19.97    3.07   34.95    1.23  574.25    3.73
  604.21    1.38  624.19    3.94  654.15    2.97  719.07    5.11   848.9     2.5
  893.84    4.02  913.81     7.3  938.78    3.21 1093.58    4.16 1107.27    3.08
 1131.08    -4.8 1157.77   -7.73 1228.28   -1.76 1325.07   -1.96    1395     2.6
  1692.8    1.47    1910     2.6    2030     2.6 2057.09     .55 2123.53   -1.77
 2278.22    -.55 2418.97   -6.88 2491.35   -6.63  2536.7    8.23 2546.68    8.58
#Mann= 7 ,-1 , 0
       0    .055       0 1093.58   .0285       0    1395    .035       0
  1692.8    .035       0    1910    .035       0 2057.09   .0285       0
  2536.7    .055       0
Levee=-1,914.75,7.32,0,,,,
Bank Sta=1093.58,2536.7
XS Rating Curve= 0 ,0
Exp/Cntr(USF)=0.5,0.3
Exp/Cntr=0.3,0.1

Type RM Length L Ch R = 1 ,14115.58,502.3,502.01,505.04
XS GIS Cut Line= 2
381171.5856811245906916.59590779381701.5223553145904581.73902776
#Sta/Elev= 30
   54.99    8.78   74.98    3.46  164.96    1.37  219.95    3.01  279.94    1.43
  309.93    3.13  544.88    1.31  719.84    2.73  744.83    4.34   904.8    2.09
 1134.75    3.99 1154.74    1.95 1161.28   -2.87 1243.36    -4.9 1293.14   -2.61
 1303.42     .63    1350     2.5 1639.63    1.58    1720     2.5 1964.56    1.17
    2040     2.5    2150     2.5 2164.96    -.26 2265.42   -2.31 2316.27   -7.28
 2366.56      -9 2407.79   -7.72 2440.92    1.01 2447.58    6.89 2449.21    6.88
#Mann= 9 ,-1 , 0
   54.99    .055       0 1134.75   .0285       0    1350    .035       0
 1639.63   .0285       0    1720    .035       0 1964.56   .0285       0
    2040    .035       0 2164.96    .025       0 2447.58    .055       0
Levee=-1,1110.77,3.98,0,,,,
Bank Sta=1134.75,2447.58
XS Rating Curve= 0 ,0
Exp/Cntr(USF)=0.5,0.3
Exp/Cntr=0.3,0.1

Type RM Length L Ch R = 1 ,13613.57,343.57,506.15,654.42
XS GIS Cut Line= 2
     381642.5406    5907109.1877382196.5057057055904668.46351006
#Sta/Elev= 30
       0    9.81       5   10.13   24.98    2.32  319.72    4.44   339.7    1.33
  494.57    2.79  519.54    1.51  584.49    2.52  714.37    1.51 1191.27    2.72
 1202.68   -2.07 1477.47     .79 1765.13    -.96 1917.23     .63 2112.32   -1.86
 2173.55   -1.07 2179.47     .17 2223.55    -.76 2254.31   -4.09 2264.64   -3.26
 2295.33   -5.97 2325.51   -5.56 2348.79   -7.63 2375.13   -7.27 2395.23   -5.32
 2434.35   -6.28 2444.49   -4.92 2459.76     .98 2467.58    7.34  2502.8    7.82
#Mann= 3 , 0 , 0
       0    .055       0 1191.27   .0285       0 2467.58    .055       0
Levee=-1,1176.1,2.87,0,,,,
Bank Sta=1191.27,2467.58
XS Rating Curve= 0 ,0
Exp/Cntr(USF)=0.5,0.3
Exp/Cntr=0.3,0.1

Type RM Length L Ch R = 1 ,13107.42,506.78,506.93,512.59
XS GIS Cut Line= 2
     381956.6837    5907185.7673382774.003128878 5904735.0743965
#Sta/Elev= 30
       0    2.44   19.99    1.75   479.7    3.13  624.61    1.39  779.52    2.81
  894.44    2.03 1069.33    2.86 1084.16    -.08 1273.51   -1.81 1325.72    -.61
    1350     2.4    1470     2.4 1494.07       1    1800     2.4 1829.23    -.12
 1846.97   -1.01 1985.46   -1.03 2015.23     .21    2030     2.4    2120     2.4
 2139.19      .2 2219.94   -5.03 2249.62   -5.63 2320.98   -5.17 2361.43   -3.12
 2492.91   -3.79 2525.24    -.59 2533.97    3.81 2548.41    7.89 2583.39    8.22
#Mann= 7 ,-1 , 0
       0    .055       0 1069.33   .0285       0    1350    .035       0
 1829.23   .0285       0    2030    .035       0 2139.19   .0285       0
 2548.41    .055       0
Levee=-1,1062.85,2.85,0,,,,
Bank Sta=1069.33,2548.41
XS Rating Curve= 0 ,0
Exp/Cntr(USF)=0.5,0.3
Exp/Cntr=0.3,0.1

Type RM Length L Ch R = 1 ,12600.49,374.32,499.98,635.01
XS GIS Cut Line= 2
     382438.0603    5907344.0193383292.9487421035904780.67768102
#Sta/Elev= 30
       0    1.78  319.66    2.95  329.65     1.5  439.54    2.54  654.31    1.37
  844.11    2.32     954     4.2  978.97    1.83 1009.25    2.11 1018.85   -1.68
 1148.45      .4  1455.7    -.43 1478.45    1.86 1718.56     .45 1758.41   -2.17
 1933.41     .58    1960     2.3    2140     2.3 2151.17     .32 2171.34   -2.16
 2324.57   -3.52 2396.18   -2.25 2486.94   -5.62 2527.74   -4.38 2557.87   -6.04
 2586.54   -3.41 2602.46    3.23 2622.24    3.98 2692.17    2.64 2702.16    4.72
#Mann= 7 ,-1 , 0
       0    .055       0 1009.25   .0285       0 1478.45    .035       0
 1718.56   .0285       0    1960    .035       0 2151.17   .0285       0
 2602.46    .055       0
Levee=-1,953.33,4.17,-1,2623.52,3.97,,
Bank Sta=1009.25,2602.46
XS Rating Curve= 0 ,0
Exp/Cntr(USF)=0.5,0.3
Exp/Cntr=0.3,0.1

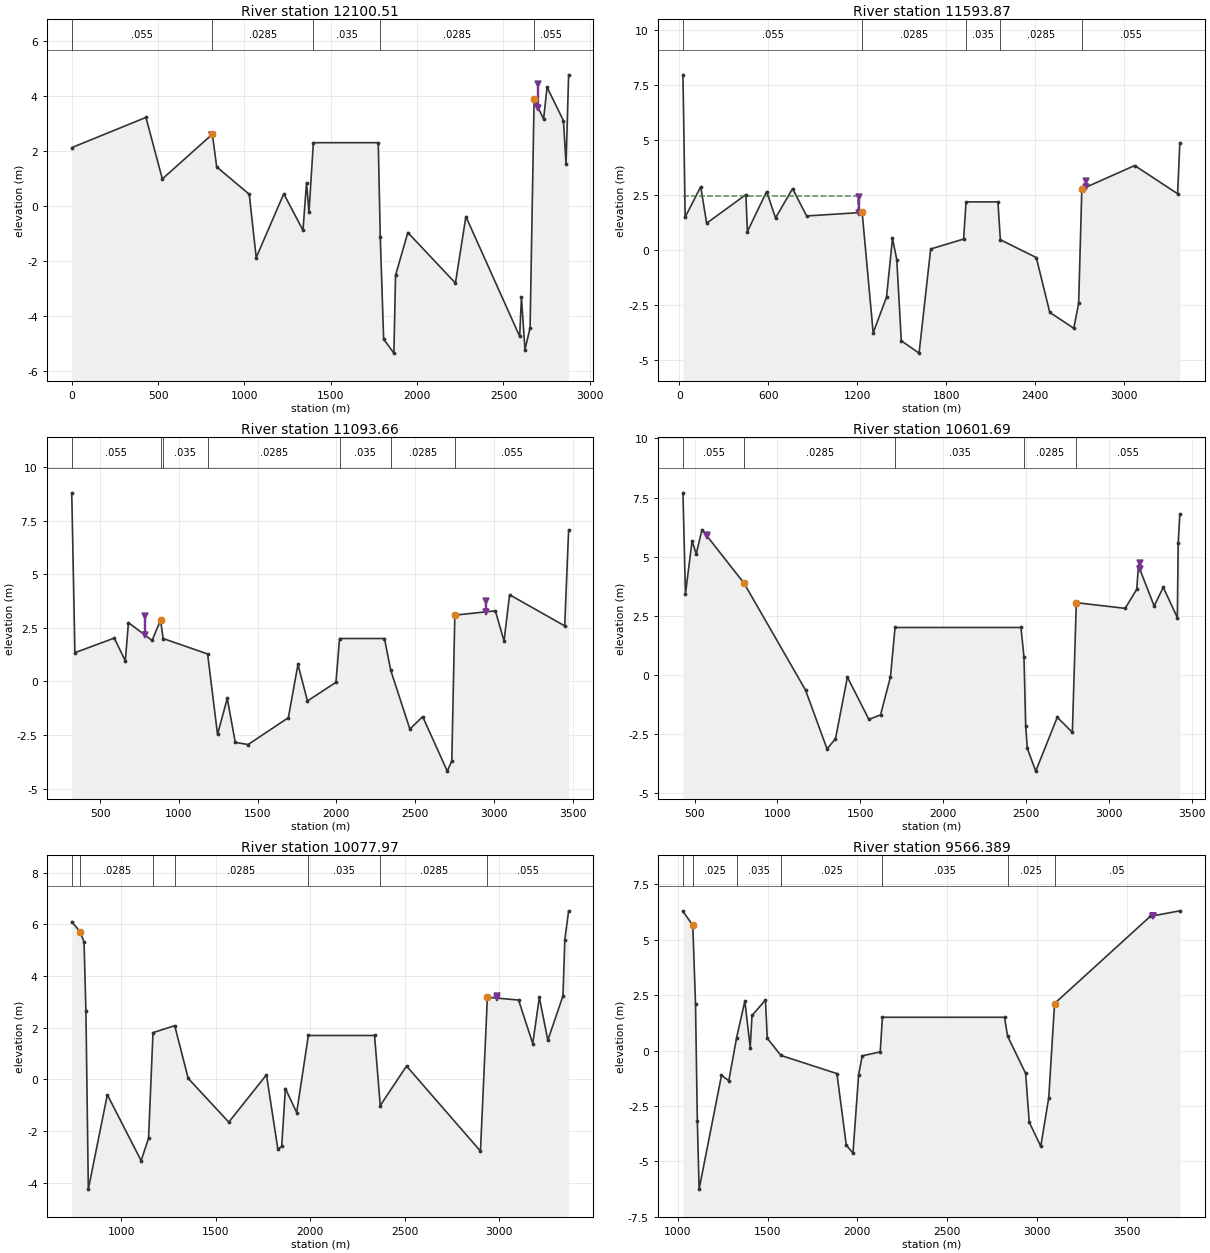
Type RM Length L Ch R = 1 ,12100.51,507.84,506.64,517.95
XS GIS Cut Line= 2
     382766.0584    5907486.1563383882.9724362735904834.38275725
#Sta/Elev= 30
       0    2.12  429.61    3.22  524.53     .98  814.27    2.61  839.24    1.42
 1028.06     .42  1068.1   -1.88 1227.78     .44  1339.1    -.89 1359.59     .85
 1373.84    -.24    1399     2.3    1775     2.3 1786.65   -1.15 1806.19   -4.85
  1865.5   -5.36 1875.11   -2.53 1946.11    -.97 2221.91   -2.81 2282.48    -.39
 2593.96   -4.75  2604.1   -3.33 2624.62   -5.23 2654.18   -4.44 2677.52    3.88
 2732.54    3.16 2752.52    4.32 2847.44     3.1 2862.43    1.52 2877.41    4.77
#Mann= 5 ,-1 , 0
       0    .055       0  814.27   .0285       0    1399    .035       0
 1786.65   .0285       0 2677.52    .055       0
Levee=-1,814.65,2.59,-1,2700.68,4.44,,
Bank Sta=814.27,2677.52
XS Rating Curve= 0 ,0
Exp/Cntr(USF)=0.5,0.3
Exp/Cntr=0.3,0.1

Type RM Length L Ch R = 1 ,11593.87,500.02,500.21,510.72
XS GIS Cut Line= 2
 383237.132849855907671.67422207384538.3860898175904582.24324925
#Sta/Elev= 30
   24.98    7.97   39.97    1.51  144.88    2.89  184.85    1.23  449.63    2.53
  459.63     .85  589.52    2.67  649.47    1.47  764.38     2.8   859.3    1.56
 1233.97    1.72 1308.37   -3.75 1398.27   -2.13 1438.68     .54 1467.52    -.42
 1498.12   -4.11 1618.06   -4.67 1696.26     .06 1918.41     .51    1935     2.2
    2150     2.2 2166.39     .48 2408.88    -.33 2499.89   -2.82 2661.77   -3.54
 2694.65   -2.41 2716.07    2.78  3072.5    3.85 3362.26    2.57 3377.25    4.89
#Mann= 5 ,-1 , 0
   24.98    .055       0 1233.97   .0285       0    1935    .035       0
 2166.39   .0285       0 2716.07    .055       0
Levee=-1,1209.75,2.42,-1,2742.75,3.17,,
#XS Ineff= 2 , 0
         1208.84    2.45
Permanent Ineff=
       F       F
Bank Sta=1233.97,2716.07
XS Rating Curve= 0 ,0
Exp/Cntr(USF)=0.5,0.3
Exp/Cntr=0.3,0.1

Type RM Length L Ch R = 1 ,11093.66,491.8,491.97,502.32
XS GIS Cut Line= 2
383807.9580584745907604.52322911385032.3599334045904697.55254782
#Sta/Elev= 30
  319.93    8.79  339.93    1.34  589.87    2.02  659.85     .96  679.85    2.74
  829.82    1.91  883.79    2.86     900       2 1182.45    1.28 1245.39   -2.47
 1307.02    -.79 1357.95   -2.84 1439.62   -2.94 1694.85   -1.69 1755.94     .79
  1816.3    -.91 1997.19    -.04    2020       2    2305       2 2345.31     .51
 2466.34   -2.22 2547.56   -1.64 2703.86   -4.18 2732.63    -3.7 2751.84    3.09
 3009.34    3.29 3064.32    1.88 3099.31    4.04 3449.24    2.59 3474.23    7.05
#Mann= 7 ,-1 , 0
  319.93    .055       0  883.79   .0285       0     900    .035       0
 1182.45   .0285       0    2020    .035       0 2345.31   .0285       0
 2751.84    .055       0
Levee=-1,787.18,3.03,-1,2949.6,3.73,,
Bank Sta=883.79,2751.84
XS Rating Curve= 0 ,0
Exp/Cntr(USF)=0.5,0.3
Exp/Cntr=0.3,0.1

Type RM Length L Ch R = 1 ,10601.69,526.02,523.72,530.89
XS GIS Cut Line= 2
384301.0055540255907700.86502134385465.0994229265904937.07748273
#Sta/Elev= 30
  429.85     7.7  444.84    3.42  484.83    5.66  509.82    5.11  544.81    6.14
  798.93    3.87 1169.64    -.65 1299.47   -3.14 1350.44   -2.71 1422.37     -.1
 1552.04   -1.89 1622.46    -1.7 1682.26    -.09    1710       2    2470       2
 2488.12     .75 2498.41   -2.17  2508.4   -3.12 2559.13   -4.08  2689.2    -1.8
 2780.11   -2.44 2804.01    3.05 3098.91    2.81 3168.89    3.62 3178.88    4.62
 3273.85    2.91 3328.83     3.7  3413.8    2.42  3418.8    5.56  3428.8    6.79
#Mann= 5 ,-1 , 0
  429.85    .055       0  798.93   .0285       0    1710    .035       0
 2488.12   .0285       0 2804.01    .055       0
Levee=-1,575.61,5.93,-1,3186.06,4.74,,
Bank Sta=798.93,2804.01
XS Rating Curve= 0 ,0
Exp/Cntr(USF)=0.5,0.3
Exp/Cntr=0.3,0.1

Type RM Length L Ch R = 1 ,10077.97,521.17,511.58,513.31
XS GIS Cut Line= 2
384898.0292449925907629.68823968 385917.752832965905208.66400365
#Sta/Elev= 30
  739.16     6.1  784.11     5.7  804.09    5.31  814.08    2.64  826.78   -4.24
  927.22    -.59 1105.96   -3.14 1145.18   -2.27 1168.67    1.81 1283.54    2.08
 1354.91     .04 1569.39   -1.65 1768.62     .18 1828.84   -2.69 1849.01   -2.59
 1868.77    -.35 1928.43   -1.28    1990     1.7    2340     1.7 2370.21   -1.01
 2509.08     .52 2900.01   -2.77 2936.67    3.18 3101.48    3.07  3176.4    1.39
 3211.36    3.17 3256.31    1.52 3336.22    3.23 3346.21    5.41 3366.18    6.52
#Mann= 7 ,-1 , 0
  739.16    .055       0  784.11   .0285       0 1168.67    .035       0
 1283.54   .0285       0    1990    .035       0 2370.21   .0285       0
 2936.67    .055       0
Levee=0,,,-1,2986.93,3.24,,
Bank Sta=784.11,2936.67
XS Rating Curve= 0 ,0
Exp/Cntr(USF)=0.5,0.3
Exp/Cntr=0.3,0.1

Type RM Length L Ch R = 1 ,9566.389,526.44,517.03,518.5
XS GIS Cut Line= 2
385449.7997380945907631.53848298386524.0371976565905081.08760957
#Sta/Elev= 30
 1029.06    6.28 1084.01    5.64 1098.99    2.08 1109.18    -3.2 1119.08   -6.25
 1243.67   -1.12 1284.32   -1.36 1327.92     .58 1373.74    2.23 1403.71     .13
  1413.7    1.58 1488.64    2.28 1498.63     .55 1574.67    -.22 1886.65   -1.04
 1938.64   -4.26 1976.05   -4.63 2007.33    -1.1 2027.41    -.24 2127.86    -.06
    2140     1.5    2820     1.5 2837.14     .65 2937.68   -1.03 2957.71   -3.23
 3022.05   -4.32 3066.55   -2.12 3098.76    2.12 3631.68    6.05 3796.52     6.3
#Mann= 7 ,-1 , 0
 1029.06    .055       0 1084.01    .025       0 1327.92    .035       0
 1574.67    .025       0    2140    .035       0 2837.14    .025       0
 3098.76     .05       0
Levee=-1,992.53,6.21,-1,3649.66,6.06,,
Bank Sta=1084.01,3098.76
XS Rating Curve= 0 ,0
Exp/Cntr(USF)=0.5,0.3
Exp/Cntr=0.3,0.1