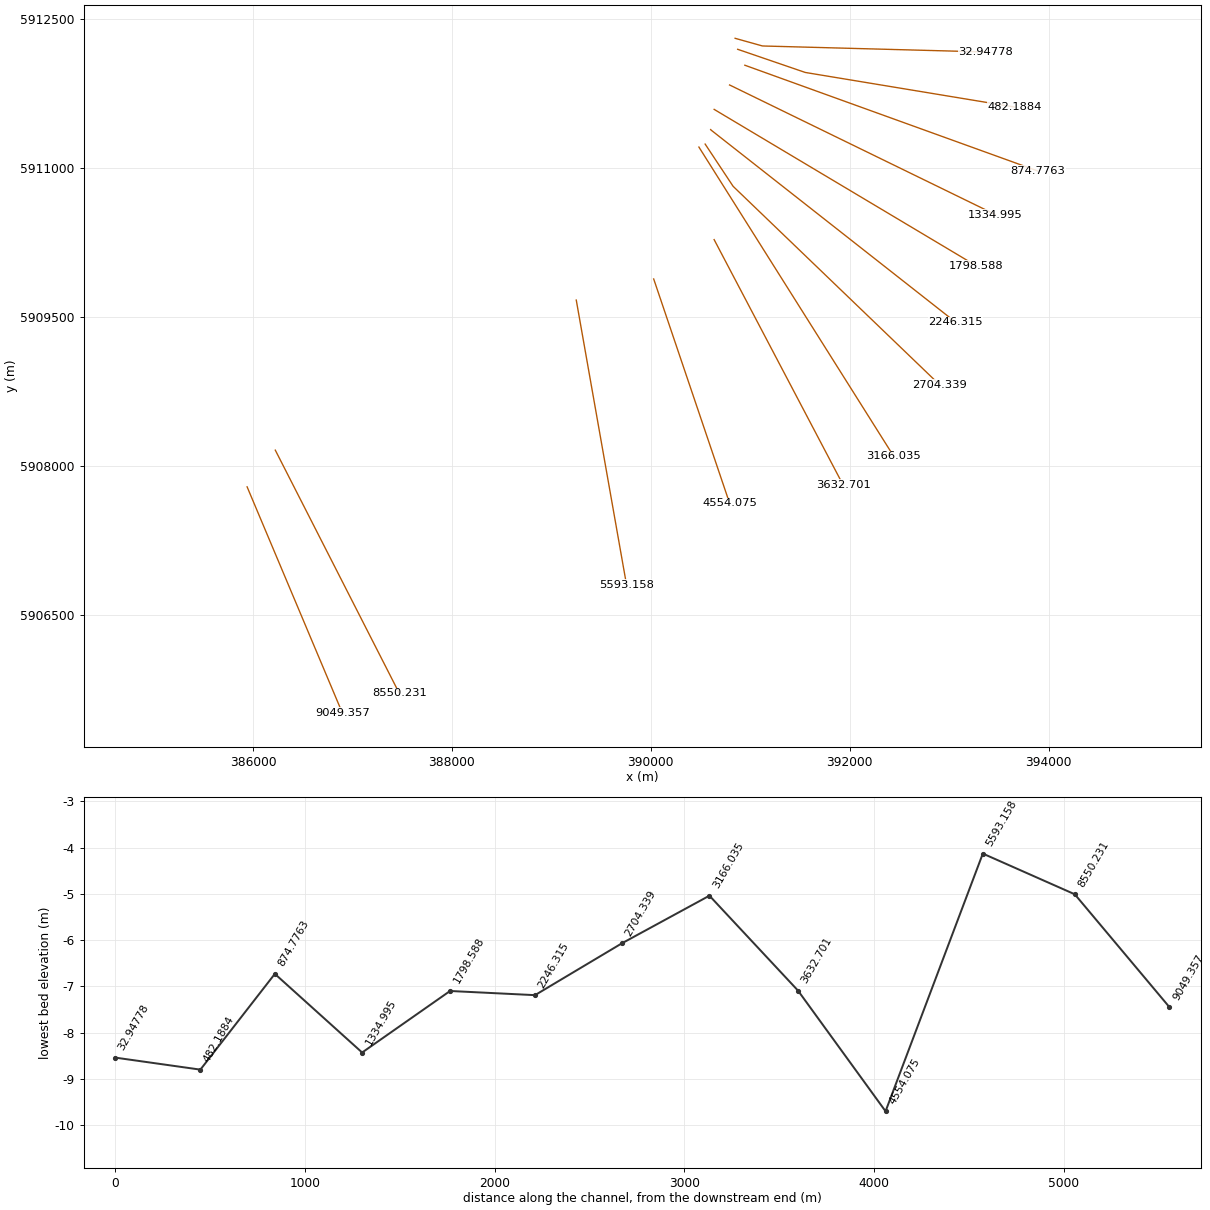
HEC-RAS study Churchill_Forecasting.prj: ChurchillRiver_Forecasting

--- Churchill_Forecasting.g14 (geometry) --- (continued)

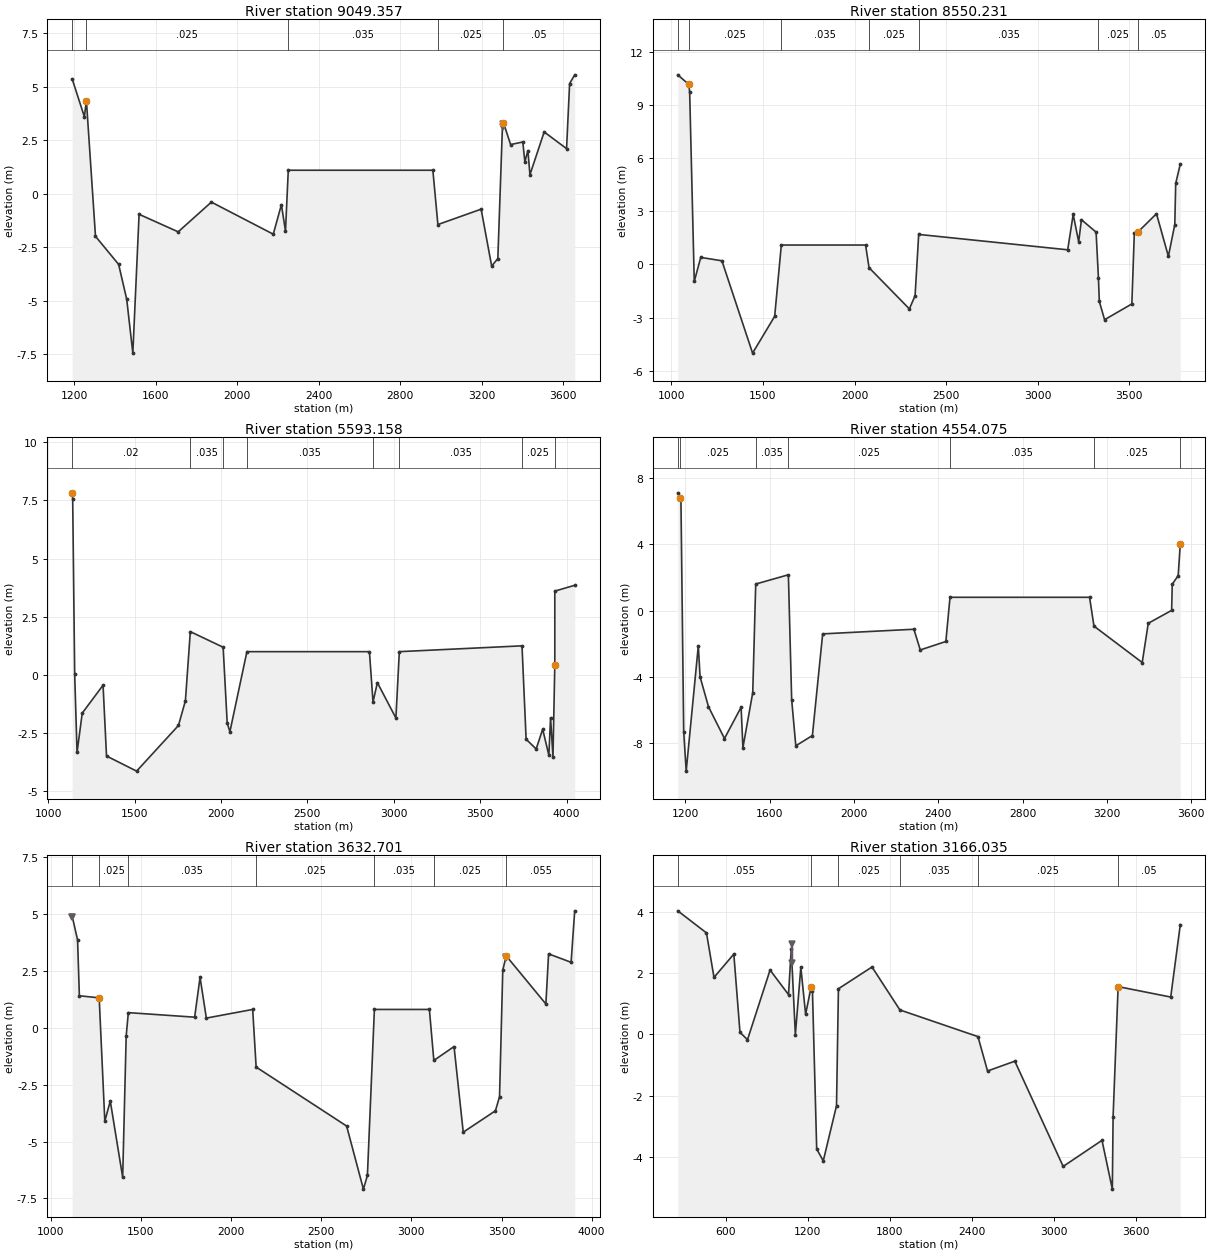
Type RM Length L Ch R = 1 ,9049.357,354.9,499.13,661.51
XS GIS Cut Line= 2
 385939.925172245907792.99225504 386897.77358476 5905518.8719472
#Sta/Elev= 30
 1188.85    5.37 1248.79     3.6 1258.78    4.35 1303.36   -1.99 1416.97    -3.3
 1456.65   -4.93 1486.76   -7.45 1517.45    -.96 1709.48   -1.78  1872.4    -.39
 2176.28   -1.89 2216.36    -.51 2236.34   -1.75    2250     1.1    2960     1.1
 2984.65   -1.44 3196.95    -.72 3248.71   -3.38 3279.04   -3.03 3301.79    3.19
 3306.79    3.32 3341.76     2.3  3401.7    2.42 3411.69    1.49 3426.67    2.02
 3436.66     .89 3506.59    2.89 3616.49    2.11 3631.47    5.15 3656.45    5.56
#Mann= 5 ,-1 , 0
 1188.85    .055       0 1258.78    .025       0    2250    .035       0
 2984.65    .025       0 3306.79     .05       0
Levee=0,,,-1,3304.29,3.14,,
Bank Sta=1258.78,3306.79
XS Rating Curve= 0 ,0
Exp/Cntr(USF)=0.5,0.3
Exp/Cntr=0.3,0.1

Type RM Length L Ch R = 1 ,8550.231,401.22,484.88,570.88
XS GIS Cut Line= 2
 386223.317029655908162.16379178387469.8446558355905717.89075788
#Sta/Elev= 30
 1034.53   10.72  1094.5   10.18  1099.5    9.75 1124.65    -.96    1160      .4
 1275.53     .21 1443.08   -5.01 1563.68   -2.93    1600     1.1    2060     1.1
 2078.92    -.18 2299.18   -2.51 2330.35   -1.76    2350     1.7 3163.57     .83
 3193.56    2.83 3223.54    1.28 3238.54    2.53 3318.57    1.83 3331.32    -.74
 3336.26   -2.09 3364.92   -3.12 3513.83   -2.23  3527.3    1.78  3548.4    1.85
 3648.35    2.87 3713.32     .46 3748.31    2.26 3753.31    4.58  3778.3    5.68
#Mann= 7 ,-1 , 0
 1034.53    .055       0  1094.5    .025       0    1600    .035       0
 2078.92    .025       0    2350    .035       0 3331.32    .025       0
  3548.4     .05       0
Bank Sta=1094.5,3548.4
XS Rating Curve= 0 ,0
Exp/Cntr(USF)=0.5,0.3
Exp/Cntr=0.3,0.1

Type RM Length L Ch R = 1 ,5593.158,526.82,512.81,384.54
XS GIS Cut Line= 2
389250.1617883315909671.42304574 389755.785370025906807.62898116
#Sta/Elev= 30
 1138.77    7.82 1141.74    7.57 1153.27     .04 1167.07   -3.33 1197.04   -1.64
 1317.54    -.44 1337.52   -3.48 1511.71   -4.13 1753.84   -2.17 1794.09   -1.11
 1822.49    1.86 2012.44    1.19  2035.9   -2.06 2051.49   -2.44    2150       1
    2859       1  2879.7   -1.16    2905    -.33 3012.18   -1.85    3032       1
 3741.94    1.25 3765.71   -2.76 3823.92   -3.18 3861.54   -2.33 3897.37   -3.45
 3907.15   -1.84 3921.11   -3.51 3931.72     .41 3931.72     3.6 4046.85    3.85
#Mann= 8 ,-1 , 0
 1138.77     .02       0 1822.49    .035       0 2012.44    .025       0
    2150    .035       0  2879.7    .025       0    3032    .035       0
 3741.94    .025       0 3931.72     .05       0
Bank Sta=1138.77,3931.72
XS Rating Curve= 0 ,0
Exp/Cntr(USF)=0.5,0.3
Exp/Cntr=0.3,0.1

Type RM Length L Ch R = 1 ,4554.075,342.12,461.93,591.45
XS GIS Cut Line= 2
390028.8622690035909883.80463814390793.2241185295907625.73349269
#Sta/Elev= 30
 1164.47    7.11 1174.47     6.8 1179.47    6.78 1192.64   -7.31 1204.46    -9.7
    1262   -2.13 1270.28      -4 1310.23   -5.81 1386.11   -7.73 1464.99   -5.84
 1473.59   -8.28 1520.19   -4.96  1534.3     1.6 1689.24    2.16 1704.87   -5.39
 1724.43   -8.17 1803.21   -7.55 1851.89   -1.41 2284.66   -1.13 2314.93   -2.38
 2436.28   -1.87    2456      .8    3118      .8 3138.88    -.94 3367.75   -3.14
 3396.49    -.77 3507.35     .01 3510.28    1.59  3538.4    2.11 3548.39    4.03
#Mann= 7 ,-1 , 0
 1164.47    .055       0 1174.47    .025       0  1534.3    .035       0
 1689.24    .025       0    2456    .035       0 3138.88    .025       0
 3548.39     .05       0
Bank Sta=1174.47,3548.39
XS Rating Curve= 0 ,0
Exp/Cntr(USF)=0.5,0.3
Exp/Cntr=0.3,0.1

Type RM Length L Ch R = 1 ,3632.701,300.31,466.67,610.79
XS GIS Cut Line= 2
390636.7859122825910279.42911882391933.7067771495907812.47081517
#Sta/Elev= 30
 1118.83     4.9  1148.8    3.85 1158.79     1.4 1268.67    1.31 1299.91   -4.11
  1330.2   -3.22 1398.96   -6.57 1418.39    -.37  1430.3     .66 1798.12     .46
 1828.09    2.21 1863.05     .42    2120      .8 2139.16   -1.73    2641   -4.32
 2733.99   -7.09 2756.27   -6.49    2795      .8    3100      .8 3124.71   -1.44
 3236.67    -.83 3287.74   -4.59 3466.35   -3.65 3489.02   -3.03 3507.02    2.53
 3526.31    3.15 3746.08    1.04 3761.06    3.24 3885.93    2.87 3905.91    5.13
#Mann= 7 ,-1 , 0
 1118.83    .055       0 1268.67    .025       0  1430.3    .035       0
 2139.16    .025       0    2795    .035       0 3124.71    .025       0
 3526.31    .055       0
Levee=-1,1120.1,4.85,-1,3525.2,3.08,,
Bank Sta=1268.67,3526.31
XS Rating Curve= 0 ,0
Exp/Cntr(USF)=0.5,0.3
Exp/Cntr=0.3,0.1

Type RM Length L Ch R = 1 ,3166.035,68.41,461.7,899.38
XS GIS Cut Line= 2
390483.5749218815911210.51167892392442.0912198995908101.93129383
#Sta/Elev= 30
  249.94    4.03  459.89    3.31  514.87    1.86  659.84    2.62  704.83     .07
  759.82    -.17  924.78     2.1 1059.74     1.3 1079.74    2.79 1109.73    -.01
 1149.72    2.19 1184.71     .66  1224.7    1.54  1234.7    1.42 1265.75   -3.73
 1313.75   -4.12 1410.68   -2.32 1424.65    1.49    1670     2.2    1874      .8
 2444.87    -.07 2514.75   -1.19 2714.23    -.87 3067.77    -4.3 3351.57   -3.45
 3427.21   -5.04 3432.73   -2.68 3469.57    1.56 3854.07    1.22 3924.05    3.58
#Mann= 6 ,-1 , 0
  249.94    .055       0  1224.7    .025       0 1424.65    .025       0
    1874    .035       0 2444.87    .025       0 3469.57     .05       0
Levee=-1,1084.74,2.94,0,,,,
Bank Sta=1224.7,3469.57
XS Rating Curve= 0 ,0
Exp/Cntr(USF)=0.5,0.3
Exp/Cntr=0.3,0.1

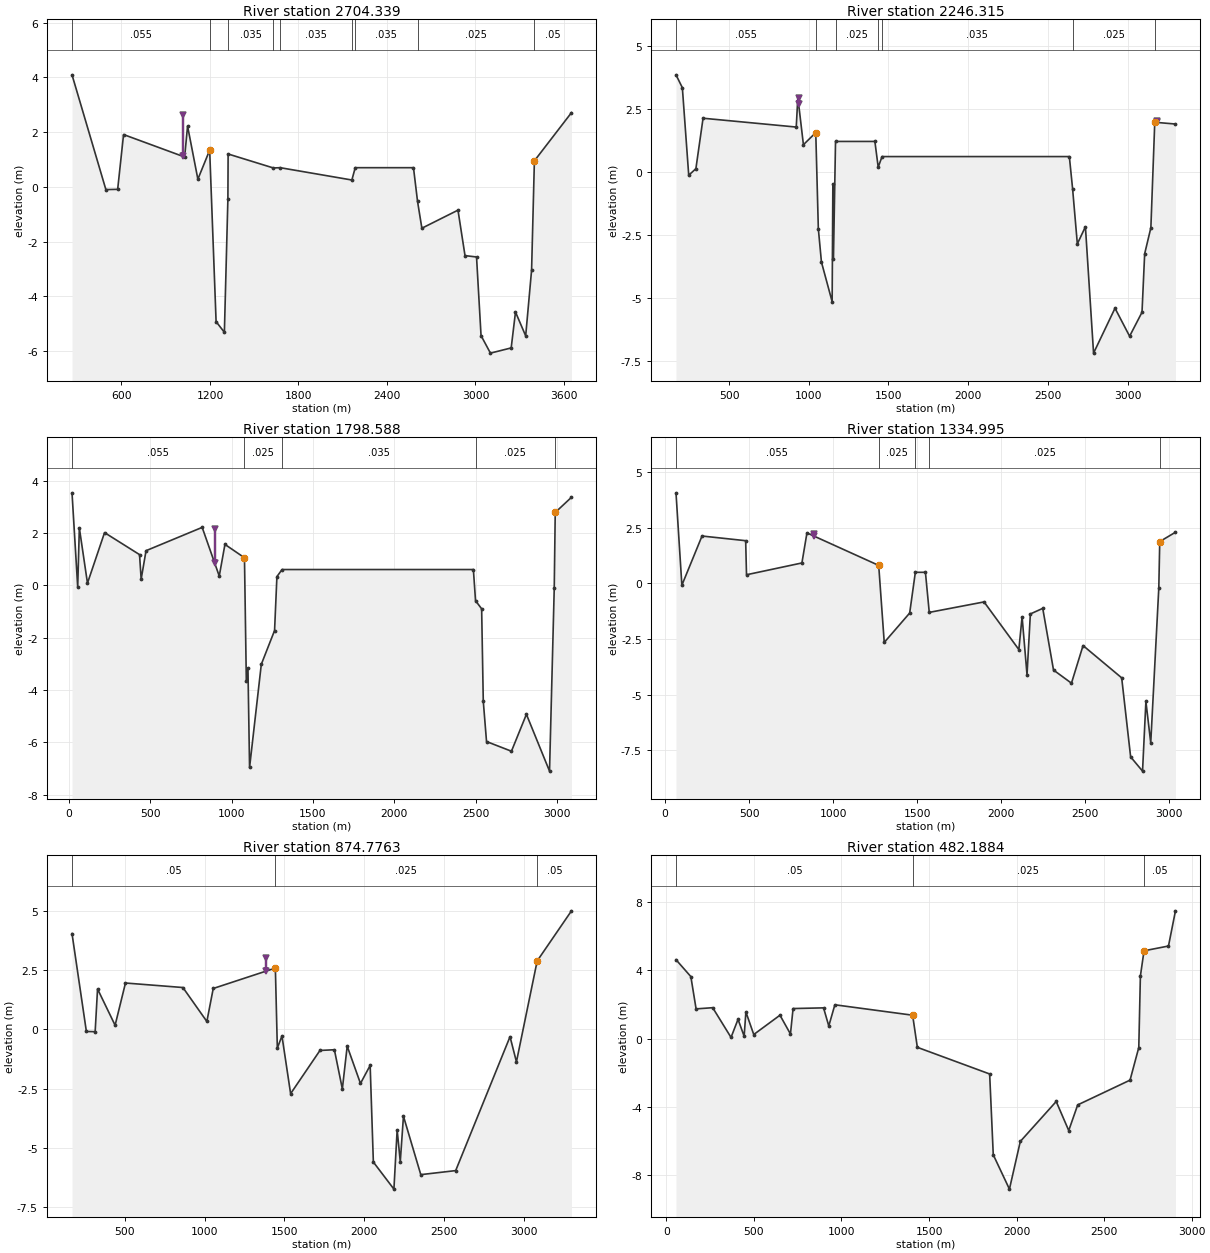
Type RM Length L Ch R = 1 ,2704.339,128.41,458.02,647.53
XS GIS Cut Line= 5
390546.482932983 5911240.2147802      390827.651     5910815.629
     391054.1582    5910597.9076     392772.7882    5908945.9397
392902.1857969325908821.56116645
#Sta/Elev= 30
  264.61    4.09  494.27     -.1  574.15    -.09  614.09    1.91 1028.19    1.09
 1048.14    2.22 1118.02     .28 1197.98    1.34 1241.56   -4.92 1297.72   -5.31
 1321.59    -.44 1323.08     1.2 1629.91     .69    1676      .7  2162.2     .25
    2185      .7    2580      .7 2607.48    -.53 2636.87   -1.51 2881.73    -.85
 2929.38   -2.51 3007.52   -2.56 3038.08   -5.43 3101.79   -6.07 3242.48   -5.88
 3271.66   -4.57 3340.77   -5.44 3380.81   -3.04 3399.84     .95 3651.36    2.71
#Mann= 9 ,-1 , 0
  264.61    .055       0 1197.98    .025       0 1323.08    .035       0
 1629.91    .025       0    1676    .035       0  2162.2    .025       0
    2185    .035       0 2607.48    .025       0 3399.84     .05       0
Levee=-1,1017.42,2.63,0,,,,
Bank Sta=1197.98,3399.84
XS Rating Curve= 0 ,0
Exp/Cntr(USF)=0.5,0.3
Exp/Cntr=0.3,0.1

Type RM Length L Ch R = 1 ,2246.315,201.07,447.73,682.36
XS GIS Cut Line= 5
390602.0439653975911386.35436667     390604.7077    5911382.2168
     391119.4203    5910977.8704     393002.1305    5909498.8561
393064.9786581125909449.48402307
#Sta/Elev= 30
  167.25    3.84  207.15    3.33  247.12    -.14  292.09     .12  337.06    2.12
  921.68    1.77  931.68    2.95  966.67    1.07 1044.13    1.55 1060.28   -2.26
 1079.71   -3.58 1146.87   -5.15 1151.37    -.48 1155.11   -3.44 1168.14     1.2
    1415     1.2 1435.84     .18    1460      .6    2635      .6 2655.37    -.67
 2685.18   -2.86 2735.84   -2.18 2786.97   -7.19 2921.46   -5.41 3013.13   -6.52
 3090.88   -5.57  3107.6   -3.25 3146.49   -2.22 3170.91    1.96 3300.82    1.89
#Mann= 7 ,-1 , 0
  167.25    .055       0 1044.13    .025       0 1168.14    .025       0
 1435.84    .025       0    1460    .035       0 2655.37    .025       0
 3170.91     .05       0
Levee=-1,936.53,2.93,-1,3182.95,2,,
Bank Sta=1044.13,3170.91
XS Rating Curve= 0 ,0
Exp/Cntr(USF)=0.5,0.3
Exp/Cntr=0.3,0.1

Type RM Length L Ch R = 1 ,1798.588,304.53,463.59,618.77
XS GIS Cut Line= 2
390637.0621078185911589.11775628393271.2730150155910017.30875395
#Sta/Elev= 30
   19.98    3.53   54.96    -.07   64.95    2.19  114.91     .08  219.82    2.01
  434.65    1.17  444.64     .23  474.61    1.32  819.34    2.21  924.25     .35
  959.22    1.56 1079.12    1.05 1090.51   -3.66 1100.51   -3.17 1110.43   -6.96
 1182.54   -3.02 1263.96   -1.73 1278.38     .33    1310      .6    2485      .6
 2498.16    -.59 2535.72     -.9 2545.77   -4.43 2565.72   -5.97 2718.78   -6.34
 2810.65   -4.93 2952.61    -7.1  2981.6    -.11 2987.67    2.78  3087.5    3.36
#Mann= 5 ,-1 , 0
   19.98    .055       0 1079.12    .025       0    1310    .035       0
 2498.16    .025       0 2987.67     .05       0
Levee=-1,896.08,2.13,0,,,,
Bank Sta=1079.12,2987.67
XS Rating Curve= 0 ,0
Exp/Cntr(USF)=0.5,0.3
Exp/Cntr=0.3,0.1

Type RM Length L Ch R = 1 ,1334.995,253.1,460.22,659.21
XS GIS Cut Line= 2
 390792.220074915911834.79118767393465.0882618155910531.40471842
#Sta/Elev= 30
   64.97    4.07   99.96    -.08  219.91    2.13  479.79    1.92  484.79     .39
  814.65     .92  844.64    2.27 1271.83     .81 1304.79   -2.65 1456.24   -1.33
    1490      .5    1550      .5 1572.79    -1.3 1899.07    -.83 2106.24   -2.97
 2125.52    -1.5 2154.84    -4.1 2174.77   -1.37 2248.47   -1.12 2312.62   -3.89
 2419.44   -4.48 2488.46   -2.79 2718.44   -4.24 2771.74   -7.79 2842.63   -8.43
 2862.62    -5.3 2891.47   -7.16 2939.42    -.21 2945.11    1.88 3038.69     2.3
#Mann= 5 ,-1 , 0
   64.97    .055       0 1271.83    .025       0    1490    .035       0
 1572.79    .025       0 2945.11     .05       0
Levee=-1,886.75,2.21,0,,,,
Bank Sta=1271.83,2945.11
XS Rating Curve= 0 ,0
Exp/Cntr(USF)=0.5,0.3
Exp/Cntr=0.3,0.1

Type RM Length L Ch R = 1 ,874.7763,130.1,392.59,756.18
XS GIS Cut Line= 2
390945.7688758475912033.34841432393889.1190668035910970.79641399
#Sta/Elev= 30
  169.96    4.03  259.94    -.09  314.93     -.1  329.92     1.7   439.9     .17
  504.88    1.95   864.8    1.76 1014.76     .33 1054.75    1.72 1443.96    2.58
 1456.32    -.79 1485.34    -.28 1539.55   -2.71 1723.42    -.89 1813.77    -.86
  1863.6   -2.51 1894.03    -.71 1977.21   -2.28 2037.84   -1.52 2057.93   -5.59
 2186.72   -6.73 2206.94   -4.24 2226.61   -5.57 2246.48   -3.66 2355.05   -6.12
 2573.68   -5.95 2914.17    -.31 2954.33   -1.37 3084.28    2.88 3299.23    4.99
#Mann= 3 , 0 , 0
  169.96     .05       0 1443.96    .025       0 3084.28     .05       0
Levee=-1,1387.68,3.02,0,,,,
Bank Sta=1443.96,3084.28
XS Rating Curve= 0 ,0
Exp/Cntr(USF)=0.5,0.3
Exp/Cntr=0.3,0.1

Type RM Length L Ch R = 1 ,482.1884,112.67,449.24,772.32
XS GIS Cut Line= 6
390873.5266551075912193.57600555      391553.291    5911960.6071
     392048.4026     5911878.808     392049.5722    5911878.6148
     393653.9463    5911613.5507393658.868451062 5911612.7374948
#Sta/Elev= 30
   54.89    4.63  139.72    3.64  169.66    1.75  264.48    1.82  369.27     .08
  409.19    1.14  444.12     .15   454.1    1.57  499.01     .25  648.71    1.38
   708.6     .28  723.57    1.77  897.68    1.81  927.49     .75  962.27    1.99
 1406.43    1.38 1433.33     -.5 1846.32   -2.06 1866.93   -6.79  1959.3    -8.8
 2021.33   -6.01 2226.43   -3.67 2297.97   -5.37 2349.14   -3.87 2648.16   -2.42
 2698.07    -.51 2707.23    3.67 2728.01    5.15 2867.68    5.43 2907.59    7.49
#Mann= 3 , 0 , 0
   54.89     .05       0 1406.43    .025       0 2728.01     .05       0
Bank Sta=1406.43,2728.01
XS Rating Curve= 0 ,0
Exp/Cntr(USF)=0.5,0.3
Exp/Cntr=0.3,0.1

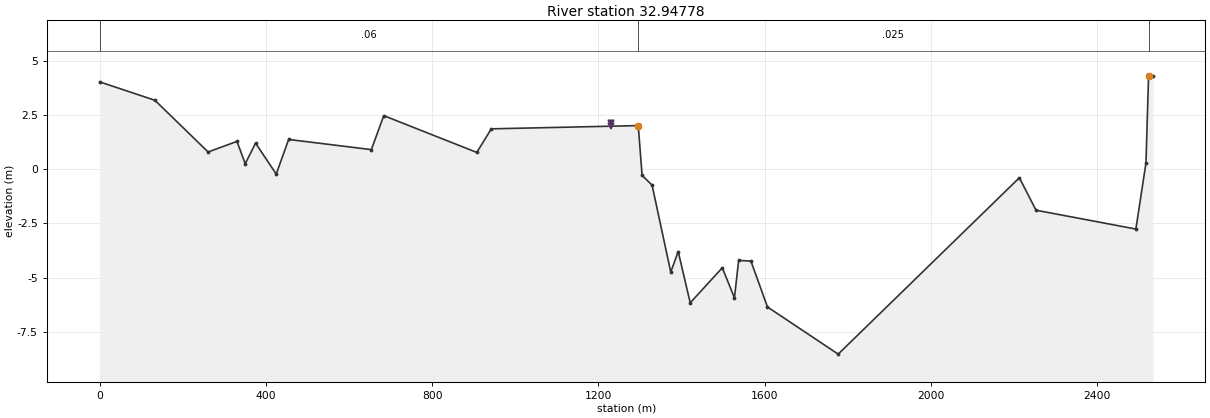
Type RM Length L Ch R = 1 ,32.94778,0,0,0
XS GIS Cut Line= 4
     390848.0599    5912303.9762     391122.9355    5912226.9858
     392022.9791    5912202.7855393370.1307005935912166.56340159
#Sta/Elev= 30
       0    4.04  132.88    3.19  260.85      .8  330.22    1.29  350.12     .26
  374.99    1.21  424.74    -.22  454.58    1.38  653.56     .91  683.41    2.48
  907.26     .78  942.08    1.87 1295.63    2.02 1304.89    -.28 1328.88    -.73
 1373.84   -4.75 1391.75    -3.8 1420.65   -6.17 1497.82   -4.55 1527.11   -5.94
 1537.09   -4.21 1566.68   -4.24 1606.47   -6.36 1776.63   -8.54 2212.53    -.39
 2252.57   -1.89 2492.79   -2.76  2517.1     .29 2523.36    4.32 2533.43    4.31
#Mann= 3 , 0 , 0
       0     .06       0 1295.63    .025       0 2523.36     .06       0
Levee=-1,1229,2.12,0,,,,
Bank Sta=1295.63,2523.36
XS Rating Curve= 0 ,0
Exp/Cntr(USF)=0.5,0.3
Exp/Cntr=0.3,0.1